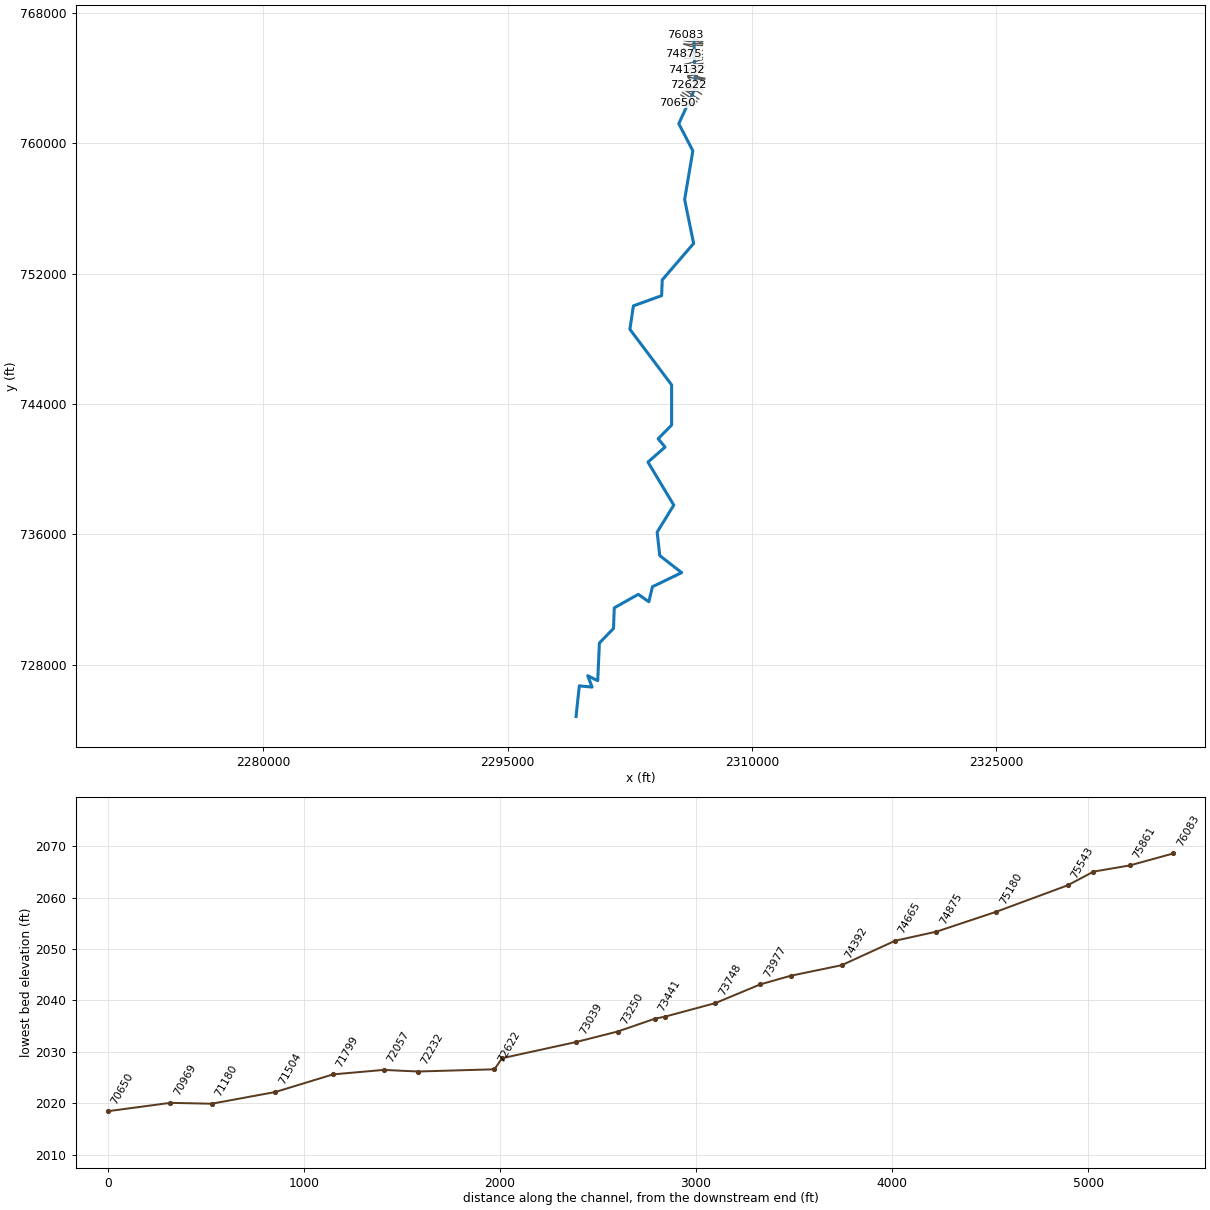
--- LEADNGCK.prj (project) ---

Proj Title=LEADNGCK
Current Plan=p01
Default Exp/Contr=0,0
English Units
Geom File=g01
Flow File=f01
Plan File=p01
BEGIN DESCRIPTION:
----------MODEL BY WOOD PLC 2022----------
AFH study
Randolph County, WV
HEC-RAS Version: RAS 6.2
Vertical Datum: NAVD88
Projection: NAD 1983 StatePlane West Virginia S FIPS 4702 (US Feet)
Terrain: 1-meter LIDAR (FEMA Region III 3DEP collected 2016-2018)
Land Use: 2019 NLCD
Hydrologic Method:
WV SIR2010-5033 regression equations
Additional Model Notes:
None
END DESCRIPTION:
DSS Export Rating Curves= 0
DSS Export Rating Curve Sorted= 0
DSS Export Volume Flow Curves= 0
DXF OffsetX= 0
DXF OffsetY= 0
DXF ScaleX= 0
DXF ScaleY= 0

--- LEADNGCK.p01 (plan) ---

Plan Title=Floodplain
Program Version=6.20
Short Identifier=Floodplain
Geom File=g01
Flow File=f01
Subcritical Flow
K Sum by GR= 0
Std Step Tol= 0.01
Critical Tol= 0.01
Num of Std Step Trials= 20
Max Error Tol= 0.3
Flow Tol Ratio= 0.001
Split Flow NTrial= 30
Split Flow Tol= 0.02
Split Flow Ratio= 0.02
Log Output Level= 0
Friction Slope Method= 1
Unsteady Friction Slope Method= 2
Unsteady Bridges Friction Slope Method= 1
Parabolic Critical Depth
Global Vel Dist= 0 , 0 , 0
Global Log Level= 0
CheckData=True
Encroach Param=-1 ,0,0, 0
Mapping Interval=1HOUR
Computation Time Step Use Courant=        0
Computation Time Step Use Time Series=    0
Computation Time Step Count To Double=0
Computation Time Step Max Doubling=0
Computation Time Step Max Halving=0
Computation Time Step Residence Courant=0
Run HTab= 0
Run UNet= 0
Run Sediment= 0
Run PostProcess= 0
Run WQNet= 0
Run RASMapper= 0
UNET Theta= 0
UNET Theta Warmup= 0
UNET ZTol= 0
UNET ZSATol= 0
UNET MxIter= 0
UNET Max Iter WO Improvement= 0
UNET MaxInSteps= 0
UNET DtIC= 0
UNET DtMin= 0
UNET MaxCRTS= 0
UNET WFStab= 0
UNET SFStab= 0
UNET WFX= 1
UNET SFX= 1
UNET Gravity=32.174
UNET 1D Methodology=Finite Difference
UNET DSS MLevel= 1
UNET Pardiso=0
UNET DZMax Abort= 0
UNET Use Existing IB Tables= 0
UNET Froude Reduction=False
UNET Froude Limit= 0
UNET Froude Power= 0
UNET D1 Cores= 0
UNET WindReference=Eulerian
UNET WindDragFormulation=Hsu (1988)
UNET D2 Coriolis=0
UNET D2 Cores= 0
UNET D2 Theta= 1
UNET D2 Theta Warmup= 1
UNET D2 Z Tol= 0.01
UNET D2 Volume Tol= 0.01
UNET D2 Max Iterations= 20
UNET D2 Equation= 0
UNET D2 RampUpFraction=0.1
UNET D2 TimeSlices= 1
UNET D2 Turbulence Formulation=Non-Conservative (original)
UNET D2 Eddy Viscosity=0.3
UNET D2 Transverse Eddy Viscosity=0.1
UNET D2 Smagorinsky Mixing=0
UNET D2 BCVolumeCheck=0
UNET D2 Cores=0
UNET D2 SolverType=PARDISO (Direct)
UNET D2 Minimum Iterations= 2147483647
UNET D2 Maximum Iterations= 2147483647
UNET D2 Restart Number= 10
UNET D2 Relaxation Coeff=1.3
UNET D2 SOR Precondition Iterations= 10
UNET D2 ILUT Maximum Fill= 8
UNET D2 ILUT Tolerance=1E-08
UNET D1D2 MaxIter= 0
UNET D1D2 ZTol=0.01
UNET D1D2 QTol=0.1
UNET D1D2 MinQTol=1
Write IC File= 0
Write IC File at Fixed DateTime=0
Write IC File at Sim End=0
Echo Input=False
Echo Parameters=False
Echo Output=False
Write Detailed= 0
HDF Write Warmup=0
HDF Write Time Slices=0
HDF Flush=0
HDF Compression= 1
HDF Chunk Size= 1
HDF Spatial Parts= 1
HDF Use Max Rows=0
HDF Fixed Rows= 1
Calibration Method= 0
Calibration Iterations= 20
Calibration Max Change=0.05
Calibration Tolerance=0.2
Calibration Maximum=1.5
Calibration Minimum=0.5
Calibration Optimization Method= 1
WQ AD Non Conservative
WQ ULTIMATE=-1
WQ Max Comp Step=1HOUR
WQ Output Interval=15MIN
WQ Output Selected Increments= 0
WQ Output face flow=0
WQ Output face velocity=0
WQ Output face area=0
WQ Output face dispersion=0
WQ Output cell volume=0
WQ Output cell surface area=0
WQ Output cell continuity=0
WQ Output cumulative cell continuity=0
WQ Output face conc=0
WQ Output face dconc_dx=0
WQ Output face courant=0
WQ Output face peclet=0
WQ Output face adv mass=0
WQ Output face disp mass=0
WQ Output cell mass=0
WQ Output cell source sink temp=0
WQ Output nsm pathways=0
WQ Output nsm derived pathways=0
WQ Create Restart=0
WQ Fixed Restart=0
WQ System Summary=0
WQ Write To DSS=0
Sorting and Armoring Iterations= 10
XS Update Threshold= 0.02
Bed Roughness Predictor= 0
Hydraulics Update Threshold= 0.02
Energy Slope Method= 1
Volume Change Method= 1
Sediment Retention Method= 0
Sediment TS Multiplier= 1
Warm Up Method= 0
XS Weighting Method= 0
Number of US Weighted Cross Sections= 1
Number of DS Weighted Cross Sections= 1
Upstream XS Weight=0
Main XS Weight=1
Downstream XS Weight=0
Number of DS XS's Weighted with US Boundary= 1
Upstream Boundary Weight= 1
Weight of XSs Associated with US Boundary= 0
Number of US XS's Weighted with DS Boundary= 1
Downstream Boundary Weight= 0.5
Weight of XSs Associated with DS Boundary= 0.5
Percentile Method= 0
Sediment Output Level= 3
Mass or Volume Output= 0
Output Increment Type= 1
Profile and TS Output Increment= 1
Transport Output Increment 1
XS Output Flag= 0
XS Output Increment= 10
Read HDF5 Sediment Hotstart= 0
Sediment Hotstart Type= 0
Write Gradation File= 0
Read Gradation Hotstart= 0
Write HDF5 File= 1
Write Binary Output= 1
Write DSS Sediment File= 0
DSS Sediment Output Type= 1
SV Curve= 0
Specific Gage Flag= 0
Subcell Erosion Methods= 0
Subcell Deposition Methods= 0
Advection Scheme= 1
Matrix Solver= 0
Implicit Weighting Factor= 1
Maximum Outer Loop Convergence Iterations= 5
Convergence Maximum Absolute= 0.001
Convergence RMSE= 0.0001
Grain Fractions Max Abs Error= 0.001
Max Subgrid Regions= 1
Max Subgrid Length Scale= 3.402823E+38
Initial Layer Thickness= 3.402823E+38
Min Layer Thickness= 3.402823E+38
Max Layer Thickness= 3.402823E+38
Number of Layers= 5

--- LEADNGCK.f01 (steady flow) ---

Flow Title=Flow
Program Version=6.20
Number of Profiles= 1
Profile Names=P100yr
River Rch & RM=LEADNGCK,Main,76083
     341
River Rch & RM=LEADNGCK,Main,72660
     488
River Rch & RM=LEADNGCK,Main,70650
     622
River Rch & RM=LEADNGCK,Main,66863
     757
River Rch & RM=LEADNGCK,Main,62894
    1140
River Rch & RM=LEADNGCK,Main,60845
    1340
River Rch & RM=LEADNGCK,Main,59217
    1490
River Rch & RM=LEADNGCK,Main,52159
    1840
River Rch & RM=LEADNGCK,Main,49393
    2340
River Rch & RM=LEADNGCK,Main,39810
    3020
River Rch & RM=LEADNGCK,Main,32296
    3670
River Rch & RM=LEADNGCK,Main,24614
    4080
River Rch & RM=LEADNGCK,Main,14520
    4800
River Rch & RM=LEADNGCK,Main,4254
    5500
Boundary for River Rch & Prof#=LEADNGCK,Main            , 1
Up Type= 0
Dn Type= 3
Dn Slope=0.000666
DSS Import GetInterval= 0
DSS Import GetPeak= 0
DSS Import FillOption= 0

--- LEADNGCK.g01 (geometry) ---

Geom Title=Geometry
Program Version=6.20

River Reach=LEADNGCK        ,Main
Reach XY= 30
     2306430.924      766462.466      2306530.75      763437.205
     2305505.958      761206.729     2306370.706       759544.88
     2305865.637      756555.852     2306416.476      753856.872
     2304490.867      751619.194     2304453.974      750654.133
      2302721.77       750026.22     2302505.298      748588.378
     2305068.406      745175.574     2305065.929      742705.752
     2304237.894      741869.151     2304664.468      741358.065
     2303614.862      740437.214     2305200.441      737795.395
     2304179.843      736143.673     2304339.146      734698.723
     2305684.197      733653.039     2303889.373      732788.112
      2303669.67      731866.642     2303018.284      732321.171
     2301546.705      731492.197     2301500.672      730227.455
     2300633.599      729333.777     2300531.976      727021.179
     2299915.728       727326.64     2300186.503      726626.088
     2299402.939      726706.431     2299200.242      724821.625

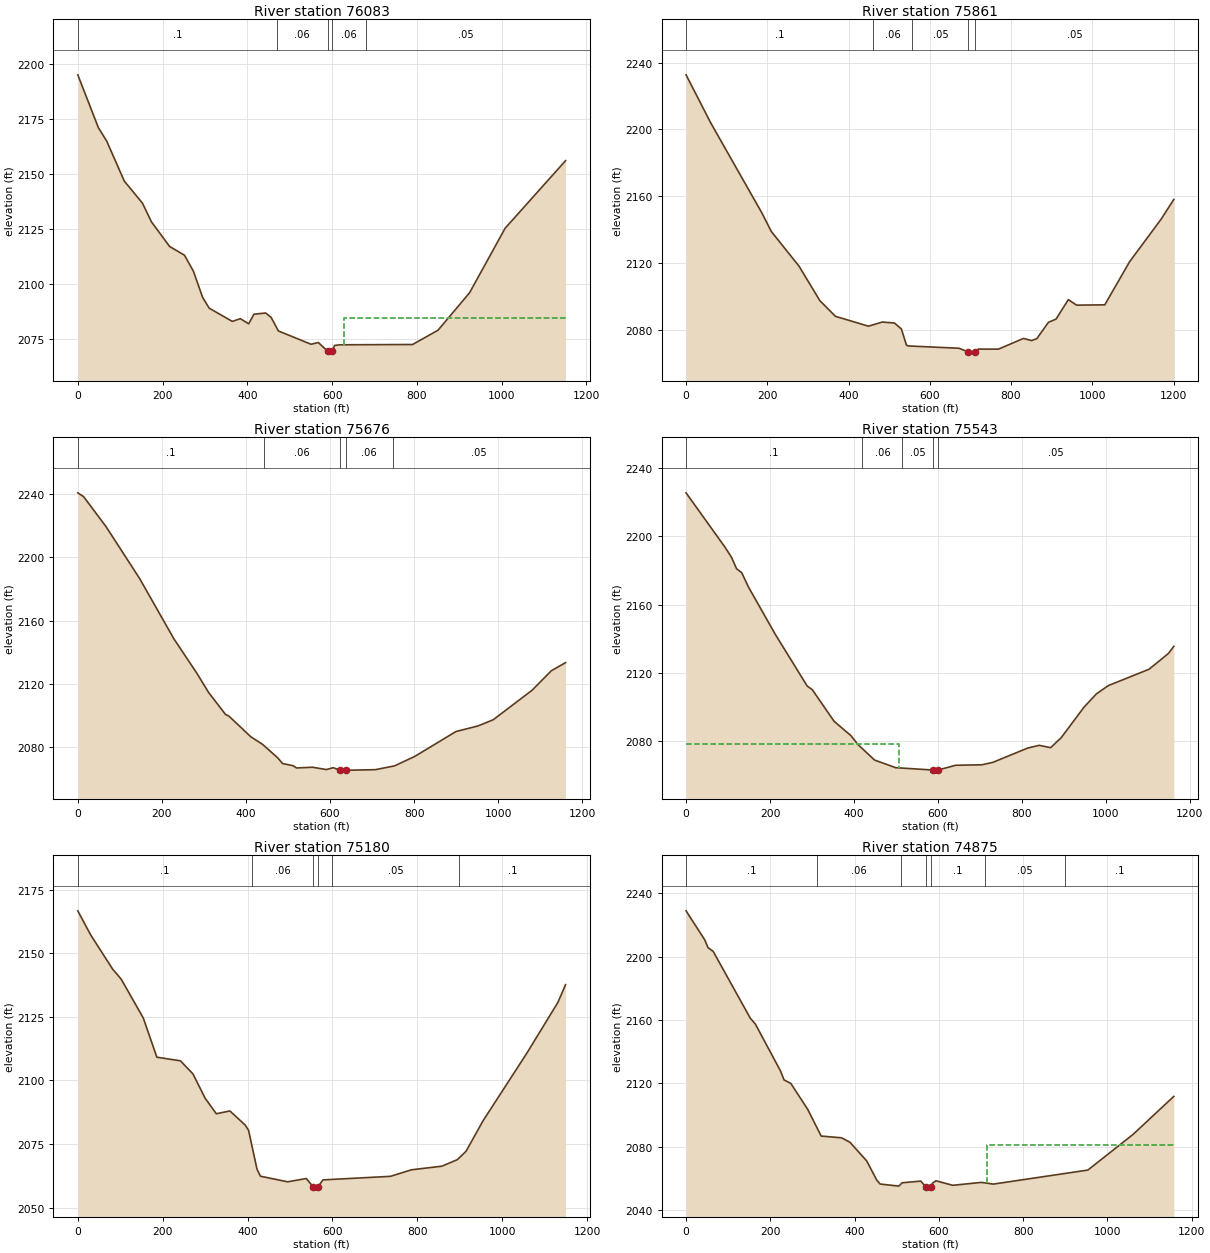
Type RM Length L Ch R = 1 ,76083   ,222.1,222.1,222.1
XS GIS Cut Line= 2
2306974.73774312766231.9683074222305898.76905879766639.811675386
#Sta/Elev= 30
       0 2195.19    48.6 2171.13    68.1 2165.08   109.7 2146.85   152.5 2136.82
   173.8  2128.3   216.6  2117.1   251.7 2113.12   272.8 2105.82   294.5 2093.92
     310 2089.02   364.5    2083   383.5 2084.24   403.1 2081.92   415.5 2086.28
   443.4 2086.82   456.2  2084.8   473.3 2078.65   550.3 2072.61   567.4 2073.41
   589.2 2069.48   597.3 2068.57   599.62069.481   605.9 2072.07   618.7 2072.36
   789.8 2072.49   849.8    2079   924.2 2096.02  1008.1 2125.38  1150.7 2156.14
#Mann= 5 ,-1,0
       0      .1       0     470     .06       0   589.2    .045       0
   599.6     .06       0     680     .05       0
#XS Ineff= 2 , 0
                          627.29         2084.62
Permanent Ineff=
       F       F
Bank Sta=589.2,599.6
XS Rating Curve= 0 ,0
Exp/Cntr(USF)=0,0
Exp/Cntr=0.3,0.1

Type RM Length L Ch R = 1 ,75861   ,185.5,185.5,185.5
XS GIS Cut Line= 4
2306968.48113893766135.3383266592306474.99332799766320.900500797
2306153.62115684766242.9106015222305817.50701861766309.609182453
#Sta/Elev= 30
       0 2232.66    60.7 2203.96   187.1 2149.89   209.8 2139.01   278.1 2118.25
   329.4 2097.62   367.8 2088.24     449 2082.35   483.2 2084.83   513.1 2084.24
   530.1 2080.66   542.5 2071.06   546.6 2070.54   671.8 2069.16   694.9 2066.96
   707.1 2066.24   712.42067.164   719.5 2068.65   768.9 2068.62   830.6 2075.03
   850.6 2073.74   863.5 2074.93     892 2084.66   910.7 2086.58     941 2098.23
   961.3 2094.94  1030.7 2095.12  1091.8  2120.9  1169.3 2146.33  1200.6 2158.14
#Mann= 5 ,-1,0
       0      .1       0     460     .06       0  557.22     .05       0
   694.9    .045       0   712.4     .05       0
Bank Sta=694.9,712.4
XS Rating Curve= 0 ,0
Exp/Cntr(USF)=0,0
Exp/Cntr=0.3,0.1

Type RM Length L Ch R = 1 ,75676   ,132.2,132.2,132.2
XS GIS Cut Line= 5
2306964.44717862  766103.06664422306965.24569162766116.880563236
2306480.87805545 766141.405506842306211.10367581766063.232249104
2305833.26204571 766107.83438171
#Sta/Elev= 30
       0 2240.81    13.8 2238.41      67 2219.52   147.1 2186.67   228.6 2148.58
   283.3 2126.82   311.3 2114.65   351.3 2100.85   359.3 2099.82   411.4 2086.76
   439.5 2081.94   475.5 2073.42   487.1 2069.83   512.1 2068.45   520.4 2067.02
   557.9  2067.5   591.2 2066.02   607.8 2067.21   623.62065.555   628.7 2065.03
     637 2065.56   707.8 2065.95   753.6 2068.36   802.1 2074.41   899.4 2090.03
   951.8 2093.56   988.1 2097.47  1080.7 2116.15  1126.3 2128.42  1160.2 2133.56
#Mann= 5 ,-1,0
       0      .1       0  443.84     .06       0   623.6    .045       0
     637     .06       0  748.83     .05       0
Bank Sta=623.6,637
XS Rating Curve= 0 ,0
Exp/Cntr(USF)=0,0
Exp/Cntr=0.3,0.1

Type RM Length L Ch R = 1 ,75543   ,363.6,363.6,363.6
XS GIS Cut Line= 4
2306956.46391501 766005.950489232306511.53423495766027.977642674
2306264.71042359765948.8602460692305828.01871525 766083.95840834
#Sta/Elev= 30
       0 2225.44    92.4 2193.72   108.4 2187.63   120.4 2180.93   132.5 2178.69
   148.4 2170.38   212.5 2142.54   288.6 2112.22   300.7 2110.09   352.7 2091.54
   392.8 2083.16   408.8 2078.11     449 2068.86   499.4 2064.38   588.1    2063
     596 2062.36   600.2 2063.03   642.2 2065.79   704.7 2066.08   730.4 2067.46
     814  2075.9   841.1 2077.48   868.5 2076.11   893.6 2081.96   948.1 2099.89
   977.8 2107.72  1005.9 2112.48    1103 2122.08  1149.1 2131.33  1161.8 2135.47
#Mann= 5 ,-1,0
       0      .1       0     420     .06       0  515.47     .05       0
   588.1    .045       0   600.2     .05       0
#XS Ineff= 2 , 0
          507.73 2078.31
Permanent Ineff=
       F       F
Bank Sta=588.1,600.2
XS Rating Curve= 0 ,0
Exp/Cntr(USF)=0,0
Exp/Cntr=0.3,0.1

Type RM Length L Ch R = 1 ,75180   ,304.6,304.6,304.6
XS GIS Cut Line= 3
2306946.46943495765701.351775079 2306048.4306851765683.766387266
2305815.40749703765777.474445612
#Sta/Elev= 30
       0 2166.73    30.3 2157.26    82.3 2143.75   102.3 2139.84   154.3 2124.57
   186.3 2109.14   241.8 2107.72   271.5 2102.54   300.1 2092.99   326.4 2086.89
   358.4 2087.99   394.4 2082.46   402.4 2080.37   422.3 2065.08   430.4 2062.31
   494.4 2060.11   538.4  2061.4   554.32058.211   562.4 2057.23   566.4  2058.2
   577.5 2060.86   736.7 2062.26   786.4 2064.84   857.8 2066.25   894.5 2068.83
   914.9 2072.12   954.8 2084.08    1058 2110.68  1131.3 2130.68  1149.4 2137.68
#Mann= 6 ,-1,0
       0      .1       0     410     .06       0   554.3    .045       0
   566.4     .06       0     600     .05       0  898.21      .1       0
Bank Sta=554.3,566.4
XS Rating Curve= 0 ,0
Exp/Cntr(USF)=0,0
Exp/Cntr=0.3,0.1

Type RM Length L Ch R = 1 ,74875   ,210.7,210.7,210.7
XS GIS Cut Line= 3
2306948.41738248765462.1415623242305945.23691556765409.986998704
2305800.85551479765460.421995733
#Sta/Elev= 30
       0  2228.9    44.3 2210.63    52.3 2205.62    64.3 2203.37   152.4 2161.21
   164.5 2157.47   224.5 2127.74   232.6 2122.26   248.6 2120.05   288.6 2103.75
   320.7 2086.84   368.7 2085.75   388.8 2082.98   428.8 2071.14   452.9  2058.9
   460.9 2056.57   504.9 2055.27   512.9 2057.38     557 2058.44   569.6 2054.59
     577 2053.37     581 2054.49     585 2057.16     593 2058.63   633.1 2055.78
   701.2 2057.63   729.2 2056.54   953.5 2065.39  1060.7 2087.85  1157.5 2111.86
#Mann= 7 ,-1,0
       0      .1       0     310     .06       0     510      .1       0
   569.6    .045       0     581      .1       0     710     .05       0
     900      .1       0
#XS Ineff= 2 , 0
                          713.93         2081.38
Permanent Ineff=
       F       F
Bank Sta=569.6,581
XS Rating Curve= 0 ,0
Exp/Cntr(USF)=0,0
Exp/Cntr=0.3,0.1

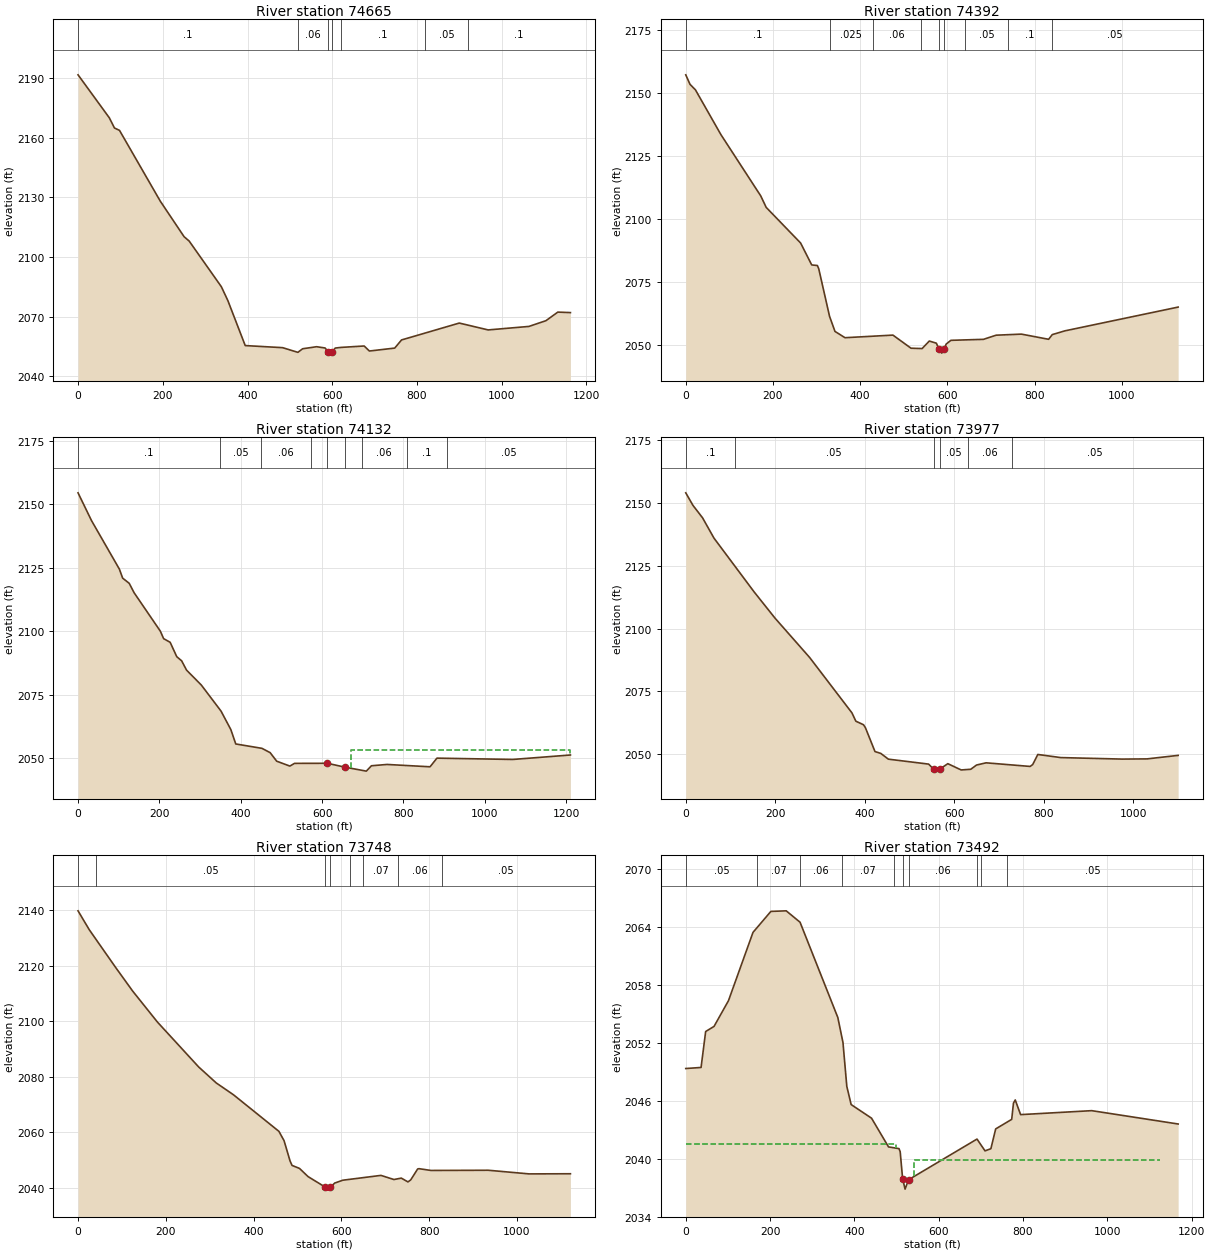
Type RM Length L Ch R = 1 ,74665   ,272.5,272.5,272.5
XS GIS Cut Line= 2
2306961.86391684765268.5114675712305802.53388863765188.998884574
#Sta/Elev= 30
       0 2191.68    73.9 2170.03    85.9 2164.93    97.9 2163.71   194.1  2128.1
   250.3 2110.21   262.3 2108.01   338.3 2085.01   353.7    2078   394.6  2055.4
   482.8 2054.35   518.9 2051.99     530 2053.79     563 2054.83   583.1 2054.18
     590 2052.35   595.1  2051.6   600.32052.365   607.1 2054.15     620 2054.47
   675.3 2055.19   687.6 2052.66   747.4 2054.14   763.5 2058.23   899.8 2066.73
     968 2063.28  1064.2 2065.04  1104.3 2067.93  1132.3 2072.24  1162.1    2072
#Mann= 7 ,-1,0
       0      .1       0     520     .06       0     590    .045       0
   600.3     .06       0     620      .1       0     820     .05       0
     920      .1       0
Bank Sta=590,600.3
XS Rating Curve= 0 ,0
Exp/Cntr(USF)=0,0
Exp/Cntr=0.3,0.1

Type RM Length L Ch R = 1 ,74392   ,260.3,260.3,260.3
XS GIS Cut Line= 3
2306957.82995653765143.4586980432306132.67049696764912.972108701
2305866.84371835764852.393592009
#Sta/Elev= 30
       0  2157.3     9.7 2153.55    22.2 2151.34    80.6 2133.58     172 2109.25
   184.5 2104.69   263.4 2090.56   288.9 2081.85   301.9 2081.62   305.1  2080.3
   329.8 2061.46   342.3 2055.46   365.3 2052.97   475.2    2054   516.7  2048.8
   542.1 2048.66   558.6 2051.64   574.8  2050.8   581.1 2048.37   587.3 2046.85
   592.72048.433   597.3 2050.44   608.1 2051.93   682.8 2052.32   711.9 2053.97
     770 2054.39   832.3 2052.34   840.7  2054.2   869.6 2055.69  1129.4 2065.12
#Mann= 9 ,-1,0
       0      .1       0     330    .025       0     430     .06       0
     540      .1       0   581.1    .045       0   592.7      .1       0
     640     .05       0     740      .1       0     840     .05       0
Bank Sta=581.1,592.7
XS Rating Curve= 0 ,0
Exp/Cntr(USF)=0,0
Exp/Cntr=0.3,0.1

Type RM Length L Ch R = 1 ,74132   ,154.7,154.7,154.7
BEGIN DESCRIPTION:
Structure-- Added IFA to raise bank station above WSE
END DESCRIPTION:
XS GIS Cut Line= 5
2306980.99831378764911.1214547362306452.70569898764845.738705379
2306442.24445909764792.1248509072306446.16742405764680.974177002
2305962.33507881764512.286683663
#Sta/Elev= 30
       0 2154.52    33.1 2143.58   101.6 2124.45   109.7 2120.89   125.8 2118.84
   137.9 2115.12   202.4 2099.97   210.4 2097.03   226.5 2095.59   242.7 2089.92
   254.8 2088.27   266.8 2084.62   303.1 2078.73   351.5 2068.48   375.7 2061.17
   387.8  2055.5   452.2 2053.77   472.3 2052.08   488.5  2048.7   520.8 2046.78
   532.3 2047.85   612.9 2047.88   656.32046.351   708.8 2044.79   721.3  2046.9
   759.6 2047.42   865.5  2046.5   882.4 2049.91  1068.8 2049.39  1210.6 2051.15
#Mann= 9 ,-1,0
       0      .1       0     350     .05       0     450     .06       0
  572.32      .1       0   612.9    .045       0   656.3      .1       0
  696.95     .06       0  808.17      .1       0  908.17     .05       0
#XS Ineff= 2 , 0
                          670.18         2053.24
Permanent Ineff=
       F       F
Bank Sta=612.9,656.3
XS Rating Curve= 0 ,0
Exp/Cntr(USF)=0,0
Exp/Cntr=0.3,0.1

Type RM Length L Ch R = 1 ,73977   ,229.5,229.5,229.5
XS GIS Cut Line= 2
2307027.26780788764815.5772068152305999.25128639764422.353348204
#Sta/Elev= 30
       0 2154.11    16.2 2149.08    37.6 2144.13    63.1 2136.04   152.9 2114.58
   199.4 2104.16   276.9 2088.45   371.6 2066.33   380.2 2063.04   397.3 2061.62
   401.6 2060.45     423 2050.92   435.9 2050.19     453 2047.89   542.9 2045.92
   553.92043.935   560.1 2043.12   568.6    2044   585.8 2046.09   615.7 2043.59
   637.1 2043.86     650 2045.55   671.4 2046.43   769.9 2044.99   775.6 2045.75
     787 2049.76   838.4 2048.52   975.5 2047.92  1031.1    2048  1100.7  2049.4
#Mann= 6 ,-1,0
       0      .1       0     110     .05       0   553.9    .045       0
   568.6     .05       0     630     .06       0     730     .05       0
Bank Sta=553.9,568.6
XS Rating Curve= 0 ,0
Exp/Cntr(USF)=0,0
Exp/Cntr=0.3,0.1

Type RM Length L Ch R = 1 ,73748   ,256,256,256
BEGIN DESCRIPTION:
Structure XS 4
END DESCRIPTION:
XS GIS Cut Line= 3
2307066.45509998764710.5081805582306695.58662705764440.568304168
2306066.89726746764229.691249947
#Sta/Elev= 30
       0 2139.78    25.5 2132.99    85.6 2119.39   124.6 2110.83   180.9 2099.69
   274.9  2083.5   314.9 2077.75   354.1 2073.49   457.7  2060.3   469.4 2056.94
     483 2049.64   487.6 2048.02   504.5 2046.95   524.1 2043.99   563.6 2040.17
   567.8 2039.48   574.72040.153   584.7 2041.66   603.1 2042.69   690.1 2044.43
   719.7 2042.94   736.5 2043.45   751.6 2042.08   757.9  2042.8   773.7 2046.73
   776.8 2046.85     804 2046.21   934.8 2046.28  1027.7 2044.97  1121.8 2045.02
#Mann= 8 ,-1,0
       0      .1       0      40     .05       0   563.6    .045       0
   574.7     .05       0  618.71     .06       0  648.71     .07       0
  728.71     .06       0  828.71     .05       0
Bank Sta=563.6,574.7
XS Rating Curve= 0 ,0
Exp/Cntr(USF)=0,0
Exp/Cntr=0.5,0.3

Type RM Length L Ch R = 1 ,73492   ,50.5,50.5,50.5
BEGIN DESCRIPTION:
Structure XS 3 14.9ft
END DESCRIPTION:
XS GIS Cut Line= 4
2307098.54838294763997.1478170752306711.48250675764070.376496354
2306506.18067378764284.8319142432306053.80165123764133.435072963
#Sta/Elev= 30
       0 2049.33    36.3 2049.44    47.2 2053.16    67.1 2053.69   101.3 2056.35
   159.5 2063.42   201.9 2065.59   238.3 2065.65   271.1 2064.47   360.7 2054.61
   372.9 2052.02     382 2047.48   392.3  2045.6   440.7 2044.19   480.9 2041.22
   505.8 2041.04   508.6 2040.72   514.4 2037.92   520.2 2036.85   528.4 2037.82
   690.8 2042.03   709.8 2040.81   723.7 2041.03   735.1 2043.08   773.1 2044.07
   777.3 2045.75   781.5 2046.08   794.2 2044.56   962.9 2044.97  1167.9 2043.59
#Mann= 10 ,-1,0
       0     .05       0     170     .07       0     270     .06       0
     370     .07       0  493.93     .06       0   514.4    .045       0
   528.4     .06       0  690.82     .07       0  700.82     .06       0
  760.82     .05       0
#XS Ineff= 2 ,-1
       0   499.5 2041.57   542.3  1125.9 2039.84
Permanent Ineff=
       F       F
Bank Sta=514.4,528.4
XS Rating Curve= 0 ,0
Exp/Cntr(USF)=0,0
Exp/Cntr=0.5,0.3

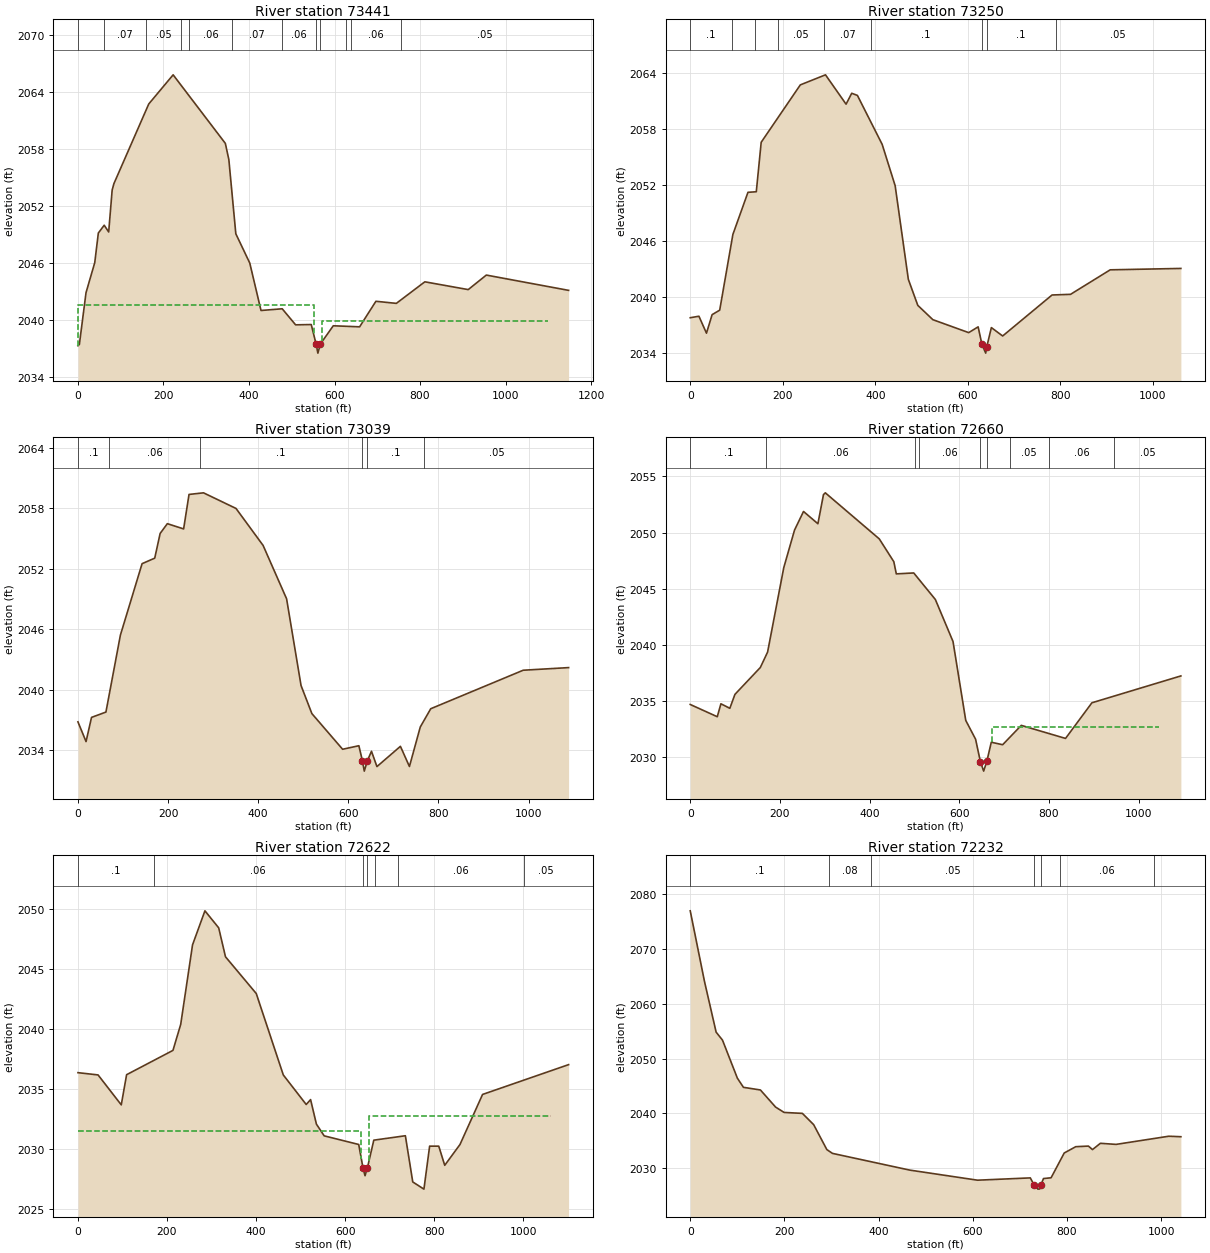
Type RM Length L Ch R = 1 ,73441   ,191,191,191
BEGIN DESCRIPTION:
Structure XS 2 14.9fft 4.97
END DESCRIPTION:
XS GIS Cut Line= 4
2307090.78104584763943.9151223962306690.04619003764020.561046581
2306484.74435706 764235.016464472306066.21591345764091.390667413
#Sta/Elev= 30
       0 2037.25     3.3 2037.38    18.9 2042.84    39.3    2046    47.7 2049.12
    61.4 2049.94    71.9 2049.23      80 2053.64    84.1 2054.32   165.6 2062.71
   222.6 2065.78   344.7 2058.56   352.9 2056.85   369.2 2049.04   401.8 2045.96
   428.1 2040.96   477.7 2041.14     509 2039.45   545.6 2039.48   556.9 2037.43
   561.1 2036.47   566.92037.428   597.1 2039.35   658.7 2039.24   696.8 2041.93
   744.6 2041.71   811.2 2043.98   912.7 2043.16     955 2044.69  1147.4 2043.08
#Mann= 12 ,-1,0
       0     .06       0      60     .07       0     160     .05       0
     240     .07       0     260     .06       0     360     .07       0
     478     .06       0   556.9    .045       0   566.9     .06       0
     628     .05       0     638     .06       0  754.88     .05       0
#XS Ineff= 2 ,-1
       0  551.93 2041.57  571.87  1098.6 2039.84
Permanent Ineff=
       F       F
Bank Sta=556.9,566.9
XS Rating Curve= 0 ,0
Exp/Cntr(USF)=0,0
Exp/Cntr=0.5,0.3

Type RM Length L Ch R = 1 ,73250   ,210.7,210.7,210.7
BEGIN DESCRIPTION:
Structure XS 1
END DESCRIPTION:
XS GIS Cut Line= 2
2307118.60405629 763863.718264412306078.34326019764070.762464195
#Sta/Elev= 30
       0 2037.76    18.8 2037.92    35.1  2036.1    47.3 2038.09    63.7 2038.57
    92.2  2046.7   124.8 2051.22   142.8 2051.28   153.4 2056.59     238 2062.75
   292.4 2063.83   336.9 2060.68   349.1 2061.85   361.4 2061.62   414.9 2056.37
     443 2051.93   471.5 2041.88   491.9 2039.09   524.5 2037.55     602 2036.16
   622.4 2036.78   630.32034.969   638.7 2033.96   640.8 2034.59     651  2036.7
   675.4  2035.8   782.2  2040.2   822.2 2040.27   907.9  2042.9  1060.7 2043.05
#Mann= 9 ,-1,0
       0      .1       0      90     .06       0     140     .07       0
     190     .05       0     290     .07       0     390      .1       0
   630.3    .045       0   640.8      .1       0     790     .05       0
Bank Sta=630.3,640.8
XS Rating Curve= 0 ,0
Exp/Cntr(USF)=0,0
Exp/Cntr=0.3,0.1

Type RM Length L Ch R = 1 ,73039   ,379,379,379
BEGIN DESCRIPTION:
Structure XS 4
END DESCRIPTION:
XS GIS Cut Line= 3
2307106.18084839 763842.829710572306339.63592697763791.946363375
2306101.31989711764006.310495842
#Sta/Elev= 30
       0 2036.82      18 2034.86    30.1 2037.26    62.1 2037.79    94.2 2045.42
   142.3 2052.51   170.4 2053.06   182.4 2055.51   198.4 2056.48   234.5 2055.96
   246.5 2059.38   278.6 2059.54   350.8 2057.99   410.9 2054.32     463 2049.03
   495.1 2040.42   519.1 2037.64   587.3  2034.1   623.4 2034.45   631.4 2032.93
   635.4 2031.93   642.42032.972   651.4  2033.9   663.5 2032.38   715.6 2034.39
   735.6 2032.39   759.7 2036.31   782.9 2038.12   988.1 2041.94  1088.8  2042.2
#Mann= 6 ,-1,0
       0      .1       0      70     .06       0     270      .1       0
   631.4    .045       0   642.4      .1       0  768.23     .05       0
Bank Sta=631.4,642.4
XS Rating Curve= 0 ,0
Exp/Cntr(USF)=0,0
Exp/Cntr=0.5,0.3

Type RM Length L Ch R = 1 ,72660   ,38.6,38.6,38.6
BEGIN DESCRIPTION:
Structure XS 3 11.1ft
END DESCRIPTION:
XS GIS Cut Line= 6
2307100.42540772763696.4186641062306802.01654029763712.875713912
2306675.06367913763613.372120032 2306546.9670985763556.186146538
2306277.04930361763466.9760278862306104.13896658763584.745076317
#Sta/Elev= 30
       0  2034.7    60.3 2033.61    68.4 2034.76    88.3 2034.36    99.7  2035.6
   156.3 2037.99   172.5 2039.36   208.6 2046.88   232.6 2050.22   252.6 2051.87
   284.7 2050.78   297.1 2053.37   301.2 2053.53   421.6 2049.43     454  2047.4
   459.5 2046.32   498.4  2046.4   546.6 2044.04     586  2040.3   614.4 2033.28
   636.3 2031.61   647.12029.601   654.3 2028.77   661.4 2029.64   671.3 2031.34
   696.7 2031.12   738.2 2032.84   836.9 2031.68   895.7 2034.85  1094.1 2037.24
#Mann= 9 ,-1,0
       0      .1       0     170     .06       0  500.16      .1       0
  510.16     .06       0   647.1    .045       0   661.4     .06       0
  712.69     .05       0  799.26     .06       0  944.89     .05       0
#XS Ineff= 2 ,-1
       0  636.04 2031.45   672.5  1044.2 2032.69
Permanent Ineff=
       F       F
Bank Sta=647.1,661.4
XS Rating Curve= 0 ,0
Exp/Cntr(USF)=0,0
Exp/Cntr=0.5,0.3

Type RM Length L Ch R = 1 ,72622   ,389.6,389.6,389.6
BEGIN DESCRIPTION:
Structure XS 2 10.4ft 3.47
END DESCRIPTION:
XS GIS Cut Line= 6
2307105.31717861 763663.863320752306820.52879156763678.685912911
 2306693.5759304763579.1823190312306565.47934977763521.996345537
2306295.56155488763432.7862268852306100.24184242763555.674011069
#Sta/Elev= 30
       0 2036.35    45.2 2036.16    97.3 2033.66   109.3 2036.18   213.4 2038.21
   230.8 2040.38   257.4 2047.03   285.2 2049.87   316.1 2048.45   331.4 2046.03
   400.5 2042.96   461.2 2036.16   512.7 2033.69   522.5  2034.1   535.6 2032.05
   553.1 2031.07   630.6 2030.35   640.2  2028.4   644.8 2027.74   650.22028.408
   664.5 2030.71   735.4 2031.08     752 2027.22   777.1 2026.62   789.9 2030.21
   810.4 2030.21   823.8 2028.61   858.1 2030.35   908.8 2034.53    1102 2037.02
#Mann= 7 ,-1,0
       0      .1       0     170     .06       0   640.2    .045       0
   650.2     .06       0  666.76     .05       0     719     .06       0
  1001.2     .05       0
#XS Ineff= 2 ,-1
       0  636.73 2031.45  653.68  1062.7 2032.69
Permanent Ineff=
       F       F
Bank Sta=640.2,650.2
XS Rating Curve= 0 ,0
Exp/Cntr(USF)=0,0
Exp/Cntr=0.5,0.3

Type RM Length L Ch R = 1 ,72232   ,175.5,175.5,175.5
BEGIN DESCRIPTION:
Structure XS 1
END DESCRIPTION:
XS GIS Cut Line= 4
2307000.99268503763253.0933621912306801.86269321763356.536108154
2306130.98379625763352.2493420392306009.70965252763434.414007882
#Sta/Elev= 30
       0 2076.96    30.3 2064.06      55 2054.82    68.5 2053.37   100.1 2046.43
     113 2044.76     149 2044.28   181.2 2041.16   199.3 2040.18   238.1 2040.01
   262.1 2037.95   290.1  2033.4   302.1 2032.71   466.1 2029.66   610.1 2027.82
   722.1 2028.24   730.2 2026.93   738.2 2026.19   742.1 2026.22   744.5 2026.95
   750.1 2028.12   766.2 2028.26   794.1 2032.78   818.5 2033.93   845.5 2034.04
   854.1  2033.4   870.9 2034.55   904.1 2034.35  1016.1 2035.84  1041.8 2035.75
#Mann= 7 ,-1,0
       0      .1       0   294.4     .08       0   384.4     .05       0
   730.2    .045       0   744.5     .05       0   784.4     .06       0
  985.29     .05       0
Bank Sta=730.2,744.5
XS Rating Curve= 0 ,0
Exp/Cntr(USF)=0,0
Exp/Cntr=0.3,0.1

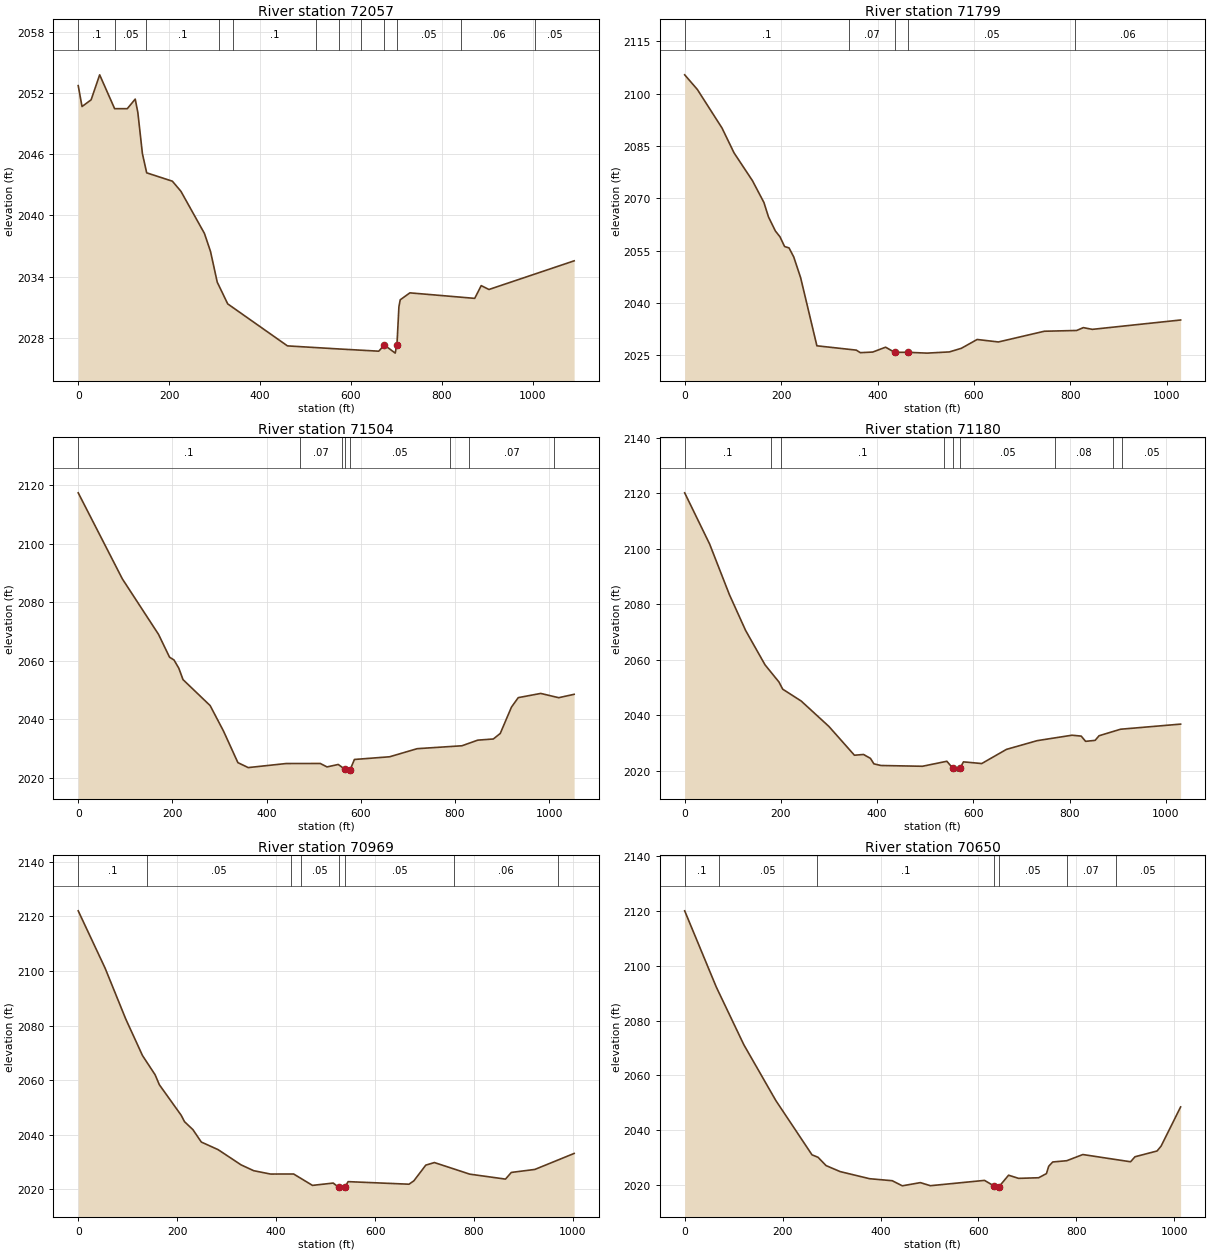
Type RM Length L Ch R = 1 ,72057   ,257.6,257.6,257.6
XS GIS Cut Line= 6
2306904.33033274763024.7810968992306587.25773245763220.668881371
2306159.54868314763178.9549705262306102.33883438763221.971674759
2305946.65285332763350.1059589822305935.83929207763360.723915288
#Sta/Elev= 30
       0 2052.73     8.4 2050.68    28.4 2051.34    47.2 2053.79    80.1 2050.47
   107.9 2050.47   125.4 2051.41   131.2 2050.09   141.2 2046.06   150.6 2044.18
   207.1 2043.36   225.9 2042.37   277.6 2038.24     291 2036.47   305.8 2033.46
   328.8 2031.33   460.2 2027.21   572.7 2026.91   661.1 2026.69   673.2  2027.3
   697.3  2026.5   700.3 2027.26   701.3 2027.51   705.4 2031.06   708.3 2031.73
   729.5 2032.41   872.1 2031.87   886.4 2033.12   903.4 2032.74  1090.8 2035.55
#Mann= 12 ,-1,0
       0      .1       0      80     .05       0     150      .1       0
     310     .05       0     340      .1       0   522.7     .05       0
   572.7     .07       0   622.7     .05       0   673.2    .045       0
   700.3     .05       0  842.44     .06       0 1004.02     .05       0
Bank Sta=673.2,700.3
XS Rating Curve= 0 ,0
Exp/Cntr(USF)=0,0
Exp/Cntr=0.3,0.1

Type RM Length L Ch R = 1 ,71799   ,295,295,295
XS GIS Cut Line= 2
2306730.18941247762716.0088264592305866.31108859763274.215786338
#Sta/Elev= 30
       0 2105.38    26.2  2101.2    77.5 2090.12   102.4 2083.01   140.5 2075.06
   164.3 2068.81   173.8 2064.67   188.1 2060.63   197.7 2058.95   207.2 2056.18
   216.4 2055.78   226.2 2053.19   240.5 2047.23   274.2 2027.73   355.9 2026.49
   364.3 2025.76     390 2025.94   416.7 2027.33   435.42025.856   462.4 2025.87
   502.5 2025.63   549.1 2025.98   573.9 2027.02   606.5 2029.54   650.7 2028.83
   745.8  2031.9   812.9 2032.12   826.8 2032.94   845.3 2032.44  1028.5 2035.12
#Mann= 5 ,-1,0
       0      .1       0     340     .07       0   435.4    .045       0
   462.4     .05       0     810     .06       0
Bank Sta=435.4,462.4
XS Rating Curve= 0 ,0
Exp/Cntr(USF)=0,0
Exp/Cntr=0.3,0.1

Type RM Length L Ch R = 1 ,71504   ,324,324,324
XS GIS Cut Line= 2
2306614.54921699762551.9611072932305732.69843632763127.311529011
#Sta/Elev= 30
       0 2117.44    93.6 2088.02   170.6 2068.98   193.9 2061.19   203.4 2060.23
   213.6 2057.41   222.5 2053.52   280.1 2044.63   308.5  2035.9     339 2025.11
   360.9 2023.41   441.5  2024.8   513.9 2024.82   528.2 2023.64   552.1 2024.48
   566.12022.847   573.2  2022.2   577.42022.723   586.4 2026.19   661.1 2027.11
   719.6 2029.88   814.8 2030.88   848.2  2032.8   881.3  2033.2     896 2035.09
   919.8  2044.1   934.2 2047.35   981.9 2048.79  1020.1 2047.33  1052.9 2048.49
#Mann= 8 ,-1,0
       0      .1       0     470     .07       0     560     .05       0
   566.1    .045       0   577.4     .05       0     790     .06       0
     830     .07       0    1010     .05       0
Bank Sta=566.1,577.4
XS Rating Curve= 0 ,0
Exp/Cntr(USF)=0,0
Exp/Cntr=0.3,0.1

Type RM Length L Ch R = 1 ,71180   ,210.7,210.7,210.7
XS GIS Cut Line= 2
2306493.53040777762402.7045759212305636.38900056762975.365690767
#Sta/Elev= 30
       0 2120.22    51.8 2101.79      93 2083.52   126.7 2070.61   167.1 2058.21
     196 2052.04   203.7 2049.47   242.2 2045.19   299.7 2036.05   352.8 2025.66
   371.7 2025.93   386.1 2024.53   393.3 2022.55   407.7 2021.96   494.1 2021.68
   544.9 2023.48     5572021.053     568 2019.93   572.62021.126   579.5 2023.27
   617.4 2022.66   668.9 2027.77   732.8 2030.92     805 2032.87   824.2 2032.55
   833.3 2030.66   853.1 2031.02   861.3 2032.68     906 2035.03  1030.8 2036.87
#Mann= 9 ,-1,0
       0      .1       0     180     .05       0     200      .1       0
     540     .05       0     557    .045       0   572.6     .05       0
     770     .08       0     890     .07       0     910     .05       0
Bank Sta=557,572.6
XS Rating Curve= 0 ,0
Exp/Cntr(USF)=0,0
Exp/Cntr=0.3,0.1

Type RM Length L Ch R = 1 ,70969   ,319.6,319.6,319.6
XS GIS Cut Line= 2
2306470.84384721762370.4938386242305525.36891271762703.341342486
#Sta/Elev= 30
       0 2121.99    54.4 2100.99    96.1 2082.38     130 2068.98   155.5 2061.95
     164 2058.32   208.1 2047.15   214.9 2044.78   231.8 2041.89   248.8 2037.34
   282.7 2034.56   329.4 2028.96   354.8 2026.84   388.7 2025.62   435.4 2025.64
   473.5 2021.47   515.4 2022.32   526.1 2020.81   532.9  2020.1   538.72020.785
   545.6 2022.84   668.6  2021.9   678.5 2023.15   702.5 2028.88   719.9 2029.83
   791.5 2025.58   863.6 2023.77   875.4 2026.21     923 2027.31  1002.4 2033.17
#Mann= 8 ,-1,0
       0      .1       0     140     .05       0     430      .1       0
     450     .05       0   526.1    .045       0   538.7     .05       0
     760     .06       0     970     .05       0
Bank Sta=526.1,538.7
XS Rating Curve= 0 ,0
Exp/Cntr(USF)=0,0
Exp/Cntr=0.3,0.1

Type RM Length L Ch R = 1 ,70650   ,262,262,262
XS GIS Cut Line= 2
2306414.06959103762276.3680981192305425.20384704762496.057913634
#Sta/Elev= 30
       0 2120.02    64.6  2092.2   120.8 2071.17   186.3 2050.77   260.1 2030.98
   272.4 2030.09   288.8 2027.06   317.5 2024.87   377.8 2022.27     424 2021.54
   444.5 2019.68   481.4 2020.84   501.9 2019.72   612.5 2021.66   632.52019.544
   637.1 2018.47     6422019.367   661.6 2023.55   682.1  2022.4     723 2022.62
   738.9 2024.13   743.6 2026.83   751.8 2028.38   780.5 2028.84   813.3 2031.09
   910.8 2028.45   919.8 2030.28   964.9 2032.39   973.1 2034.16    1013 2048.46
#Mann= 7 ,-1,0
       0      .1       0      70     .05       0     270      .1       0
   632.5    .045       0     642     .05       0     780     .07       0
     880     .05       0
Bank Sta=632.5,642
XS Rating Curve= 0 ,0
Exp/Cntr(USF)=0,0
Exp/Cntr=0.3,0.1