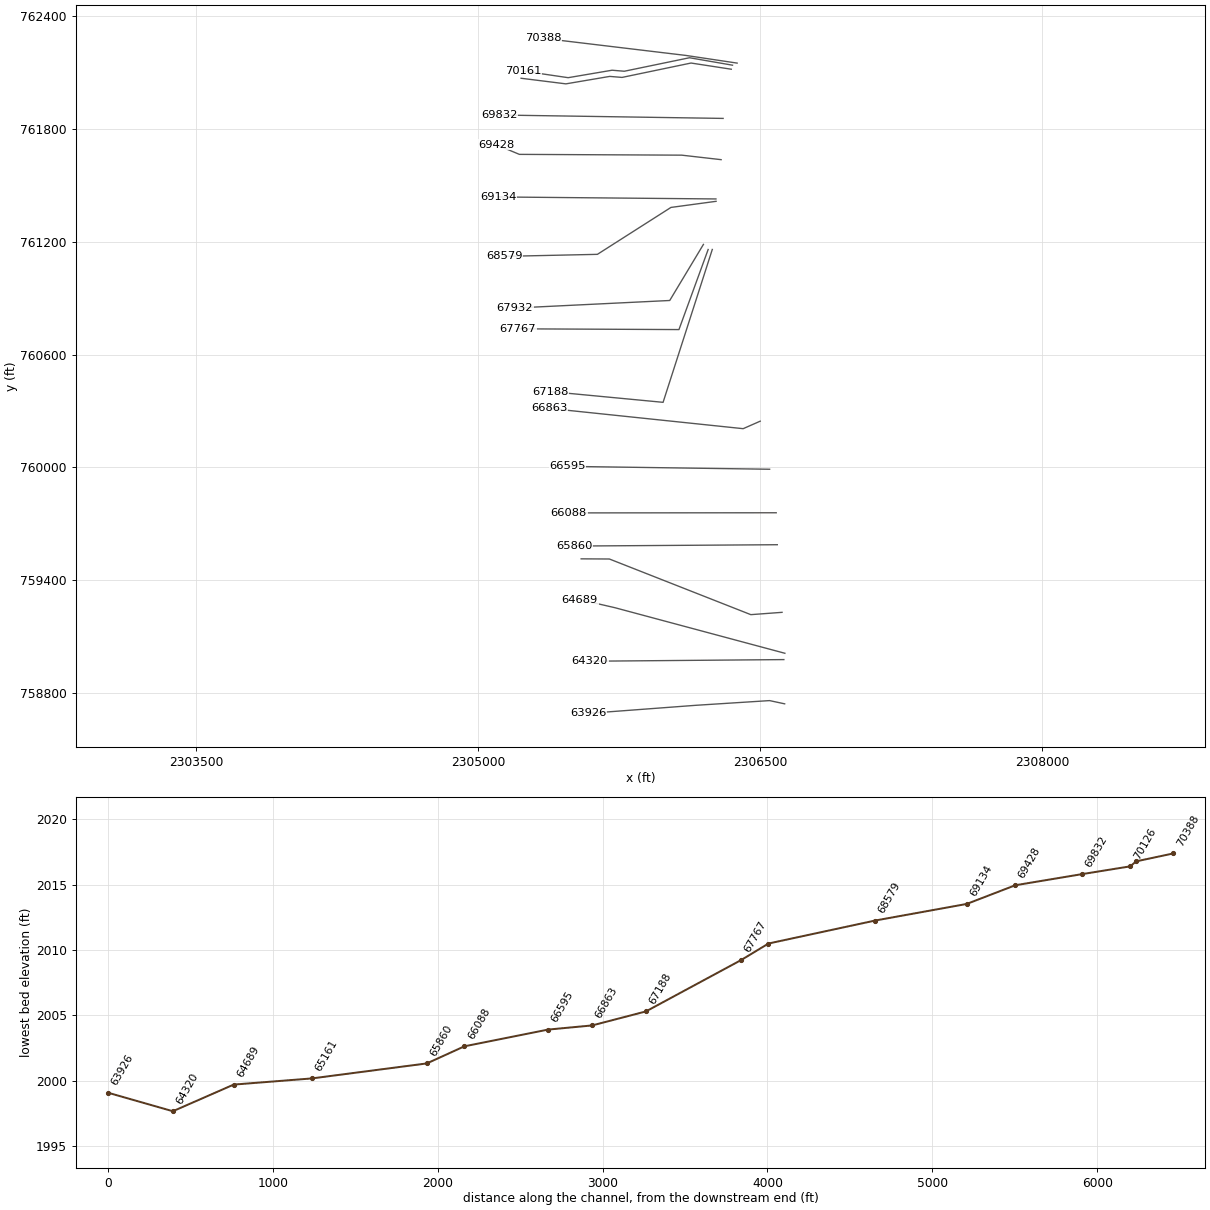
HEC-RAS study LEADNGCK.prj: LEADNGCK

--- LEADNGCK.g01 (geometry) --- (continued)

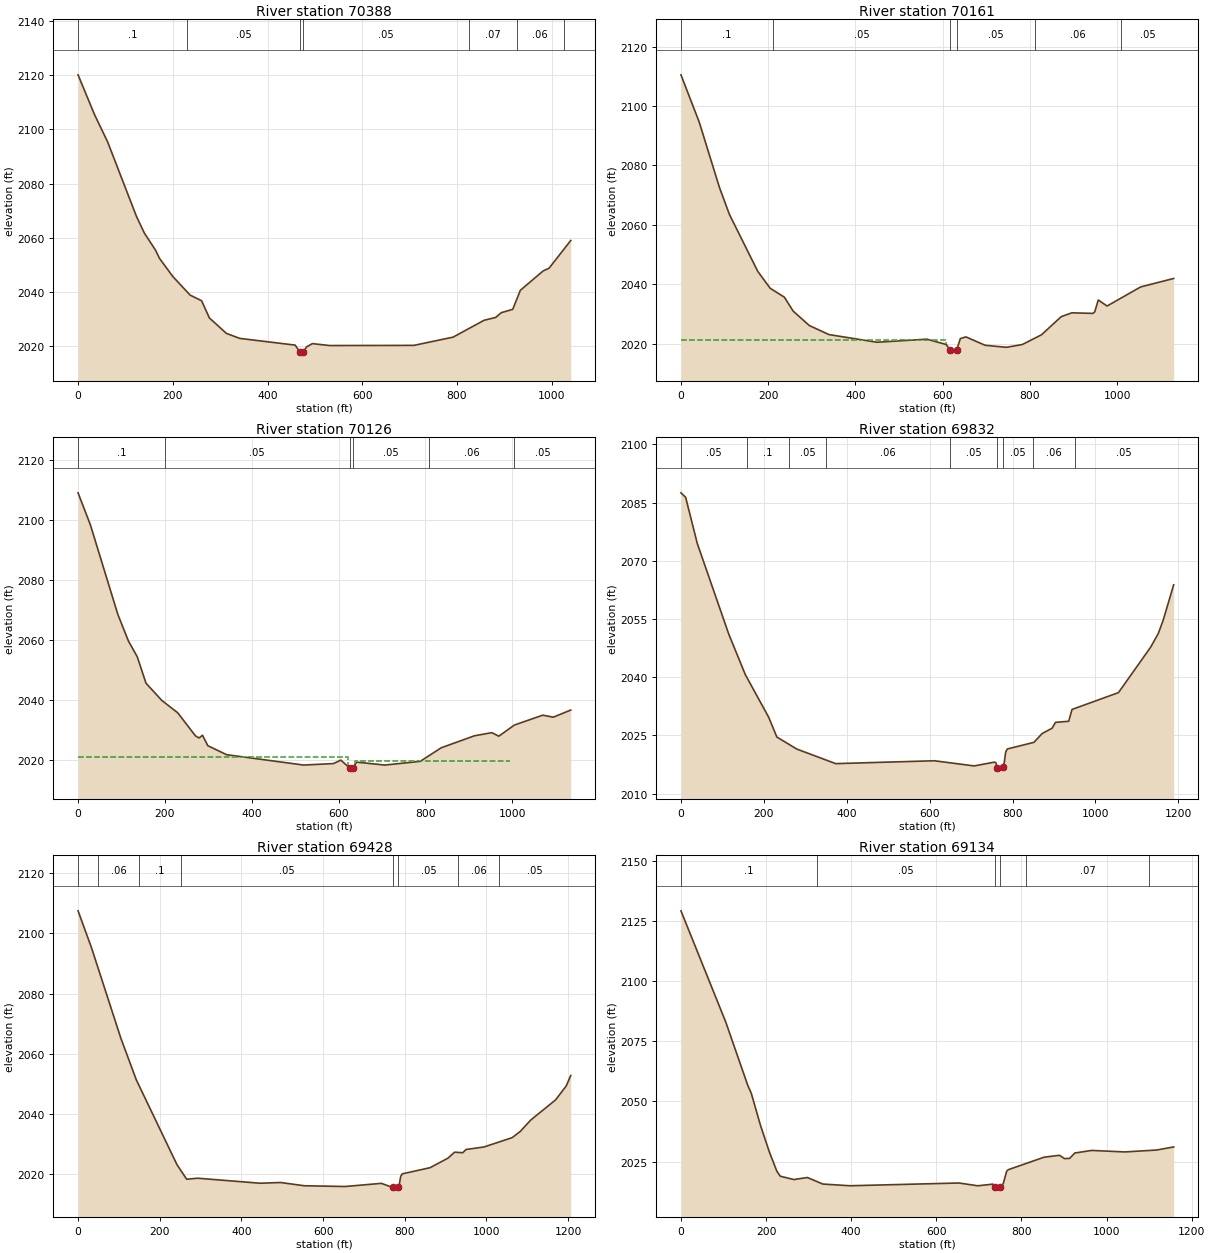
Type RM Length L Ch R = 1 ,70388   ,226.5,226.5,226.5
BEGIN DESCRIPTION:
Structure XS 4
END DESCRIPTION:
XS GIS Cut Line= 3
2306378.05364543762151.9502103932306105.40441548762192.759331886
2305346.57516104762283.759759155
#Sta/Elev= 30
       0 2120.13    34.3 2105.64    62.6 2095.31   123.2 2067.91   139.9 2061.74
   163.7 2055.36   171.8 2052.41   200.1 2045.68   236.5 2038.83   260.8 2036.72
   277.2  2030.4   313.1 2024.69   341.4 2022.84   458.2 2020.36   467.82017.956
   470.3  2017.4   475.62017.974   482.6 2019.72   494.5 2020.91   530.7  2020.2
   708.8 2020.26   791.6  2023.3   857.1 2029.53   881.5 2030.57   893.3 2032.34
   917.5 2033.56   933.6 2040.59   981.9 2047.77     994 2048.71    1040 2058.98
#Mann= 7 ,-1,0
       0      .1       0     230     .05       0   467.8    .045       0
   475.6     .05       0  825.69     .07       0  925.69     .06       0
 1025.69     .05       0
Bank Sta=467.8,475.6
XS Rating Curve= 0 ,0
Exp/Cntr(USF)=0,0
Exp/Cntr=0.5,0.3

Type RM Length L Ch R = 1 ,70161   ,35.1,35.1,35.1
BEGIN DESCRIPTION:
Structure XS 3 11ft
END DESCRIPTION:
XS GIS Cut Line= 6
 2306353.5265121762140.7990322832306124.70779318762180.473245644
2305777.89888639762108.6509249322305712.65510385762114.031855451
2305479.25724259762074.347492873 2305241.2675932 762109.35654055
#Sta/Elev= 30
       0 2110.51      42 2094.53      88 2072.67     111 2063.52   175.9 2044.35
   204.4 2038.64   236.9 2035.64   257.3 2030.92   294.1 2026.09     339 2023.04
   449.3 2020.45   563.7 2021.49   608.2 2019.68   617.3 2017.69   620.2 2016.79
   631.5 2017.69   640.3 2021.68     653 2022.26     697 2019.44   745.7 2018.75
   782.2 2019.68   826.4 2022.98   871.5 2029.07   895.8 2030.36   944.3 2030.17
   948.3  2030.7   956.4 2034.68   976.6 2032.65  1053.5 2039.08  1129.2 2041.93
#Mann= 6 ,-1,0
       0      .1       0     210     .05       0   617.3    .045       0
   631.5     .05       0  811.87     .06       0 1008.61     .05       0
#XS Ineff= 2 ,-1
       0  606.29 2021.16   642.5   986.5 2019.84
Permanent Ineff=
       F       F
Bank Sta=617.3,631.5
XS Rating Curve= 0 ,0
Exp/Cntr(USF)=0,0
Exp/Cntr=0.5,0.3

Type RM Length L Ch R = 1 ,70126   ,294.5,294.5,294.5
BEGIN DESCRIPTION:
Structure XS 2 13.8ft 4.6
END DESCRIPTION:
XS GIS Cut Line= 6
2306346.86631886762119.3491226972306132.84515888762152.297172909
2305765.85776265762075.7665379932305700.61398009762081.147468512
2305467.21611883762041.4631059342305228.93881686762071.259240941
#Sta/Elev= 30
       0 2109.03    28.5 2098.34    91.6 2068.58     116 2059.72   136.3 2054.49
   156.5 2045.67   192.9 2039.94   229.5 2035.84   270.3 2028.16   278.5 2027.45
   286.7 2028.34   298.9 2024.87   342.4 2021.87   519.6 2018.43   588.3 2018.92
   605.2 2020.08   625.2 2017.47   629.2 2016.41   633.82017.583   641.3 2019.41
   706.5 2018.43     788 2019.66   836.4 2024.18   912.9 2028.17   952.9 2029.21
     969 2028.04  1005.1 2031.76  1070.2 2035.03  1094.5 2034.37  1134.7 2036.74
#Mann= 6 ,-1,0
       0      .1       0     200     .05       0   625.2    .045       0
   633.8     .05       0  808.12     .06       0 1003.85     .05       0
#XS Ineff= 2 ,-1
       0   620.6 2021.16  638.42   995.6 2019.84
Permanent Ineff=
       F       F
Bank Sta=625.2,633.8
XS Rating Curve= 0 ,0
Exp/Cntr(USF)=0,0
Exp/Cntr=0.5,0.3

Type RM Length L Ch R = 1 ,69832   ,403.6,403.6,403.6
BEGIN DESCRIPTION:
Structure XS 1
END DESCRIPTION:
XS GIS Cut Line= 2
2306303.44832833761857.5721887332305115.01819825761875.615789955
#Sta/Elev= 30
       0  2087.5    11.3 2086.35    39.3 2074.48   115.3 2051.11   155.3 2040.66
   211.7 2029.68   231.3  2024.6   279.3  2021.5   373.3 2017.74   611.3 2018.48
   707.4 2017.15   755.5 2018.12   759.3 2018.03   763.4 2016.72   767.4 2015.81
   776.62016.779   779.4 2017.64   783.4 2020.75   787.4 2021.52   851.4 2023.22
   871.4  2025.5   895.4 2026.87   903.4 2028.37   935.4 2028.65   943.4  2031.7
  1055.4 2036.03    1133 2047.73  1151.4 2051.23  1163.4 2054.72  1188.6  2063.8
#Mann= 9 ,-1,0
       0     .05       0     160      .1       0     260     .05       0
     350     .06       0     650     .05       0   763.4    .045       0
   776.6     .05       0     850     .06       0     950     .05       0
Bank Sta=763.4,776.6
XS Rating Curve= 0 ,0
Exp/Cntr(USF)=0,0
Exp/Cntr=0.3,0.1

Type RM Length L Ch R = 1 ,69428   ,294.1,294.1,294.1
XS GIS Cut Line= 4
2306292.83178247761638.020390061  2306083.191124761661.986956538
2305219.84302034761666.1564779482305097.96854695761717.102789067
#Sta/Elev= 30
       0 2107.52    32.9 2095.27   104.6 2065.23   142.6 2051.33     242 2023.16
     266 2018.25   292.8 2018.59     446 2016.92   496.2 2017.16     554 2016.08
     654 2015.83   742.7 2016.88     7702015.531   781.6 2014.96   784.62015.561
     786 2015.91     790 2019.17     794 2020.04     862 2022.09     906 2025.28
     922 2027.25     942 2027.07     950 2028.14     994 2028.98    1063 2032.08
  1082.7 2034.13  1108.7 2037.96  1169.4 2044.65  1195.4 2049.28  1206.5 2052.75
#Mann= 8 ,-1,0
       0      .1       0      50     .06       0     150      .1       0
  251.01     .05       0     770    .045       0   784.6     .05       0
  931.01     .06       0 1031.01     .05       0
Bank Sta=770,784.6
XS Rating Curve= 0 ,0
Exp/Cntr(USF)=0,0
Exp/Cntr=0.3,0.1

Type RM Length L Ch R = 1 ,69134   ,555.1,555.1,555.1
XS GIS Cut Line= 2
2306265.33904553761428.9075608672305107.81001834761439.533064343
#Sta/Elev= 30
       0 2129.24   105.2 2083.02   157.2 2056.56   165.2 2053.41   186.6 2040.18
   207.5  2029.1   225.2 2021.01   233.2 2018.91   265.2 2017.51   297.2 2018.36
   333.2 2015.64   397.2 2014.93   653.2 2016.08   697.2 2014.92   733.2 2015.61
   738.7  2014.4   741.2 2013.53   750.6  2014.4   757.2 2015.83   765.2 2020.96
   769.2 2021.62   853.2 2026.81   889.3 2027.59   901.2 2026.22   913.3 2026.32
   925.2 2028.54   965.2 2029.62  1042.5 2028.99  1117.2 2029.78  1157.6 2031.07
#Mann= 6 ,-1,0
       0      .1       0     320     .05       0   738.7    .045       0
   750.6     .05       0     810     .07       0    1100     .05       0
Bank Sta=738.7,750.6
XS Rating Curve= 0 ,0
Exp/Cntr(USF)=0,0
Exp/Cntr=0.3,0.1

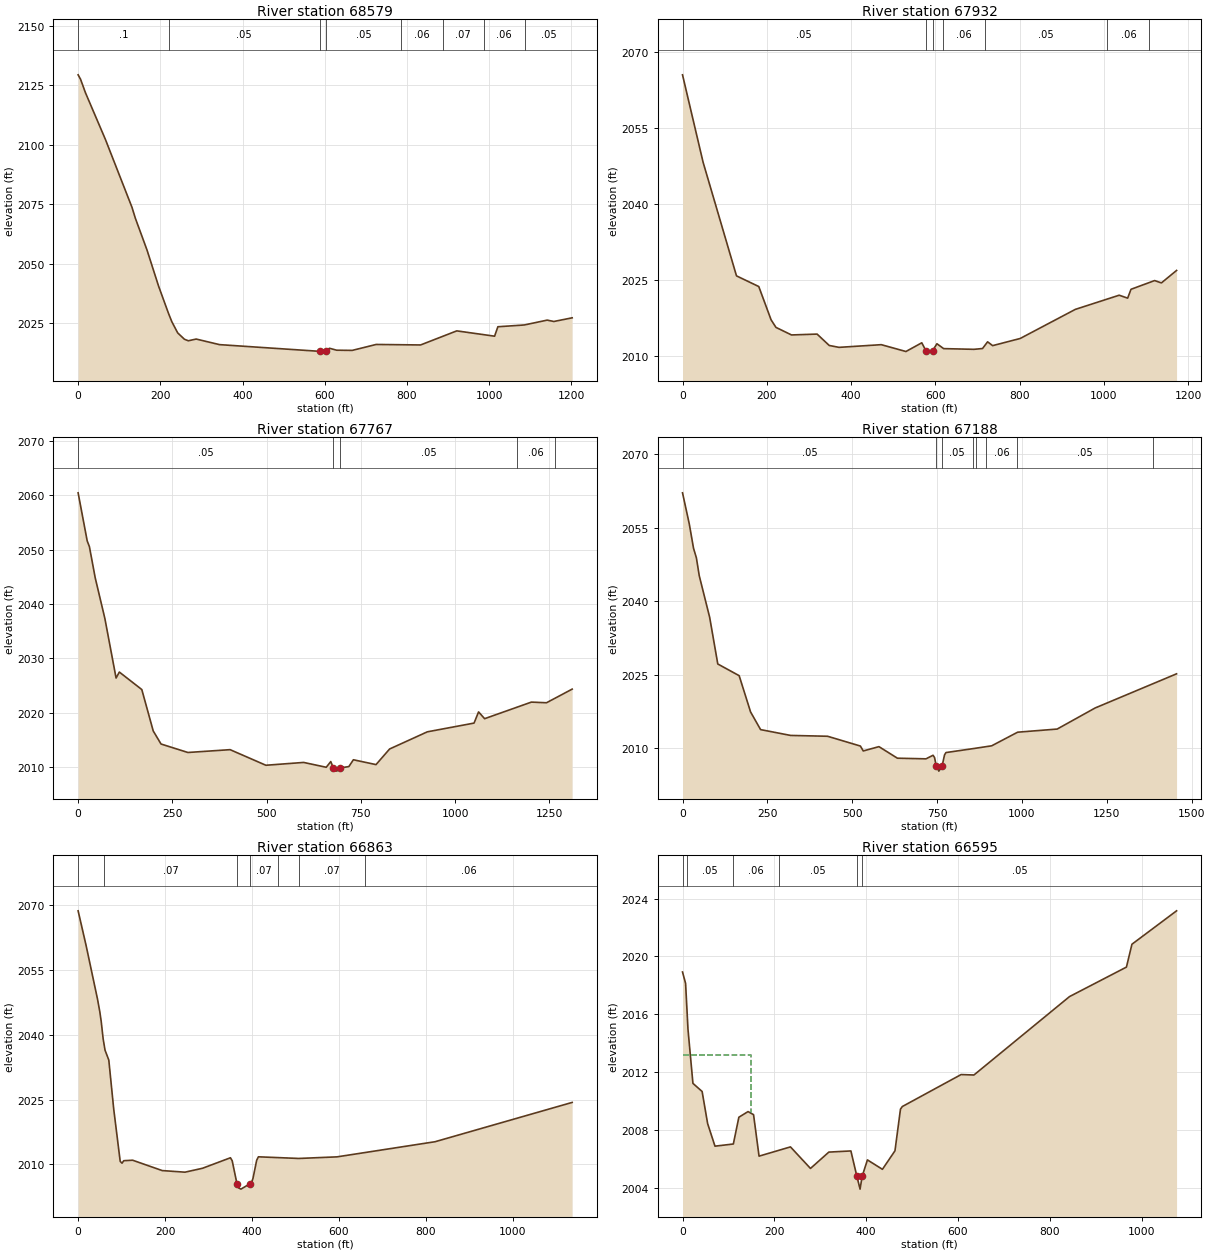
Type RM Length L Ch R = 1 ,68579   ,647,647,647
XS GIS Cut Line= 4
2306266.01421252761416.3079048462306026.01011778761383.779252936
2305634.76296071761134.0715085772305139.51294253761123.312404159
#Sta/Elev= 30
       0 2129.45     5.9  2127.6      18 2121.85    66.4 2102.24     131 2073.67
   139.1 2069.12   167.4 2055.76   195.6 2040.54   219.8 2029.02   227.9 2025.51
   242.2 2020.78   258.6  2018.1   268.1 2017.46   287.1 2018.19   343.9 2015.84
   587.2 2013.02     593 2012.26   603.9 2013.13   611.3 2014.32   628.7 2013.49
   666.7 2013.41   724.9 2015.91     833  2015.7     921 2021.63    1013 2019.39
    1021 2023.37    1085 2024.11    1141 2026.16    1157 2025.58  1201.7 2027.13
#Mann= 8 ,-1,0
       0      .1       0     220     .05       0   587.2    .045       0
   603.9     .05       0  786.34     .06       0  886.34     .07       0
  986.34     .06       0 1086.34     .05       0
Bank Sta=587.2,603.9
XS Rating Curve= 0 ,0
Exp/Cntr(USF)=0,0
Exp/Cntr=0.3,0.1

Type RM Length L Ch R = 1 ,67932   ,165,165,165
XS GIS Cut Line= 3
2306198.73390178761186.9871110272306019.50255391760888.469148789
2305196.21814107 760848.31213552
#Sta/Elev= 30
       0 2065.47    48.8 2048.21   128.1 2025.76     181 2023.65   210.2 2017.08
   221.8 2015.58   258.7 2014.09   319.4 2014.26   348.2 2012.01   371.5 2011.64
   471.7 2012.17   530.2 2010.82   567.8 2012.54  577.462011.009   579.8  2010.5
  593.472010.995   603.8 2012.35   619.8 2011.39   691.9 2011.25     712 2011.41
     724 2012.73     736 2011.98   801.3 2013.39   932.2 2019.14  1036.3 2021.94
  1056.4 2021.36  1064.4 2023.11  1120.4 2024.83  1136.5 2024.37  1172.5 2026.83
#Mann= 7 ,-1,0
       0     .05       0  577.46    .045       0  593.47     .05       0
  618.19     .06       0  718.19     .05       0 1008.19     .06       0
 1108.19     .05       0
Bank Sta=577.46,593.47
XS Rating Curve= 0 ,0
Exp/Cntr(USF)=0,0
Exp/Cntr=0.3,0.1

Type RM Length L Ch R = 1 ,67767   ,578.5,578.5,578.5
XS GIS Cut Line= 3
2306223.82884697761159.8280217322306068.55244112760733.655442293
2305211.95172625760737.635542625
#Sta/Elev= 30
       0 2060.45    24.1  2051.6    29.9 2050.56    45.4 2044.79    70.9 2037.34
   100.7 2026.37   109.3 2027.47   168.9 2024.25   199.2 2016.63   219.9 2014.23
   291.1 2012.67     403 2013.19     498 2010.32     598 2010.84     658 2009.95
     670    2011  677.052009.804     686 2009.24     694 2009.81     718 2010.08
     730 2011.33     790 2010.44     826 2013.31     926 2016.47    1050 2018.08
    1062 2020.14    1078 2018.89    1202 2021.94  1242.1 2021.82  1310.2 2024.33
#Mann= 5 ,-1,0
       0     .05       0  677.05    .045       0     694     .05       0
 1163.58     .06       0 1263.58     .05       0
Bank Sta=677.05,694
XS Rating Curve= 0 ,0
Exp/Cntr(USF)=0,0
Exp/Cntr=0.3,0.1

Type RM Length L Ch R = 1 ,67188   ,325.6,325.6,325.6
XS GIS Cut Line= 3
2306245.86304418761160.0894661432305984.14401643760346.445958109
2305385.92909587760403.418807687
#Sta/Elev= 30
       0 2062.13    19.9 2055.79    32.5 2050.79    40.9 2048.85    49.3  2045.2
      80 2036.71   103.9 2027.18   166.9 2024.79   200.5 2017.39     230 2013.78
   318.4 2012.59   427.4 2012.42   524.1 2010.42   532.5 2009.42   578.7  2010.3
   633.1 2007.94   717.4 2007.81   738.1 2008.54   742.6 2008.07   747.6 2006.33
   755.2  2005.3  764.45 2006.25     772 2008.62   776.2 2009.09   854.7 2009.88
   910.9 2010.47   987.3 2013.25  1103.8 2013.89  1215.8  2018.2  1455.6 2025.17
#Mann= 8 ,-1,0
       0     .05       0   747.6    .045       0  764.45     .05       0
   854.7     .07       0   864.7     .05       0   894.7     .06       0
   984.7     .05       0  1384.7     .07       0
Bank Sta=747.6,764.45
XS Rating Curve= 0 ,0
Exp/Cntr(USF)=0,0
Exp/Cntr=0.3,0.1

Type RM Length L Ch R = 1 ,66863   ,268,268,268
BEGIN DESCRIPTION:
Structure
END DESCRIPTION:
XS GIS Cut Line= 3
2306500.79179859760246.1622578432306410.02769168  760206.2260508
2305378.31274357760314.234614753
#Sta/Elev= 30
       0 2068.74    18.2 2060.78    44.4 2048.38    49.8 2045.41    53.1 2043.13
    57.5 2039.11    61.9 2036.45    70.6 2034.14    81.9 2022.78    96.8 2010.67
     101 2010.24     105 2010.82   125.4 2010.93   193.5 2008.53   245.8 2008.16
     286 2009.06   350.4  2011.5   354.4 2010.82   365.62005.383   369.3  2004.5
   374.5 2004.23   394.4 2005.42   398.6 2005.72   402.1 2006.65   410.7  2010.9
   414.7 2011.72   507.7 2011.34   595.7 2011.71   821.2 2015.22  1136.5 2024.33
#Mann= 7 ,-1,0
       0      .1       0      60     .07       0   365.6    .045       0
   394.4     .07       0  459.16     .05       0  509.16     .07       0
  659.16     .06       0
Bank Sta=365.6,394.4
XS Rating Curve= 0 ,0
Exp/Cntr(USF)=0,0
Exp/Cntr=0.3,0.1

Type RM Length L Ch R = 1 ,66595   ,507,507,507
XS GIS Cut Line= 2
2306550.84270708759990.2730297622305474.99737139760005.634890507
#Sta/Elev= 30
       0 2018.92     6.7 2018.13    11.9 2014.96    22.7 2011.22    42.7 2010.66
    54.7 2008.44    70.7 2006.88   110.7 2007.03   122.7 2008.88   142.7 2009.27
   154.7 2009.06   166.7 2006.19   235.1 2006.83   278.7 2005.34   318.7 2006.47
   366.7 2006.55  379.712004.801   386.7 2003.91  391.132004.784   402.7 2005.93
   435.4 2005.28   462.7 2006.56   474.7 2009.44   478.7 2009.62   606.7 2011.83
   634.7  2011.8   842.8 2017.22   966.8 2019.26   978.8 2020.84    1076 2023.15
#Mann= 6 ,-1,0
       0      .1       0      10     .05       0     110     .06       0
     210     .05       0  379.71    .045       0  391.13     .05       0
#XS Ineff= 2 , 0
          149.89 2013.17
Permanent Ineff=
       F       F
Bank Sta=379.71,391.13
XS Rating Curve= 0 ,0
Exp/Cntr(USF)=0,0
Exp/Cntr=0.3,0.1

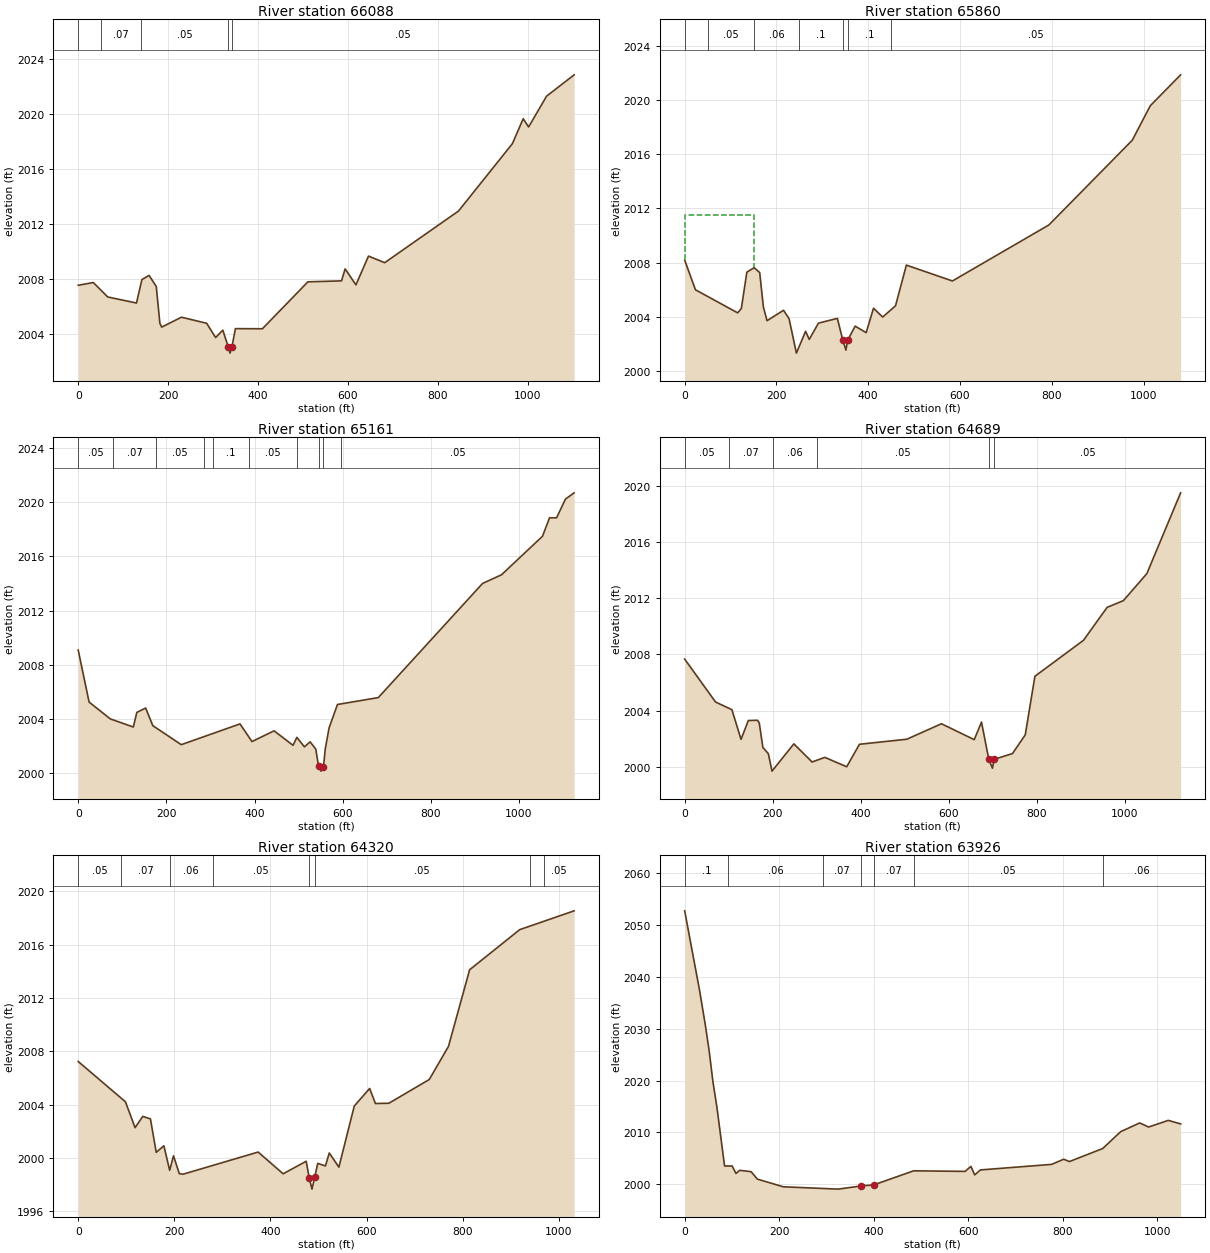
Type RM Length L Ch R = 1 ,66088   ,227.9,227.9,227.9
XS GIS Cut Line= 2
2306585.78246827759758.6696952972305482.85663885759757.950249039
#Sta/Elev= 30
       0 2007.56    33.6 2007.76    65.6 2006.71   129.6 2006.27   141.6 2007.97
   157.6 2008.28   173.6 2007.47   181.6  2004.8   185.6 2004.52   229.6 2005.24
   285.6  2004.8   305.6 2003.76   321.6  2004.3   334.12003.039   337.6 2002.63
   341.6 2003.04   349.6 2004.41   409.6  2004.4   510.8 2007.81   585.6 2007.88
   593.6 2008.75   617.6 2007.59   645.6 2009.68   681.6  2009.2   845.6 2012.95
   965.6 2017.85   989.6 2019.66  1001.6 2019.06  1041.6  2021.3  1102.9 2022.85
#Mann= 5 ,-1,0
       0     .05       0      50     .07       0     140     .05       0
   334.1    .045       0   341.6     .05       0
Bank Sta=334.1,341.6
XS Rating Curve= 0 ,0
Exp/Cntr(USF)=0,0
Exp/Cntr=0.3,0.1

Type RM Length L Ch R = 1 ,65860   ,698.6,698.6,698.6
XS GIS Cut Line= 2
2306591.63111137759588.6033362182305510.83477555759581.487760822
#Sta/Elev= 30
       0 2008.18    23.5 2005.99   115.5 2004.29   123.5 2004.61   135.5 2007.29
   151.5 2007.62   163.5 2007.26   171.5 2004.73   179.5 2003.71   215.5 2004.48
   227.5 2003.86   243.5 2001.32   263.5 2002.93   271.5 2002.33   291.5 2003.53
   332.7 2003.88   344.6 2002.28   351.5 2001.54   354.92002.252   371.5 2003.31
   395.5 2002.83   411.5 2004.63   431.5 2003.98   459.5 2004.81   483.2 2007.81
   583.5 2006.64   793.7 2010.77   975.5 2017.02  1014.7 2019.56  1080.8 2021.84
#Mann= 7 ,-1,0
       0      .1       0      50     .05       0     150     .06       0
     250      .1       0   344.6    .045       0   354.9      .1       0
     450     .05       0
#XS Ineff= 2 , 0
          151.62 2011.48
Permanent Ineff=
       F       F
Bank Sta=344.6,354.9
XS Rating Curve= 0 ,0
Exp/Cntr(USF)=0,0
Exp/Cntr=0.3,0.1

Type RM Length L Ch R = 1 ,65161   ,472.4,472.4,472.4
XS GIS Cut Line= 4
2306616.78948717759228.7209250892306450.86313076759216.375282172
2305698.59788019759512.5570893892305548.35798458759513.421537312
#Sta/Elev= 30
       0 2009.09    24.7 2005.26    72.8 2004.02     125 2003.42     133  2004.5
     153 2004.82   169.3 2003.52   233.8 2002.12     367 2003.65   394.2 2002.35
   444.4 2003.14   487.4 2002.07     496 2002.66   513.2 2001.96   526.1 2002.33
     539 2001.79   545.32000.515   550.7 2000.17   556.42000.477   560.5 2001.81
   569.1 2003.35   588.1 2005.08   680.8 2005.59   917.3    2014   960.3 2014.64
  1053.3 2017.48  1069.3 2018.84  1085.3 2018.84  1105.4 2020.22  1125.1 2020.68
#Mann= 10 ,-1,0
       0     .05       0      80     .07       0  176.39     .05       0
  286.39     .06       0  306.39      .1       0  386.39     .05       0
  496.39     .07       0   545.3    .045       0   556.4     .07       0
  596.39     .05       0
Bank Sta=545.3,556.4
XS Rating Curve= 0 ,0
Exp/Cntr(USF)=0,0
Exp/Cntr=0.3,0.1

Type RM Length L Ch R = 1 ,64689   ,369.1,369.1,369.1
XS GIS Cut Line= 3
2306631.89550858759010.8291463862305728.53873386759253.222869397
2305541.39460766759296.494829286
#Sta/Elev= 30
       0 2007.67    70.1 2004.62   107.4 2004.07   128.1 2001.96   144.7  2003.3
   165.4 2003.32   169.5 2003.14   177.8 2001.38   190.2 2000.94   198.5  1999.7
   248.2 2001.64   289.6 2000.35   318.6 2000.68   368.3 2000.01   397.3 2001.61
     505 2001.97   583.7 2003.07   658.2 2001.94   674.8 2003.19   691.3 2000.54
   699.6 1999.91   703.6 2000.54   745.2 2000.95   774.2 2002.28   796.2 2006.45
   906.7 2009.01   960.3 2011.35   997.3 2011.83  1050.6 2013.75  1127.4  2019.5
#Mann= 6 ,-1,0
       0     .05       0     100     .07       0     200     .06       0
     300     .05       0   691.3    .045       0   703.6     .05       0
Bank Sta=691.3,703.6
XS Rating Curve= 0 ,0
Exp/Cntr(USF)=0,0
Exp/Cntr=0.3,0.1

Type RM Length L Ch R = 1 ,64320   ,394,394,394
XS GIS Cut Line= 2
2306626.51689484758977.2128104912305594.70317882758968.508437209
#Sta/Elev= 30
       0 2007.23    98.3 2004.21   118.3 2002.27   134.3 2003.11   150.3 2002.93
   162.3 2000.42   178.3 2000.91   190.3 1999.07   198.3 2000.16   210.3 1998.82
   218.3 1998.78   374.4 2000.44   426.4 1998.81   474.4 1999.75   480.7  1998.5
   486.4 1997.66   491.91998.535   498.4 1999.59   514.4  1999.4   522.4 2000.37
   542.4 1999.31   574.4 2003.89   606.4 2005.21   618.4 2004.08   646.4  2004.1
   730.4 2005.88   770.4 2008.36   814.4 2014.11   918.7 2017.12  1031.9 2018.53
#Mann= 8 ,-1,0
       0     .05       0      90     .07       0     190     .06       0
     280     .05       0   480.7    .045       0   491.9     .05       0
     940     .06       0     970     .05       0
Bank Sta=480.7,491.9
XS Rating Curve= 0 ,0
Exp/Cntr(USF)=0,0
Exp/Cntr=0.3,0.1

Type RM Length L Ch R = 1 ,63926   ,119.1,119.1,119.1
BEGIN DESCRIPTION:
Structure
END DESCRIPTION:
XS GIS Cut Line= 4
2306630.78646952758741.7030251522306550.44352657 758758.93978627
2306158.91310665758733.924536886 2305585.7669029758690.936855637
#Sta/Elev= 30
       0 2052.73    31.3  2037.5    43.6 2030.77    51.8 2025.75    59.9 2019.71
    68.1 2014.94    84.4 2003.54   100.5 2003.54   108.5  2002.1   116.5 2002.71
   140.6 2002.44   153.8 2001.01   208.7 1999.53   324.9 1999.08   373.9  1999.7
     4001999.895   484.5 2002.61   593.4  2002.5   605.6 2003.47   613.6 2001.83
   625.7 2002.78   776.3 2003.85   801.9 2004.84   814.2  2004.4   884.5 2006.91
   922.5 2010.16   962.8 2011.84   981.5 2011.05  1023.1 2012.33  1049.3 2011.66
#Mann= 7 ,-1,0
       0      .1       0   92.17     .06       0  292.17     .07       0
   373.9    .045       0     400     .07       0   484.5     .05       0
   884.5     .06       0
Bank Sta=373.9,400
XS Rating Curve= 0 ,0
Exp/Cntr(USF)=0,0
Exp/Cntr=0.3,0.1