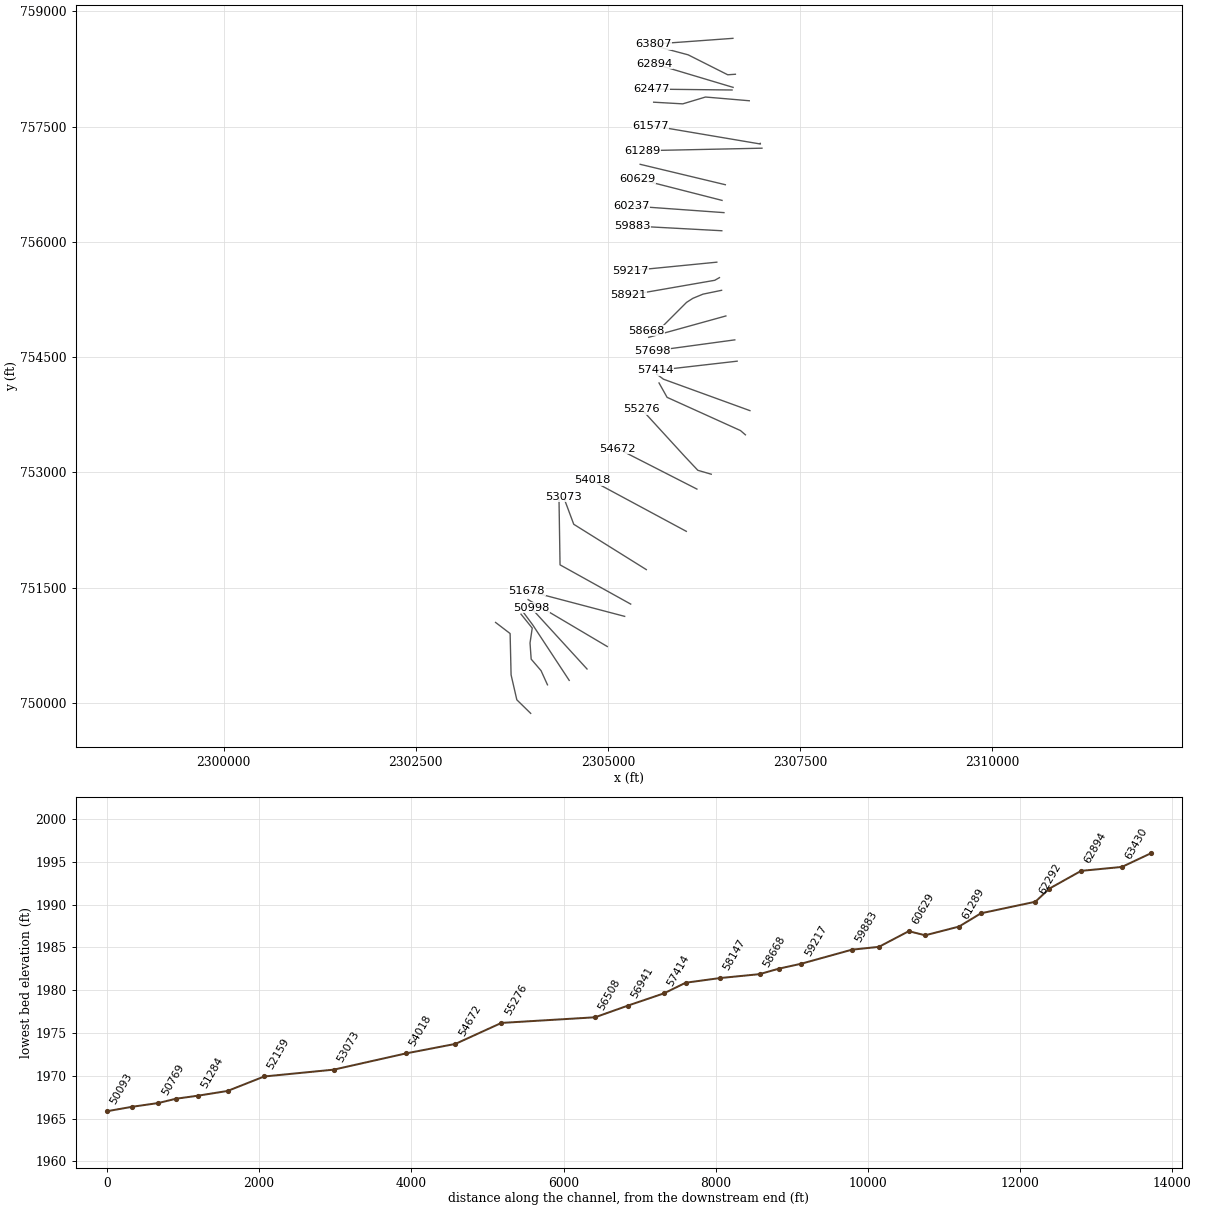
HEC-RAS study LEADNGCK.prj: LEADNGCK

--- LEADNGCK.g01 (geometry) --- (continued)

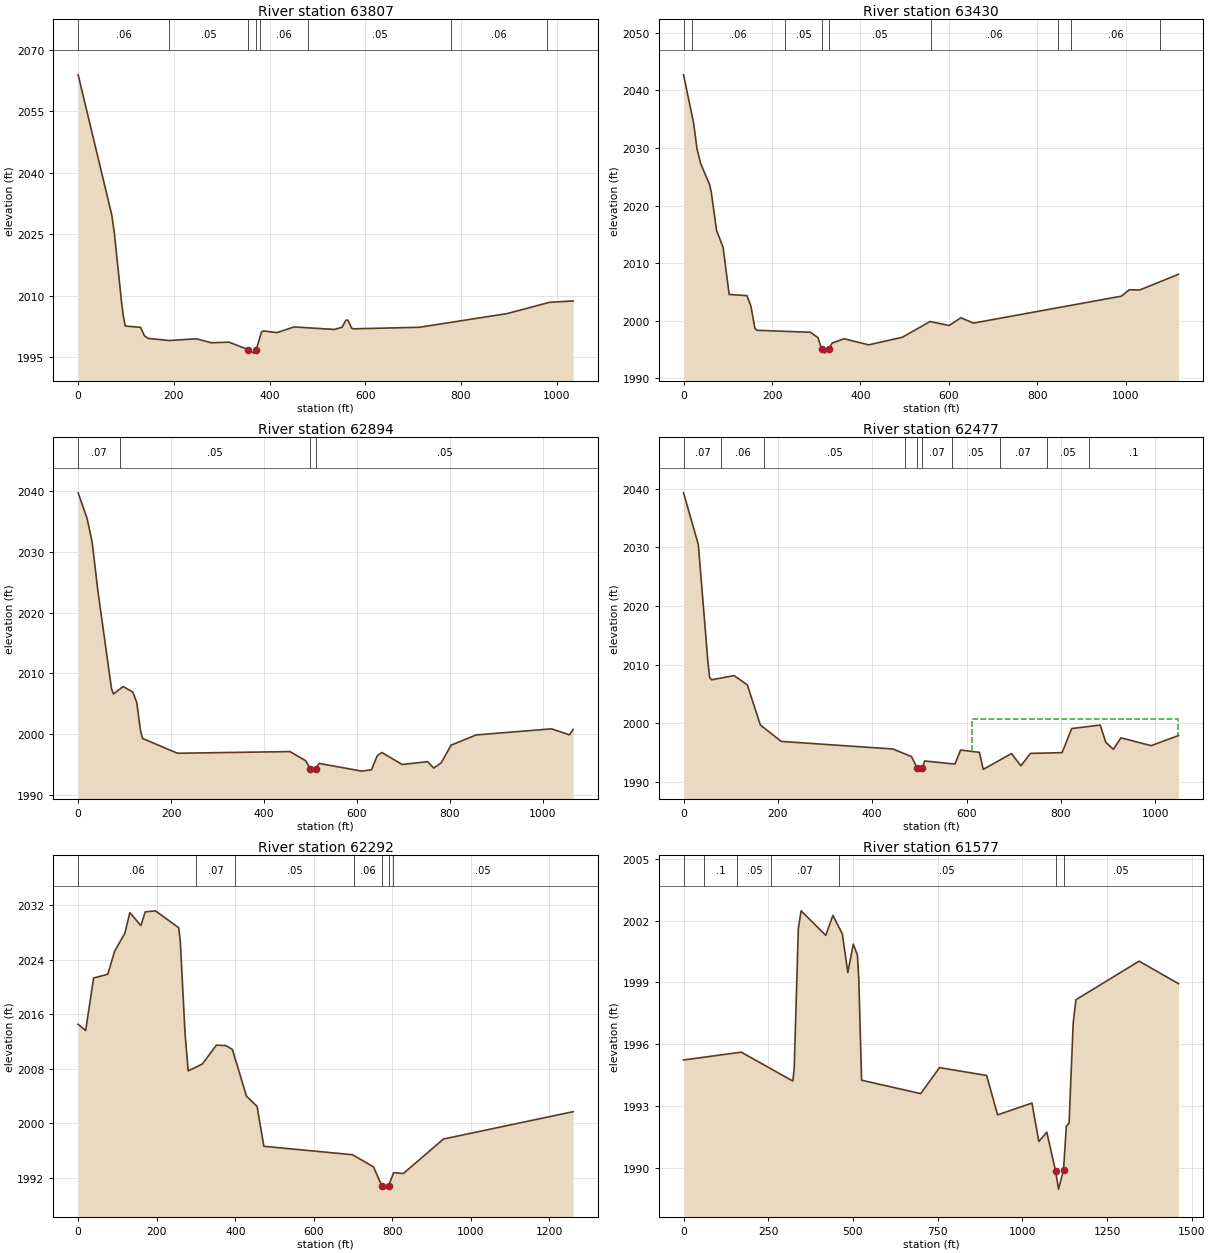
Type RM Length L Ch R = 1 ,63807   ,376.5,376.5,376.5
XS GIS Cut Line= 2
2306626.30472261758648.0490007732305594.58558147758572.987745152
#Sta/Elev= 30
       0 2063.83    70.3 2029.64    75.7  2025.2    90.4 2008.71    94.4 2005.03
    98.4 2002.59   130.5 2002.26   138.5  2000.2   146.3 1999.57   190.6 1999.05
   246.8 1999.48   278.9  1998.5     315 1998.66   355.81996.824   367.1 1995.98
     3721996.746   383.1 2001.12   387.2  2001.4   415.2 2000.98   451.3 2002.37
   535.7 2001.75   551.6  2002.3   559.6    2004   563.6 2004.04   571.6 2002.07
   575.6 2001.91   712.9 2002.28   896.5 2005.62   984.7 2008.36  1034.4 2008.71
#Mann= 8 ,-1,0
       0     .06       0     190     .05       0   355.8    .045       0
     372     .05       0     380     .06       0     480     .05       0
     780     .06       0     980     .05       0
Bank Sta=355.8,372
XS Rating Curve= 0 ,0
Exp/Cntr(USF)=0,0
Exp/Cntr=0.3,0.1

Type RM Length L Ch R = 1 ,63430   ,535.9,535.9,535.9
XS GIS Cut Line= 4
2306658.68106973 758180.576570552306558.94323277758173.780843218
2306043.94096686758433.2989563252305616.54601274758547.718922295
#Sta/Elev= 30
       0 2042.67    22.6 2034.37    30.6 2029.79    38.6 2027.31    58.6 2023.69
    62.7 2022.31    74.7 2015.66    89.4 2012.77   103.1 2004.58   143.4 2004.37
   152.3 2002.56   161.3 1998.72   165.8 1998.36   286.7 1998.02   304.1 1997.08
     312 1995.09     319  1994.4   327.9 1995.06     336 1996.15   362.9 1996.89
   418.6 1995.84   494.7 1997.15   557.3 1999.88   600.3 1999.19   627.1 2000.53
   655.6 1999.61   989.9 2004.28  1007.7 2005.38    1032 2005.37  1119.1 2008.07
#Mann= 9 ,-1,0
       0      .1       0      20     .06       0  229.97     .05       0
     312    .045       0   327.9     .05       0  559.97     .06       0
  846.66     .05       0  876.66     .06       0 1076.66     .05       0
Bank Sta=312,327.9
XS Rating Curve= 0 ,0
Exp/Cntr(USF)=0,0
Exp/Cntr=0.3,0.1

Type RM Length L Ch R = 1 ,62894   ,417,417,417
XS GIS Cut Line= 2
2306629.01013173 758009.869993232305608.34792918758315.157794181
#Sta/Elev= 30
       0 2039.68    19.4 2035.42    30.1 2031.57    42.6 2023.49    71.8 2007.47
      76 2006.62    96.9 2007.84   117.8 2006.92   126.1  2005.2   134.5 2000.44
   138.7  1999.3   213.8 1996.88     456 1997.15   489.4 1995.67   499.81994.333
   511.1 1994.37   518.6 1995.21   610.4 1993.94   631.3 1994.16   643.8 1996.48
   653.6    1997   697.5 1995.03   752.4  1995.5   765.3 1994.44   781.6 1995.32
   802.5  1998.2   856.8 1999.89  1018.9 2000.89  1057.5  1999.9  1065.3 2000.79
#Mann= 4 ,-1,0
       0     .07       0      90     .05       0   499.8    .045       0
   511.1     .05       0
Bank Sta=499.8,511.1
XS Rating Curve= 0 ,0
Exp/Cntr(USF)=0,0
Exp/Cntr=0.3,0.1

Type RM Length L Ch R = 1 ,62477   ,185.1,185.1,185.1
XS GIS Cut Line= 2
2306615.46698383757975.8349986742305566.25039362757987.115549487
#Sta/Elev= 30
       0 2039.28    31.3  2030.5    51.3 2010.84    55.3 2007.86    59.3 2007.43
   107.3 2008.14   135.3 2006.55   162.9 1999.72   207.3 1996.93   443.9 1995.64
   483.2 1994.35   495.71992.337   503.3 1991.87   505.41992.319   511.3  1993.6
   575.3 1993.07   587.3 1995.46   627.3 1995.07   635.3 1992.17   695.3 1994.86
   715.3 1992.77   735.3 1994.89   802.6 1995.02   822.8 1999.12   883.3 1999.72
   895.3 1996.76   911.3 1995.59   927.3 1997.54   991.3 1996.21  1049.3 1997.93
#Mann= 10 ,-1,0
       0     .07       0      80     .06       0     170     .05       0
     470     .07       0   495.7    .045       0   505.4     .07       0
     570     .05       0     670     .07       0     770     .05       0
     860      .1       0
#XS Ineff= 2 , 0
                          610.83         2000.69
Permanent Ineff=
       F       F
Bank Sta=495.7,505.4
XS Rating Curve= 0 ,0
Exp/Cntr(USF)=0,0
Exp/Cntr=0.3,0.1

Type RM Length L Ch R = 1 ,62292   ,714.8,714.8,714.8
XS GIS Cut Line= 5
 2306839.3126508757835.7078192812306430.81655411 757870.57891616
2306269.35041687757884.1635573752305973.51828465757795.260636812
2305594.73332098 757816.92331453
#Sta/Elev= 30
       0 2014.53    19.1 2013.62    39.3 2021.32    75.4 2021.88      93 2025.28
   118.9 2027.89   131.6 2030.93   159.7 2029.03   170.7 2031.03   196.6 2031.19
   256.1 2028.71   260.1 2026.68   272.1 2013.24   280.2 2007.69   316.3  2008.7
   351.9 2011.47   376.5  2011.4   392.6 2010.84   428.7 2003.97   455.6 2002.47
   472.8 1996.62   698.5 1995.38     752  1993.6773.77431990.739   777.9 1990.33
790.47431990.836   803.4 1992.75     828 1992.62   930.3 1997.69  1260.3  2001.7
#Mann= 7 ,-1,0
       0     .06       0     300     .07       0     400     .05       0
  702.02     .06       0773.7743    .045       0790.4743     .06       0
  802.02     .05       0
Bank Sta=773.7743,790.4743
XS Rating Curve= 0 ,0
Exp/Cntr(USF)=0,0
Exp/Cntr=0.3,0.1

Type RM Length L Ch R = 1 ,61577   ,288.1,288.1,288.1
XS GIS Cut Line= 4
2306981.98402425757281.200502323 2306985.2646611 757272.57899412
2305690.63863806757491.7442108662305553.23971807757512.361464132
#Sta/Elev= 30
       0 1995.24   170.3 1995.62   322.7 1994.22   326.8 1994.87   338.9 2001.62
   347.1 2002.47     420 2001.28   440.9 2002.25   468.8 2001.35     485 1999.48
   501.2 2000.86   513.4 2000.32   517.4 1999.16   525.6 1994.26     700 1993.61
   755.7 1994.87   894.7 1994.49   927.2 1992.58  1028.6 1993.15  1048.9 1991.29
  1072.4 1991.741098.1511989.873  1107.1 1988.98  1121.9 1989.93    1130 1992.02
  1138.2 1992.18  1150.3 1997.02  1158.4 1998.16    1345 2000.03  1461.2 1998.94
#Mann= 7 ,-1,0
       0     .05       0   59.22      .1       0  159.22     .05       0
  259.22     .07       0  459.22     .05       01098.151    .045       0
  1121.9     .05       0
Bank Sta=1098.151,1121.9
XS Rating Curve= 0 ,0
Exp/Cntr(USF)=0,0
Exp/Cntr=0.3,0.1

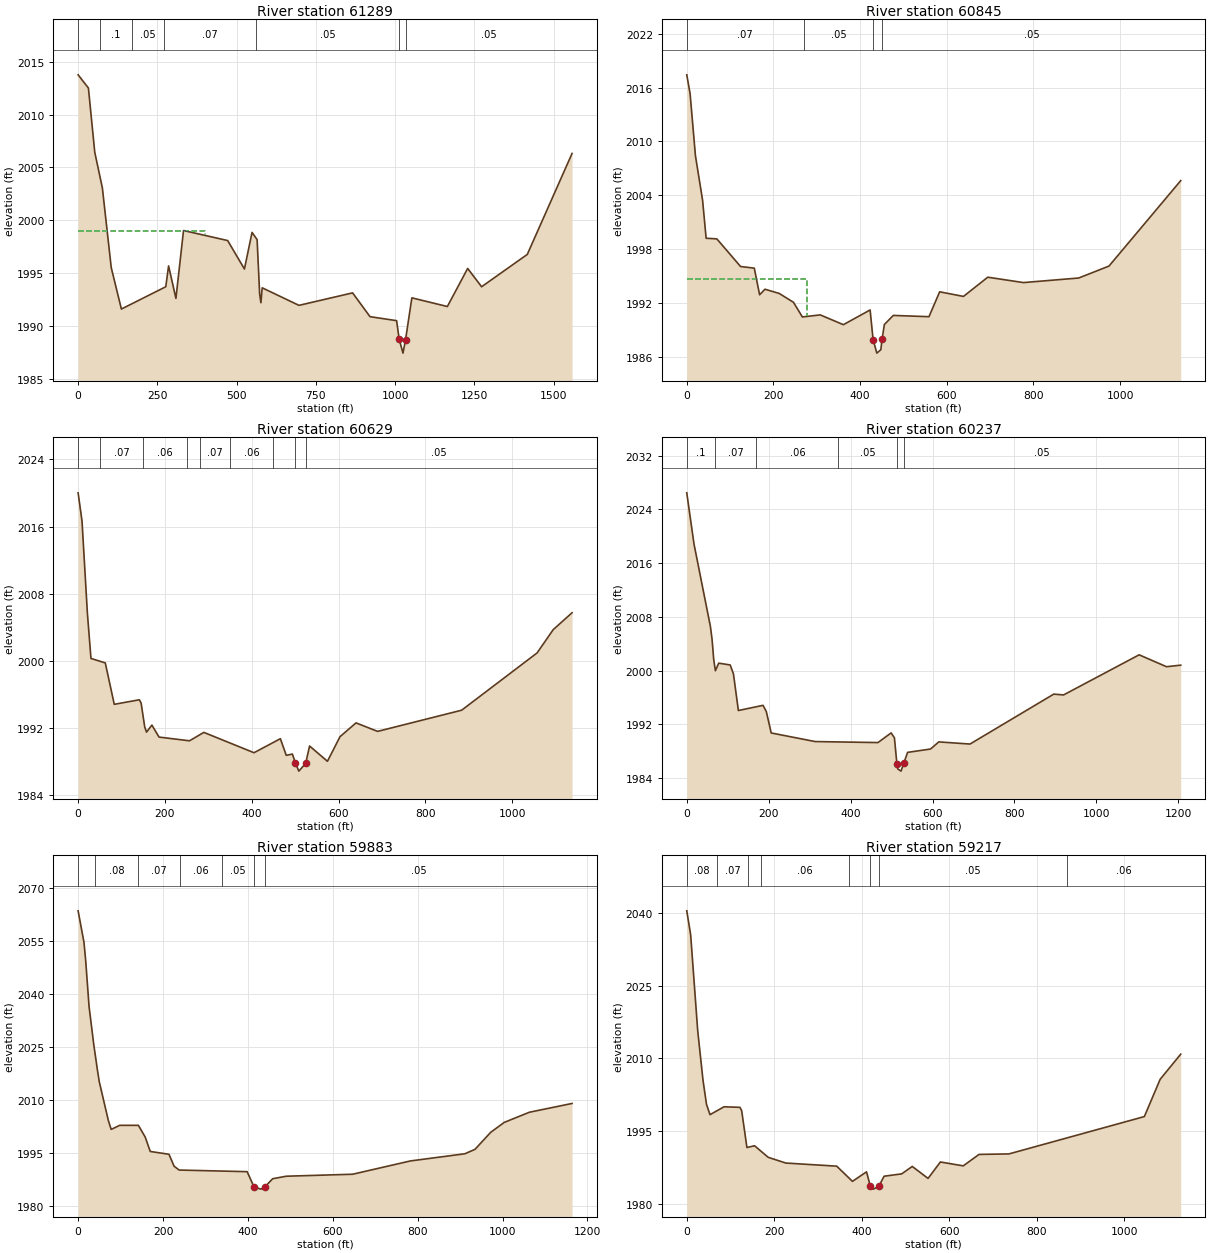
Type RM Length L Ch R = 1 ,61289   ,443.9,443.9,443.9
XS GIS Cut Line= 2
2307004.62250716757218.3748550572305446.93637814757185.311138445
#Sta/Elev= 30
       0 2013.76    32.5 2012.51    52.5 2006.44    76.5 2003.06   104.5 1995.52
   136.5  1991.6   276.5 1993.71   285.4 1995.68   308.5 1992.61   332.5 1999.03
   471.7 1998.08   524.6 1995.39   548.6 1998.85   564.6 1998.17   572.6 1993.02
   576.6  1992.2   580.6 1993.61   696.6 1991.95   865.8 1993.13   920.7 1990.88
  1004.6  1990.5  1012.7 1988.74  1024.7 1987.43  1032.7 1988.68  1052.7 1992.66
  1164.7 1991.84  1228.7 1995.44  1272.7 1993.71  1416.8 1996.77    1558 2006.32
#Mann= 7 ,-1,0
       0     .05       0      70      .1       0     170     .05       0
     270     .07       0     560     .05       0  1012.7    .045       0
  1032.7     .05       0
#XS Ineff= 2 , 0
          399.42 1999.01
Permanent Ineff=
       F       F
Bank Sta=1012.7,1032.7
XS Rating Curve= 0 ,0
Exp/Cntr(USF)=0,0
Exp/Cntr=0.3,0.1

Type RM Length L Ch R = 1 ,60845   ,216.4,216.4,216.4
XS GIS Cut Line= 2
2306527.66868591756742.9736293822305419.19914526757008.581003294
#Sta/Elev= 30
       0 2017.42     7.7 2015.32      20 2008.41    36.5 2003.45    44.7 1999.21
    69.4 1999.14   124.2 1996.06   155.8 1995.88   168.1 1992.91   180.5 1993.53
   213.4 1993.06   246.3 1992.07   266.8 1990.44     308 1990.67   361.4 1989.58
   423.1 1991.22     4301987.902   438.6 1986.41   447.8 1986.79   450.7 1987.97
     456  1989.6   476.6 1990.61   558.9 1990.47   583.6 1993.24   638.5 1992.73
   694.6 1994.87   776.9 1994.27   904.4 1994.78   974.3 1996.11  1139.8 2005.63
#Mann= 4 ,-1,0
       0     .07       0     270     .05       0     430    .045       0
   450.7     .05       0
#XS Ineff= 2 , 0
          276.39  1994.7
Permanent Ineff=
       F       F
Bank Sta=430,450.7
XS Rating Curve= 0 ,0
Exp/Cntr(USF)=0,0
Exp/Cntr=0.3,0.1

Type RM Length L Ch R = 1 ,60629   ,392.3,392.3,392.3
XS GIS Cut Line= 2
2306484.85752652756539.0332099032305382.10259629756820.648284676
#Sta/Elev= 30
       0 2020.01       9 2016.65    21.3 2005.75    29.6  2000.3    62.6 1999.77
    83.3 1994.84   141.1 1995.38   145.2 1994.98   153.5 1992.14   157.6 1991.53
     170 1992.37   186.5 1990.94   256.7  1990.5   289.7  1991.5   405.3 1989.08
     466 1990.75   479.6 1988.77   493.7 1988.92   500.81987.852   508.5 1986.89
   524.31987.801   533.3 1989.88   574.5 1988.06   603.4 1990.99   640.3 1992.63
   690.1 1991.62   883.7 1994.14  1057.6 2000.96  1094.7 2003.73  1138.1 2005.74
#Mann= 9 ,-1,0
       0      .1       0      50     .07       0     150     .06       0
     250     .05       0     280     .07       0     350     .06       0
     450     .05       0   500.8    .045       0   524.3     .05       0
Bank Sta=500.8,524.3
XS Rating Curve= 0 ,0
Exp/Cntr(USF)=0,0
Exp/Cntr=0.3,0.1

Type RM Length L Ch R = 1 ,60237   ,353.9,353.9,353.9
XS GIS Cut Line= 2
2306509.85276979756379.7204716092305306.95739707756466.263415471
#Sta/Elev= 30
       0 2026.48    17.7 2018.85    57.8 2006.57    61.8 2004.66    65.8 2001.68
    69.9    2000      78 2001.13     106 2000.86     114 1999.53     126 1994.08
   186.2 1994.85   194.2 1993.93   206.2 1990.74   313.5 1989.46   466.8 1989.31
     499 1990.75     507 1990.02     513 1986.19     515  1985.4     523 1985.06
   530.11986.255   539.1 1987.85   595.2 1988.35   615.3 1989.41   691.5 1989.09
     896 1996.52     920  1996.4  1104.5 2002.37  1171.3  2000.6    1206 2000.83
#Mann= 6 ,-1,0
       0      .1       0      70     .07       0     170     .06       0
     370     .05       0     513    .045       0   530.1     .05       0
Bank Sta=513,530.1
XS Rating Curve= 0 ,0
Exp/Cntr(USF)=0,0
Exp/Cntr=0.3,0.1

Type RM Length L Ch R = 1 ,59883   ,666.1,666.1,666.1
XS GIS Cut Line= 2
2306481.92045884756143.9777005192305319.80314214756206.583146073
#Sta/Elev= 30
       0 2063.64    13.8 2054.73    17.8  2049.6    25.8 2036.51      37  2025.6
    45.8 2018.27    49.8 2015.21    71.2 2004.21    77.9 2001.66    97.9 2002.81
     142 2002.82     158 1999.51     170 1995.41   214.1 1994.61   226.1 1991.23
   238.1 1990.14   398.3 1989.68   414.2 1985.41   430.4 1984.73   439.71985.324
   458.4 1987.68   490.5 1988.39   646.7 1988.95   782.9 1992.72   911.1 1994.75
   935.1 1996.01   972.1 2000.84    1004 2003.65  1063.3 2006.53  1163.8 2009.02
#Mann= 7 ,-1,0
       0     .07       0      40     .08       0     140     .07       0
     240     .06       0     340     .05       0   414.2    .045       0
   439.7     .05       0
Bank Sta=414.2,439.7
XS Rating Curve= 0 ,0
Exp/Cntr(USF)=0,0
Exp/Cntr=0.3,0.1

Type RM Length L Ch R = 1 ,59217   ,295.5,295.5,295.5
XS GIS Cut Line= 2
2306417.04623685755734.9952075932305293.52089584755624.145739547
#Sta/Elev= 30
       0  2040.4     8.9 2035.48      25 2015.72    37.1 2005.52    45.1 2000.55
    53.1 1998.42    85.3 2000.05   121.5 1999.93   125.5 1999.25   137.5 1991.66
     155 1992.02   186.2 1989.64   226.4 1988.46   342.7 1987.82   378.7 1984.69
   410.9 1986.65   419.41983.757   426.9 1983.09     439  1983.7   451.1 1985.75
   491.2 1986.23   515.4 1987.76   551.5  1985.3   579.7 1988.68   631.9 1987.88
   668.1 1990.24   736.4 1990.34  1045.9 1998.03  1082.1 2005.72    1129 2010.88
#Mann= 8 ,-1,0
       0     .08       0      70     .07       0     140     .08       0
     170     .06       0     370     .05       0   419.4    .045       0
     439     .05       0     870     .06       0
Bank Sta=419.4,439
XS Rating Curve= 0 ,0
Exp/Cntr(USF)=0,0
Exp/Cntr=0.3,0.1

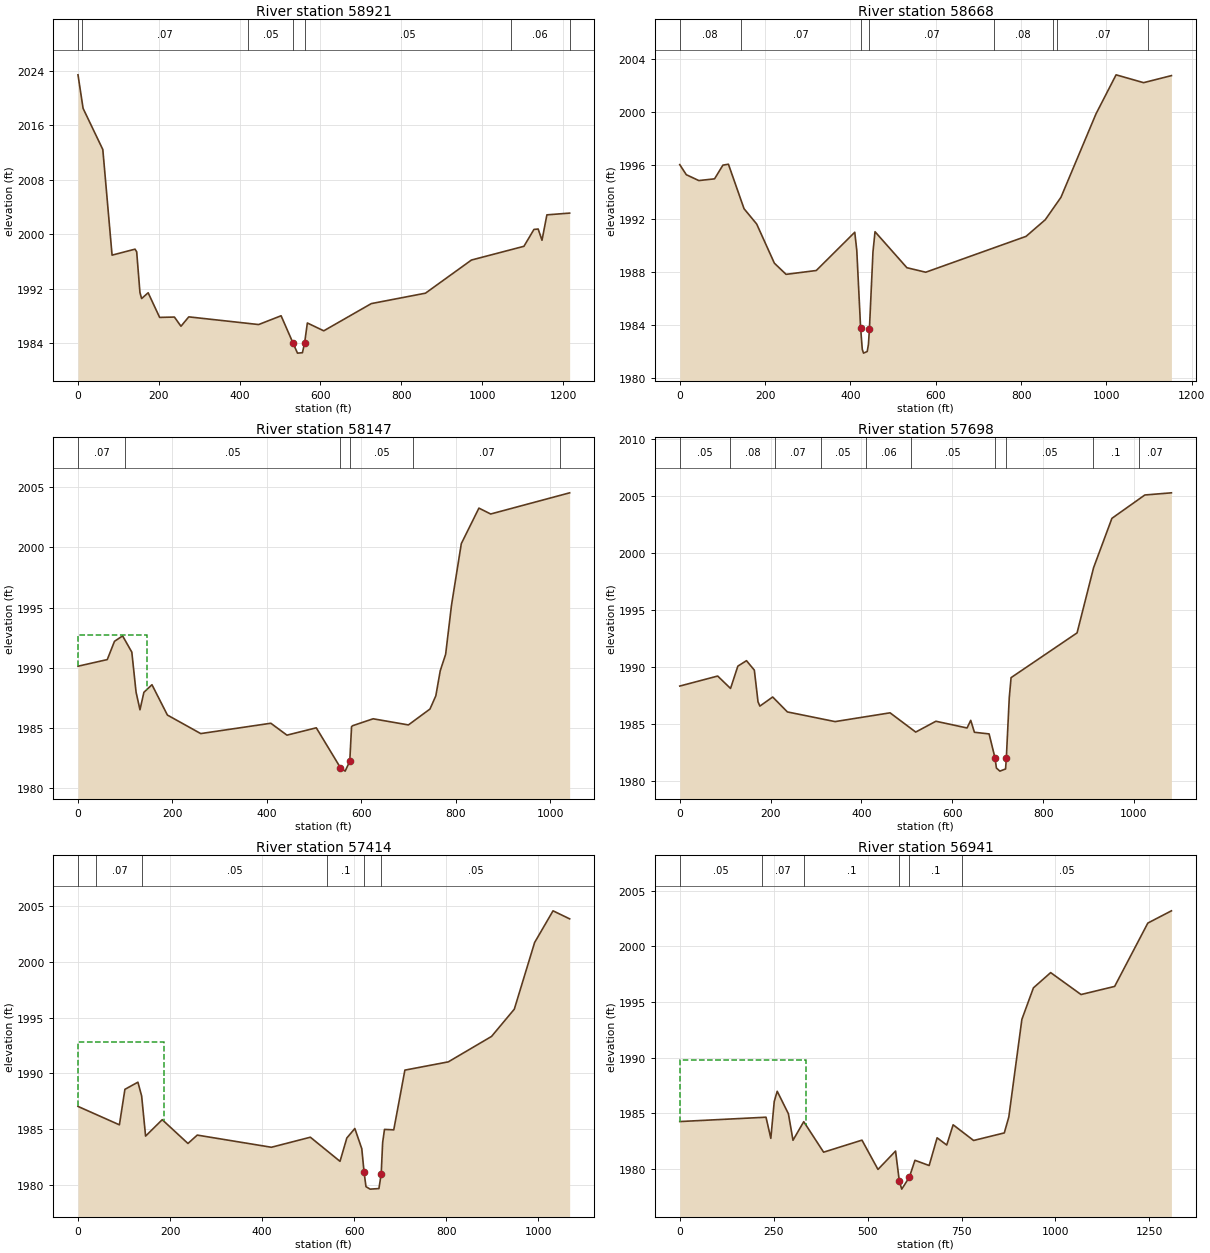
Type RM Length L Ch R = 1 ,58921   ,253.1,253.1,253.1
XS GIS Cut Line= 3
2306451.18855533755533.725612053 2306389.5836351755499.056652331
2305260.73184629755302.505161124
#Sta/Elev= 30
       0 2023.41    12.6 2018.48    61.4 2012.43    84.3 1996.91   141.1 1997.79
   145.2  1997.4   153.3 1991.42   157.4 1990.53   173.6 1991.38     202 1987.76
   238.6 1987.81   254.8 1986.46   274.1 1987.84     447 1986.71   502.5    1988
   532.21983.969   543.1 1982.51   555.3 1982.57   560.7 1983.99   567.5 1986.94
   608.1 1985.79   725.8 1989.79   859.8 1991.32   973.5 1996.19  1103.4 1998.21
  1128.2 2000.69  1138.6 2000.75  1148.1  1999.1  1160.2 2002.83  1216.5 2003.09
#Mann= 7 ,-1,0
       0      .1       0      10     .07       0  420.69     .05       0
   532.2    .045       0   560.7     .05       0 1070.69     .06       0
 1216.53     .05       0
Bank Sta=532.2,560.7
XS Rating Curve= 0 ,0
Exp/Cntr(USF)=0,0
Exp/Cntr=0.3,0.1

Type RM Length L Ch R = 1 ,58668   ,521.4,521.4,521.4
BEGIN DESCRIPTION:
Structure
END DESCRIPTION:
XS GIS Cut Line= 6
2306478.91301783755368.7743822132306237.43845062755318.966433972
2306105.47579062755264.6288680882306023.19319085755211.843804086
2305676.98527107754865.6358843092305503.54368102754843.960669759
#Sta/Elev= 30
       0 1996.06    15.4  1995.3    44.7 1994.86    81.6 1994.99   101.1 1996.02
   114.1 1996.09   150.7 1992.74   180.3 1991.59   221.8 1988.64   249.2  1987.8
     320 1988.09   410.2 1990.97   414.9 1989.62   423.9 1983.78   427.8 1982.16
   430.7 1981.87   439.4 1981.99   442.3 1982.54   444.61983.713   452.9  1989.5
   457.7 1991.01   532.4  1988.3   576.5 1987.96   811.7 1990.66   856.7 1991.91
   893.5  1993.6   975.6 1999.88  1022.7 2002.82  1087.2 2002.23  1152.4 2002.76
#Mann= 8 ,-1,0
       0     .08       0  142.89     .07       0   423.9    .045       0
   444.6     .07       0   735.8     .08       0  874.33     .05       0
  884.33     .07       0 1097.58     .08       0
Bank Sta=423.9,444.6
XS Rating Curve= 0 ,0
Exp/Cntr(USF)=0,0
Exp/Cntr=0.3,0.1

Type RM Length L Ch R = 1 ,58147   ,448.8,448.8,448.8
XS GIS Cut Line= 2
2306534.70859281755034.9712522072305530.98990325 754757.12675002
#Sta/Elev= 30
       0 1990.13      62 1990.68    77.3  1992.2    94.5 1992.65     114  1991.3
     123 1987.98   131.3 1986.51   139.6 1987.96   156.7 1988.59   189.4 1986.07
     260 1984.53   408.5 1985.39   442.6  1984.4   504.8 1985.01  555.921981.696
   565.9 1981.41   575.71982.223   579.5 1985.11   582.1 1985.19   625.2 1985.76
   699.9 1985.25   745.6 1986.57     758 1987.67   767.4 1989.76   778.8 1991.12
   791.2  1995.2     812 2000.32   849.3 2003.27   874.2 2002.78  1041.5 2004.54
#Mann= 6 ,-1,0
       0     .07       0     100     .05       0  555.92    .045       0
   575.7     .05       0     710     .07       0    1020     .08       0
#XS Ineff= 2 , 0
          145.85 1992.72
Permanent Ineff=
       F       F
Bank Sta=555.92,575.7
XS Rating Curve= 0 ,0
Exp/Cntr(USF)=0,0
Exp/Cntr=0.3,0.1

Type RM Length L Ch R = 1 ,57698   ,284.1,284.1,284.1
XS GIS Cut Line= 3
2306650.91481364 754723.845490472305689.54237126754592.985199056
2305577.60327925 754585.38806203
#Sta/Elev= 30
       0 1988.34    83.5 1989.22   111.8 1988.13   127.9 1990.09   146.9 1990.57
   164.2 1989.74   172.3 1986.96   176.4 1986.58   204.6 1987.38   236.9 1986.07
   341.9 1985.22     463 1985.99   519.5  1984.3   563.9 1985.25   632.5 1984.66
   640.6 1985.33   648.7 1984.28     681 1984.14   694.1 1982.02   697.1 1981.14
   704.8 1980.87   717.3 1981.06     719 1982.03   725.4  1987.3   729.4 1989.08
   874.7 1993.01   911.1 1998.74   951.4 2003.07  1023.9 2005.12  1082.4 2005.31
#Mann= 10 ,-1,0
       0     .05       0     110     .08       0     210     .07       0
     310     .05       0     410     .06       0     510     .05       0
   694.1    .045       0     719     .05       0     910      .1       0
 1010.24     .07       0
Bank Sta=694.1,719
XS Rating Curve= 0 ,0
Exp/Cntr(USF)=0,0
Exp/Cntr=0.3,0.1

Type RM Length L Ch R = 1 ,57414   ,473.3,473.3,473.3
XS GIS Cut Line= 3
2306681.45398899754446.4603760582305720.45532378754336.232742407
2305620.17545365754332.195656349
#Sta/Elev= 30
       0 1987.04    89.9 1985.39   101.9 1988.57   130.1 1989.21   138.2 1987.98
   146.8 1984.38   182.9 1985.85   238.8 1983.72     259 1984.47     420 1983.38
   504.6 1984.28     569 1982.12   583.8 1984.21   601.2 1985.06   616.3 1983.25
   621.3 1981.13   625.4 1979.85   634.4 1979.63   653.5 1979.68   658.41980.967
   661.6 1983.81   665.6 1984.98   685.7 1984.94   709.9 1990.29   804.2 1991.03
   898.1 1993.31   947.5 1995.75   991.6 2001.72  1031.6 2004.56  1067.7 2003.84
#Mann= 6 ,-1,0
       0     .05       0      40     .07       0     140     .05       0
     540      .1       0   621.3    .045       0   658.4     .05       0
#XS Ineff= 2 , 0
          186.28 1992.84
Permanent Ineff=
       F       F
Bank Sta=621.3,658.4
XS Rating Curve= 0 ,0
Exp/Cntr(USF)=0,0
Exp/Cntr=0.3,0.1

Type RM Length L Ch R = 1 ,56941   ,432.7,432.7,432.7
XS GIS Cut Line= 3
2306847.99757337 753802.757259542305722.64894352754211.822192112
 2305633.6192982754278.420278152
#Sta/Elev= 30
       0 1984.27   229.6 1984.66   242.4 1982.76   251.5 1986.08   259.4 1986.99
   289.2 1984.97   301.4 1982.59     330 1984.26   382.9 1981.52     485  1982.6
   527.6 1979.97   574.4 1981.62   584.41978.921   590.8  1978.2   611.11979.272
     626 1980.79   663.8 1980.32     685 1982.81   710.6 1982.16   727.6 1983.98
   782.1 1982.57   863.8 1983.25   875.8 1984.68   910.6 1993.45   941.3 1996.28
   987.2 1997.65  1068.1 1995.68  1157.5 1996.41  1245.8  2002.1  1308.6  2003.2
#Mann= 6 ,-1,0
       0     .05       0     220     .07       0     330      .1       0
   584.4    .045       0   611.1      .1       0     750     .05       0
#XS Ineff= 2 , 0
          336.61 1989.79
Permanent Ineff=
       F       F
Bank Sta=584.4,611.1
XS Rating Curve= 0 ,0
Exp/Cntr(USF)=0,0
Exp/Cntr=0.3,0.1

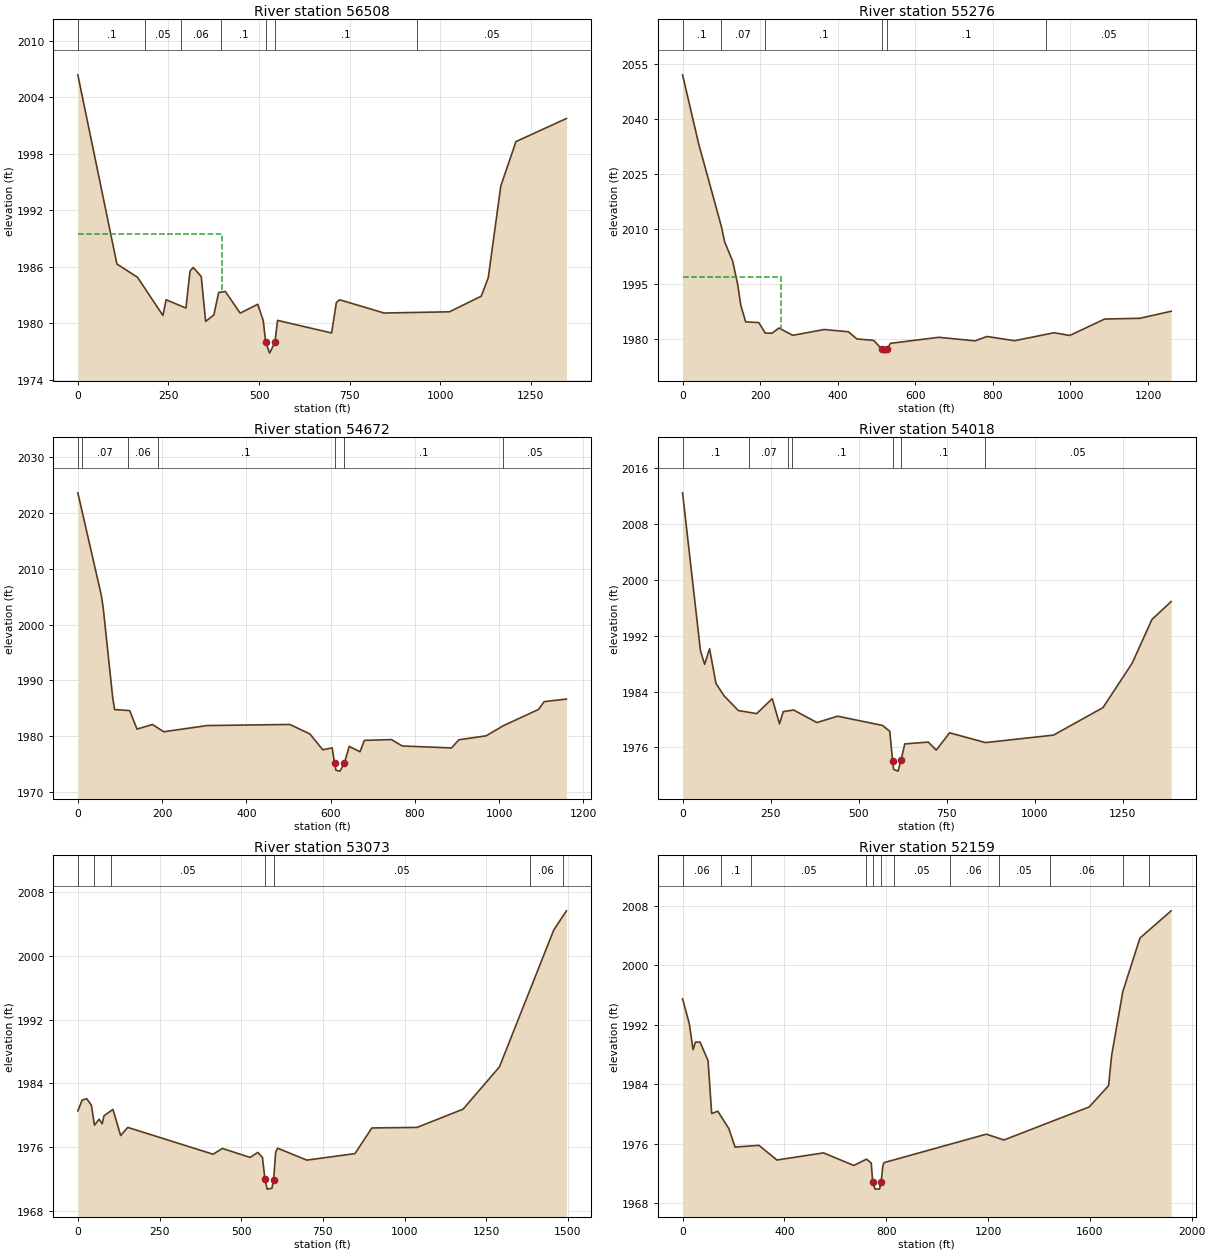
Type RM Length L Ch R = 1 ,56508   ,1232,1232,1232
XS GIS Cut Line= 4
2306788.97998668753487.9414013642306724.81134746753543.490109451
2305769.74586694753975.7187494022305664.73372428754163.243228862
#Sta/Elev= 30
       0  2006.4   107.8  1986.3   164.6 1984.89   234.8 1980.83   243.6  1982.5
   298.2 1981.62   309.5 1985.54   318.3 1985.93   340.5 1984.97   352.6  1980.2
   375.3 1980.89   388.5 1983.27     407 1983.38   447.9 1981.08   496.4 1982.02
   511.5 1980.29   518.21978.017     529 1976.83  543.831977.979     551 1980.31
   700.2 1978.97   713.4 1982.22   722.2  1982.5   845.1 1981.09  1025.2 1981.22
    1113 1982.88  1132.5 1984.85    1167 1994.59  1208.9 1999.31  1348.1 2001.76
#Mann= 7 ,-1,0
       0      .1       0  184.87     .05       0  284.87     .06       0
  394.87      .1       0   518.2    .045       0  543.83      .1       0
  934.87     .05       0
#XS Ineff= 2 , 0
          397.26 1989.48
Permanent Ineff=
       F       F
Bank Sta=518.2,543.83
XS Rating Curve= 0 ,0
Exp/Cntr(USF)=0,0
Exp/Cntr=0.3,0.1

Type RM Length L Ch R = 1 ,55276   ,603.5,603.5,603.5
XS GIS Cut Line= 4
2306344.34476378752975.3054337412306169.47636455753026.426693669
2306001.76844858753204.6772792922305439.73642642753818.963130766
#Sta/Elev= 30
       0 2052.16    41.9 2033.17   100.2 2010.71   108.5 2006.54   129.4 2001.22
   141.9 1994.99   150.2 1989.21   162.7  1984.7   196.4 1984.52   213.3 1981.63
   230.8 1981.62   248.3 1983.03   284.1 1981.03     365 1982.62   427.6    1982
   449.3 1980.05   492.7 1979.65   513.4  1977.3   521.8 1976.17   527.51977.318
     536 1978.85   660.6 1980.49     754 1979.52   784.8 1980.71   855.9 1979.56
   957.9 1981.74   998.2 1980.99  1088.1 1985.48  1178.7 1985.68  1259.5  1987.6
#Mann= 6 ,-1,0
       0      .1       0     100     .07       0  212.19      .1       0
   513.4    .045       0   527.5      .1       0  936.93     .05       0
#XS Ineff= 2 , 0
          253.72  1996.9
Permanent Ineff=
       F       F
Bank Sta=513.4,527.5
XS Rating Curve= 0 ,0
Exp/Cntr(USF)=0,0
Exp/Cntr=0.3,0.1

Type RM Length L Ch R = 1 ,54672   ,654,654,654
XS GIS Cut Line= 2
2306157.79572968752781.8957502892305125.08254804753309.179945203
#Sta/Elev= 30
       0 2023.62    55.7 2005.26    60.2    2003    82.7 1986.91    87.2 1984.76
   123.1 1984.57   140.4 1981.26     177 1982.08   203.9 1980.78   306.9 1981.89
   503.1 1982.09   550.7 1980.39   581.2 1977.55   603.6 1977.89  609.221975.121
   612.6 1973.87   622.1 1973.72   632.61975.174   644.1 1978.16   669.6 1977.19
     680 1979.23     744 1979.38   769.8 1978.23   886.7 1977.88   904.4 1979.34
   968.9 1980.05    1010 1981.87  1093.2 1984.78  1106.7 1986.18  1159.5 1986.64
#Mann= 7 ,-1,0
       0      .1       0      10     .07       0     120     .06       0
     190      .1       0  609.22    .045       0   632.6      .1       0
    1010     .05       0
Bank Sta=609.22,632.6
XS Rating Curve= 0 ,0
Exp/Cntr(USF)=0,0
Exp/Cntr=0.3,0.1

Type RM Length L Ch R = 1 ,54018   ,945.3,945.3,945.3
XS GIS Cut Line= 3
2306019.72388924752231.8764020052304899.64061415752834.669472132
2304801.87795459752895.613331405
#Sta/Elev= 30
       0 2012.47    50.8 1989.85    62.6  1987.9    76.7 1990.13    94.9 1985.16
   117.6  1983.4   158.5 1981.28   210.3 1980.84   254.6 1982.97   275.3 1979.37
   285.7 1981.12   315.1 1981.36   381.6 1979.56   440.1 1980.47   567.6 1979.15
   588.3 1978.31   596.31974.119   599.1 1972.86   611.9  1972.6   620.41974.186
   630.9  1976.5   697.6 1976.76   720.2 1975.61   758.1 1978.09     860 1976.69
  1053.3 1977.76  1193.7  1981.7  1276.7 1988.08  1332.6 1994.32  1387.2 1996.89
#Mann= 7 ,-1,0
       0      .1       0     190     .07       0     300     .06       0
     310      .1       0   596.3    .045       0   620.4      .1       0
     860     .05       0
Bank Sta=596.3,620.4
XS Rating Curve= 0 ,0
Exp/Cntr(USF)=0,0
Exp/Cntr=0.3,0.1

Type RM Length L Ch R = 1 ,53073   ,914.5,914.5,914.5
XS GIS Cut Line= 3
2305499.30035114751733.7692877972304554.93072994 752323.82260364
  2304421.432648752681.349819603
#Sta/Elev= 30
       0 1980.52    13.1 1981.89    27.3 1982.06    41.4 1981.25    50.9 1978.74
      65 1979.49    74.4 1978.91    80.2 1979.93   107.5 1980.72     131 1977.44
   152.8 1978.46     414 1975.09   442.3 1975.82   527.2 1974.69   550.8 1975.32
     565 1974.69   572.6 1971.98   579.5 1970.71     594 1970.82  598.961971.895
   605.6 1975.37   611.4 1975.85   700.9 1974.35     848 1975.17   899.8 1978.39
  1038.2 1978.46  1178.9 1980.75  1290.1 1986.05  1456.6 2003.26  1495.2 2005.65
#Mann= 7 ,-1,0
       0     .05       0      50     .07       0     100     .05       0
   572.6    .045       0  598.96     .05       0 1383.55     .06       0
 1483.55     .05       0
Bank Sta=572.6,598.96
XS Rating Curve= 0 ,0
Exp/Cntr(USF)=0,0
Exp/Cntr=0.3,0.1

Type RM Length L Ch R = 1 ,52159   ,480.2,480.2,480.2
XS GIS Cut Line= 3
2305296.16419735751285.0659283652304376.57869414751795.729670224
2304362.79030335752662.948590832
#Sta/Elev= 30
       0 1995.47    26.6 1992.12    41.3 1988.63    50.3 1989.65    68.6 1989.66
   100.1 1987.17   114.4 1980.06   138.3 1980.38   181.5 1978.06   206.2 1975.56
   300.1 1975.79   370.6 1973.82   553.6 1974.78   672.6 1973.09   722.9 1973.94
   741.2  1973.4  747.051970.801   756.1 1969.91   773.8 1969.92   779.6 1970.81
     787 1973.09   791.5 1973.47  1193.3 1977.29  1262.4 1976.51  1597.4 1980.95
  1673.4 1983.81  1685.4 1987.86  1729.4 1996.46  1796.8 2003.64  1919.2 2007.29
#Mann= 12 ,-1,0
       0     .06       0     150      .1       0     270     .05       0
     720      .1       0  747.05    .045       0   779.6      .1       0
     830     .05       0    1050     .06       0 1241.86     .05       0
 1441.86     .06       0 1731.86     .05       0 1831.86     .06       0
Bank Sta=747.05,779.6
XS Rating Curve= 0 ,0
Exp/Cntr(USF)=0,0
Exp/Cntr=0.3,0.1

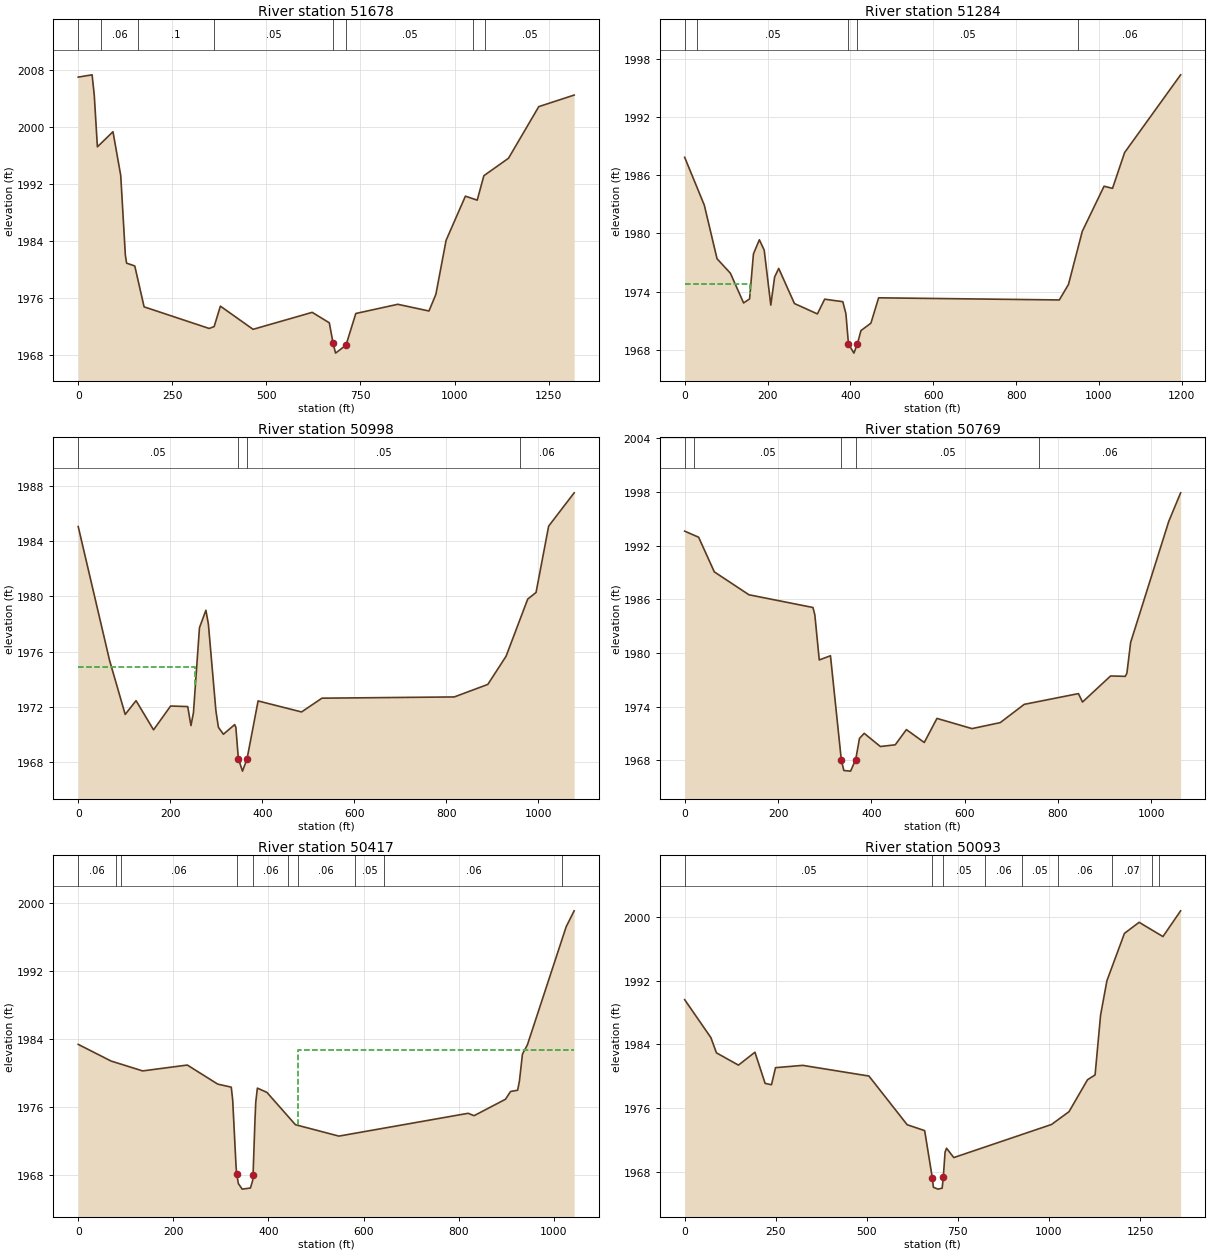
Type RM Length L Ch R = 1 ,51678   ,394,394,394
XS GIS Cut Line= 2
2305217.49367952751125.3683724622303943.07177809751461.132935013
#Sta/Elev= 30
       0 2006.94    36.9 2007.26    42.7 2004.38      51 1997.16    92.4 1999.28
     113 1993.14   125.3 1981.96   128.6 1980.84   150.3 1980.45   175.1 1974.71
     348 1971.68   361.2 1971.94   377.8 1974.81   464.7 1971.56   621.8 1973.94
   667.3 1972.47677.37991969.582   683.9 1968.22   711.6 1969.34   737.7 1973.78
   849.3 1975.07   932.1 1974.13   950.4 1976.46   977.6 1984.04  1028.9 1990.24
  1060.3 1989.68    1078 1993.11  1143.5 1995.56  1223.9  2002.8  1317.9 2004.42
#Mann= 8 ,-1,0
       0     .05       0      60     .06       0     160      .1       0
     360     .05       0677.3799    .045       0   711.6     .05       0
    1050     .06       0    1080     .05       0
Bank Sta=677.3799,711.6
XS Rating Curve= 0 ,0
Exp/Cntr(USF)=0,0
Exp/Cntr=0.3,0.1

Type RM Length L Ch R = 1 ,51284   ,286.5,286.5,286.5
XS GIS Cut Line= 2
2304991.01335509750733.0260433272303960.89145267751343.133932272
#Sta/Elev= 30
       0 1987.84    47.4 1982.91    78.1 1977.39   110.3  1975.9   142.3 1972.83
   156.7 1973.25     166 1977.89   180.3 1979.34     192 1978.27   207.9 1972.61
   217.1  1975.5     227 1976.39     265 1972.77   320.4  1971.7   337.9 1973.22
   381.7 1972.96   389.2 1971.73395.39821968.611   408.5 1967.66417.0981 1968.64
   425.5 1969.98   449.6 1970.75   468.2 1973.36   904.4 1973.14   926.5 1974.74
   959.8 1980.21  1012.4 1984.86  1032.8 1984.64    1062 1988.33  1197.2 1996.34
#Mann= 5 ,-1,0
       0     .06       0      30     .05       0395.3982    .045       0
417.0981     .05       0     950     .06       0
#XS Ineff= 2 , 0
          157.69 1974.83
Permanent Ineff=
       T       F
Bank Sta=395.3982,417.0981
XS Rating Curve= 0 ,0
Exp/Cntr(USF)=0,0
Exp/Cntr=0.3,0.1

Type RM Length L Ch R = 1 ,50998   ,228.9,228.9,228.9
XS GIS Cut Line= 2
2304727.73561584750440.4249534062304000.33169071  751235.5897462
#Sta/Elev= 30
       0 1985.08    68.2 1975.35   102.1 1971.43   125.7 1972.43   163.7 1970.31
   200.8 1972.04     238    1972     245 1970.62   250.4 1971.55   263.5 1977.73
   277.5    1979   282.9 1977.99   299.2  1971.7   304.6  1970.5   315.5 1969.99
     340 1970.69   342.6 1970.49     348 1968.22     357 1967.31   366.8 1968.19
   390.9 1972.41   485.3 1971.61   529.7 1972.61   817.2  1972.7   890.1 1973.61
   929.8 1975.66   976.8 1979.81   994.9 1980.29  1022.3 1985.11  1077.7 1987.53
#Mann= 4 ,-1,0
       0     .05       0     348    .045       0   366.8     .05       0
     960     .06       0
#XS Ineff= 2 , 0
          254.73 1974.87
Permanent Ineff=
       T       F
Bank Sta=348,366.8
XS Rating Curve= 0 ,0
Exp/Cntr(USF)=0,0
Exp/Cntr=0.3,0.1

Type RM Length L Ch R = 1 ,50769   ,352,352,352
XS GIS Cut Line= 3
2304495.89043255750292.1607031522304022.25245921751012.580921502
2303902.69335914751173.525863899
#Sta/Elev= 30
       0 1993.62    29.9 1992.94    63.5 1989.07   137.8 1986.51   274.9 1985.09
   278.9 1984.27   288.4 1979.23   312.4  1979.7   335.71968.031   341.1 1966.88
   355.5 1966.81  366.44  1968.1   374.6 1970.47   384.7 1971.03   419.3 1969.56
   451.2 1969.75   475.1 1971.45   513.4 1970.01   540.6  1972.7   615.7 1971.56
   676.2 1972.23   727.6 1974.27   843.7 1975.47   852.5 1974.53   912.6 1977.44
   944.1  1977.4   947.6 1977.75   955.6 1981.19  1037.3 1994.71  1062.7  1997.9
#Mann= 5 ,-1,0
       0     .07       0      20     .05       0   335.7    .045       0
  366.44     .05       0     760     .06       0
Bank Sta=335.7,366.44
XS Rating Curve= 0 ,0
Exp/Cntr(USF)=0,0
Exp/Cntr=0.3,0.1

Type RM Length L Ch R = 1 ,50417   ,323.7,323.7,323.7
XS GIS Cut Line= 6
2304212.95837694750234.5376999982304129.40242847750418.789278687
2304000.85481543750568.7614938992303985.85759391750778.722595196
2304014.58841433750972.7278881462303868.54512449751154.193337508
#Sta/Elev= 30
       0 1983.37    69.1 1981.41   135.5 1980.25   229.4 1980.94   293.3  1978.7
   321.8 1978.34   324.8 1976.83   331.8 1969.08   333.3 1968.09   336.8    1967
   344.8 1966.36   362.1 1966.49   366.7 1967.35   367.6 1968.03   371.7 1974.56
   373.3 1976.58   376.7 1978.23   396.7 1977.73   456.7 1973.93   548.1 1972.59
   819.8 1975.27   832.3 1974.99   898.3 1976.92     909 1977.83   923.8 1977.98
   927.6 1979.04     934 1982.22   944.3  1983.3    1026  1997.2  1042.7 1999.06
#Mann= 10 ,-1,0
       0     .06       0      80     .05       0      90     .06       0
   333.3    .045       0   367.6     .06       0  441.15     .05       0
  461.15     .06       0  581.48     .05       0  643.61     .06       0
 1017.99     .05       0
#XS Ineff= 2 , 0
                          461.81         1982.68
Permanent Ineff=
       F       F
Bank Sta=333.3,367.6
XS Rating Curve= 0 ,0
Exp/Cntr(USF)=0,0
Exp/Cntr=0.3,0.1

Type RM Length L Ch R = 1 ,50093   ,700.8,700.8,700.8
XS GIS Cut Line= 5
2303994.54112877749862.8240196162303814.21900252750039.127963571
2303739.46292182750363.3804253242303726.76439972 750901.64977806
2303537.66934026751046.260800218
#Sta/Elev= 30
       0 1989.62      72 1984.86    87.2 1982.95   147.6 1981.41   192.9 1983.03
   220.8 1979.12   238.3 1978.95   249.4 1981.09   324.1 1981.38   505.8 1980.04
   610.8 1973.93   658.8 1973.19   679.91967.233   682.8 1966.08   695.5 1965.85
   706.8 1965.97   709.91967.334   714.8 1970.49   718.8 1970.98   738.8 1969.81
  1006.9 1973.96  1055.1 1975.57  1105.9 1979.58  1126.6 1980.18  1141.7 1987.69
  1159.1    1992  1207.2 1997.94  1247.5 1999.33  1312.9 1997.54  1361.4 2000.77
#Mann= 9 ,-1,0
       0     .05       0   679.9    .045       0   709.9     .05       0
  824.95     .06       0  924.95     .05       0 1024.95     .06       0
 1173.37     .07       0 1283.37     .05       0 1303.37     .06       0
Bank Sta=679.9,709.9
XS Rating Curve= 0 ,0
Exp/Cntr(USF)=0,0
Exp/Cntr=0.3,0.1