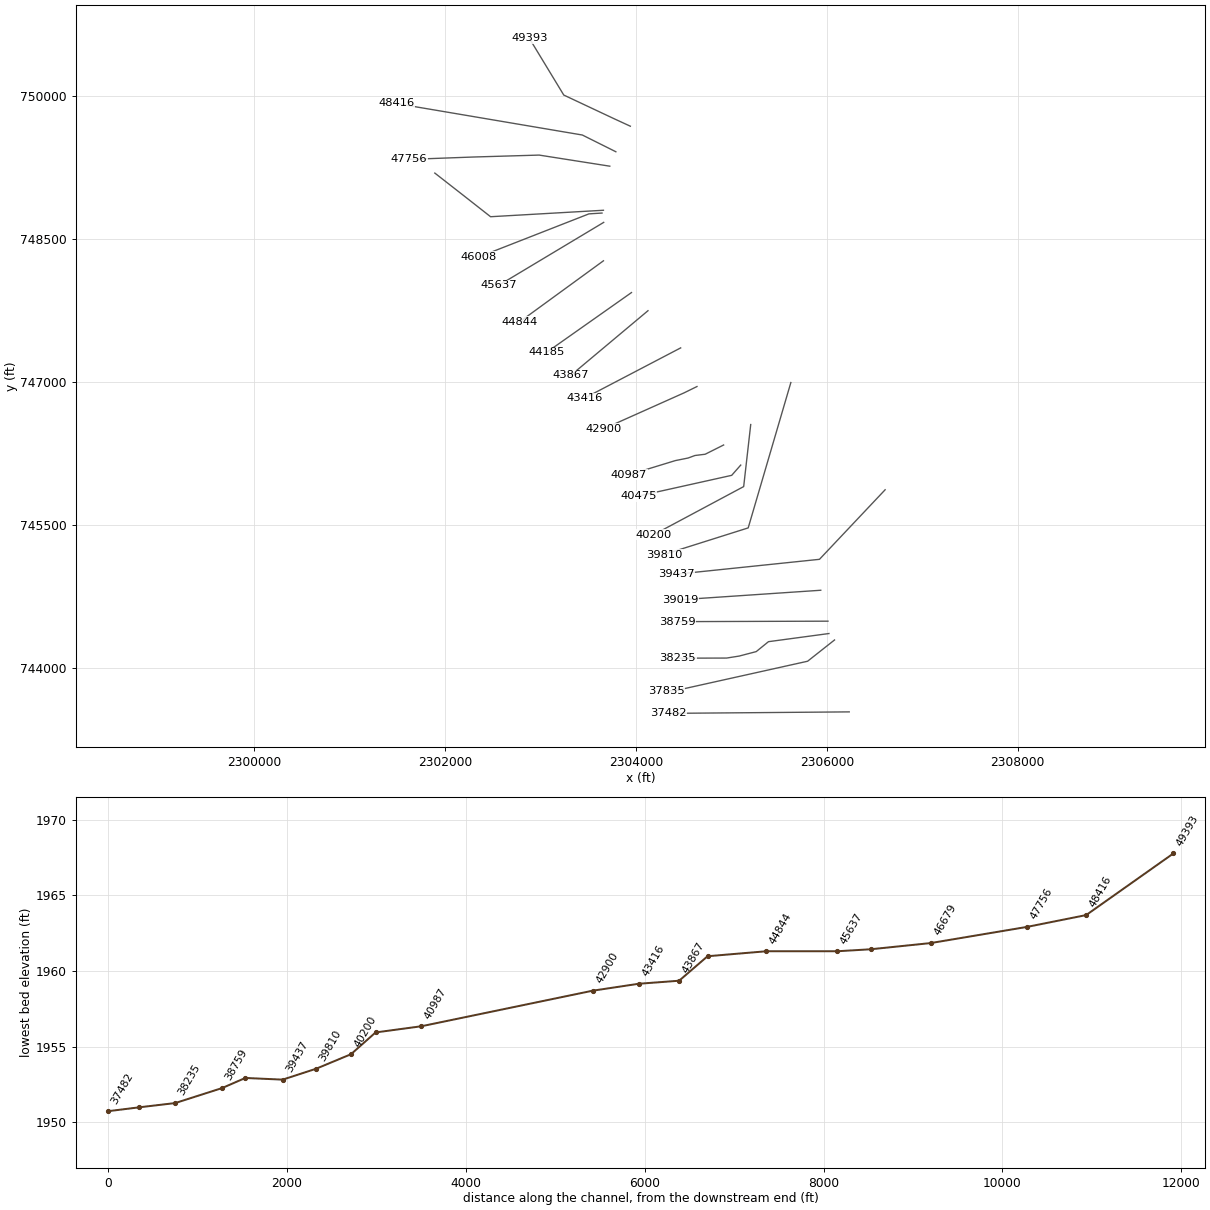
HEC-RAS study LEADNGCK.prj: LEADNGCK

--- LEADNGCK.g01 (geometry) --- (continued)

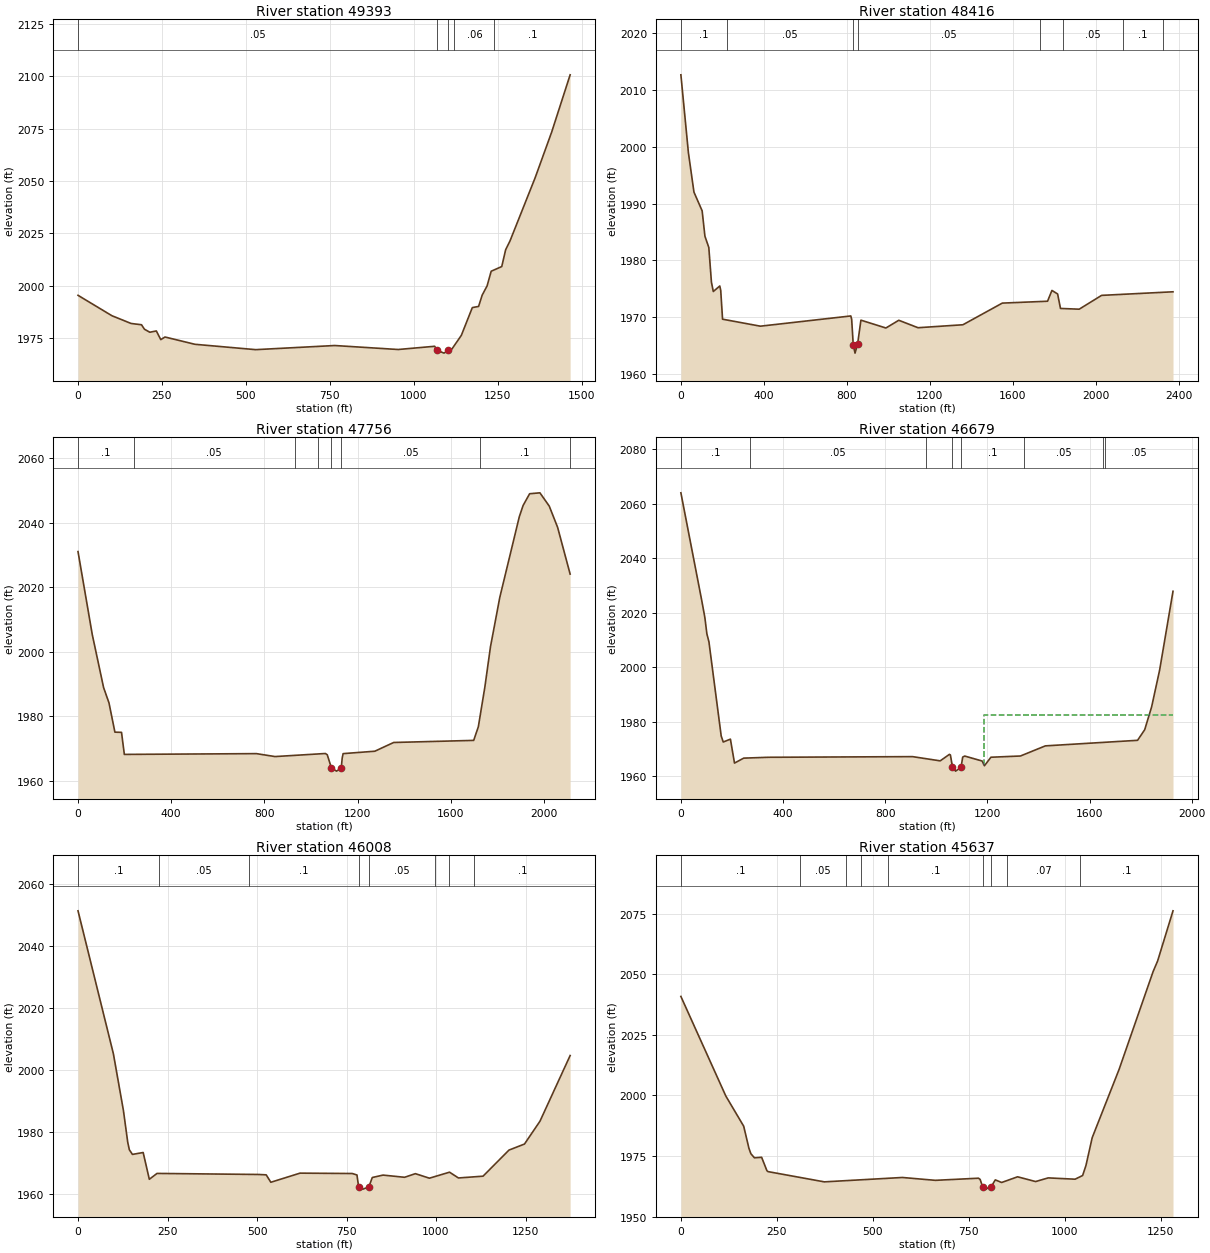
Type RM Length L Ch R = 1 ,49393   ,976,976,976
XS GIS Cut Line= 4
2303939.83167144 749684.792900872303772.92849618749761.766148407
2303242.05269083750011.6566606882302881.44618762750606.307602417
#Sta/Elev= 30
       0 1995.39   100.9 1985.65   158.2 1981.94   189.1 1981.33   197.9 1979.19
     214 1977.76   233.3 1978.37   246.5 1974.24   259.1 1975.48   348.2    1972
   529.1 1969.44   764.7 1971.41   953.6 1969.51  1062.4 1971.05  1070.61969.059
  1090.4 1967.78  1102.3 1969.04  1113.6 1969.69  1141.9 1976.27  1174.6 1989.52
  1193.3 1990.09    1204 1995.48  1218.6 1999.89  1230.8  2006.9  1262.3 2009.13
  1273.9 2017.17  1286.9 2021.38  1361.8 2051.56  1410.8 2073.27    1466  2100.7
#Mann= 5 ,-1,0
       0     .05       0  1070.6    .045       0  1102.3     .05       0
 1120.55     .06       0 1240.55      .1       0
Bank Sta=1070.6,1102.3
XS Rating Curve= 0 ,0
Exp/Cntr(USF)=0,0
Exp/Cntr=0.3,0.1

Type RM Length L Ch R = 1 ,48416   ,660.2,660.2,660.2
XS GIS Cut Line= 3
2303787.88802856749417.0326927752303436.68648067749592.520676528
2301484.81130367749923.184361241
#Sta/Elev= 30
       0 2012.66    36.1    1999      63 1992.02   102.5 1988.73   115.9 1984.26
   134.6 1982.29   147.2  1976.2   156.2 1974.54   187.5 1975.51     192 1974.75
   200.9 1969.67   383.3 1968.44   819.1 1970.24   823.2 1969.66 830.7921965.198
   839.4  1963.7   851.6 1965.22   867.8  1969.5   988.3 1968.12  1050.4 1969.48
    1143 1968.17  1359.5 1968.69  1549.4  1972.5  1767.5 1972.83  1788.7 1974.73
    1816 1974.11  1829.9 1971.56  1920.1 1971.43  2028.1 1973.86  2372.3 1974.49
#Mann= 8 ,-1,0
       0      .1       0     220     .05       0 830.792    .045       0
   851.6     .05       0  1732.6     .06       0  1842.6     .05       0
  2132.6      .1       0  2322.6     .05       0
Bank Sta=830.792,851.6
XS Rating Curve= 0 ,0
Exp/Cntr(USF)=0,0
Exp/Cntr=0.3,0.1

Type RM Length L Ch R = 1 ,47756   ,1077.7,1077.7,1077.7
XS GIS Cut Line= 4
 2303724.5640907749265.6749626372302983.98037023749382.096511464
2302288.27912146749361.6063280432301622.54340025749336.946978965
#Sta/Elev= 30
       0 2031.06    61.1 2005.32   109.7 1988.87   132.9  1984.1   158.3 1975.02
   186.7 1974.95   198.8 1968.11   765.5 1968.35   845.5 1967.44  1061.6 1968.39
  1069.6    1968 1087.681963.867  1109.6 1962.92  1129.6 1963.88  1133.7 1966.98
  1137.7 1968.35  1273.7  1969.1  1354.6 1971.81    1698 1972.46    1718  1976.7
    1746 1989.05    1770  2001.5    1810 2016.84  1893.9 2041.92  1910.1 2045.38
  1938.1 2049.02  1982.2  2049.3  2022.2 2045.19  2058.2 2038.58  2111.9 2024.08
#Mann= 8 ,-1,0
       0      .1       0     240     .05       0  929.68      .1       0
 1029.68     .05       0 1087.68    .045       0  1129.6     .05       0
 1725.68      .1       0 2111.87     .06       0
Bank Sta=1087.68,1129.6
XS Rating Curve= 0 ,0
Exp/Cntr(USF)=0,0
Exp/Cntr=0.3,0.1

Type RM Length L Ch R = 1 ,46679   ,670.7,670.7,670.7
XS GIS Cut Line= 4
2303657.77231216748803.5282562182302475.19858029748735.735972204
 2302194.9103701748955.7347016442301890.76662336749193.440822955
#Sta/Elev= 30
       0 2064.01    81.7 2024.46    93.8 2018.27   101.8 2012.23   109.8 2009.32
   157.9 1974.71   165.9 1972.54   193.9 1973.59   209.9 1964.81     246 1966.62
   342.2 1966.93   907.1 1967.17  1015.3 1965.62  1051.3    1968  1055.3 1967.79
  1063.3 1963.34  1075.4 1961.85 1096.721963.235  1103.4 1967.01  1111.4 1967.38
  1179.5 1965.56  1188.4 1963.81  1213.8 1966.95  1329.4  1967.4    1427 1971.12
    1788 1973.16    1816 1977.06    1843 1985.41  1874.4 1998.93  1926.8 2027.88
#Mann= 8 ,-1,0
       0      .1       0     270     .05       0     960      .1       0
  1063.3    .045       0 1096.72      .1       0 1344.52     .05       0
 1650.83      .1       0 1660.83     .05       0
#XS Ineff= 2 , 0
                         1187.63         1982.55
Permanent Ineff=
       F       F
Bank Sta=1063.3,1096.72
XS Rating Curve= 0 ,0
Exp/Cntr(USF)=0,0
Exp/Cntr=0.3,0.1

Type RM Length L Ch R = 1 ,46008   ,371.2,371.2,371.2
XS GIS Cut Line= 3
 2303642.8514042748774.2153314062303505.95817109748765.669609024
 2302353.6765049748314.308182677
#Sta/Elev= 30
       0 2051.46    98.9 2005.17   126.9 1986.82   138.9 1976.59   143.4 1974.17
     152 1972.67     182 1973.28   199.2 1964.62   220.7 1966.52   504.2 1966.18
   525.7 1966.06   538.6 1963.66   620.2 1966.61   766.3 1966.49   779.2 1966.01
   783.91962.187   796.2 1961.44   812.31962.155   822.1  1965.2     852 1965.98
   912.3 1965.27   942.4 1966.44   981.6 1964.98  1037.8 1966.92  1062.7 1965.05
  1131.4 1965.63  1203.9 1974.07  1247.1 1976.02  1290.4  1983.4  1374.7 2004.65
#Mann= 8 ,-1,0
       0      .1       0  227.16     .05       0  477.16      .1       0
   783.9    .045       0   812.3     .05       0  997.16      .1       0
 1037.16     .05       0 1107.16      .1       0
Bank Sta=783.9,812.3
XS Rating Curve= 0 ,0
Exp/Cntr(USF)=0,0
Exp/Cntr=0.3,0.1

Type RM Length L Ch R = 1 ,45637   ,792.8,792.8,792.8
XS GIS Cut Line= 2
2303660.48235399748676.3824544852302561.48231797 748016.85256862
#Sta/Elev= 30
       0 2040.88     117 1999.77   163.6 1987.29   177.2 1978.17   182.3 1975.93
   191.6 1974.24   210.3 1974.45   224.1  1968.9     227 1968.54   373.6 1964.31
   576.9 1966.12   662.8 1964.94   775.1 1965.82   779.4 1965.32   785.61962.378
   793.4 1961.31     8081962.302   818.9 1965.13   835.4 1964.05   876.9  1966.4
   923.8 1964.44   956.7 1965.95  1026.7 1965.41  1046.3 1966.93    1055 1971.08
  1071.2 1982.54  1141.2 2010.72  1229.9 2051.16  1241.6 2055.52  1281.7 2076.24
#Mann= 9 ,-1,0
       0      .1       0     310     .05       0     430      .1       0
     470     .05       0     540      .1       0   785.6    .045       0
     808      .1       0     850     .07       0    1040      .1       0
Bank Sta=785.6,808
XS Rating Curve= 0 ,0
Exp/Cntr(USF)=0,0
Exp/Cntr=0.3,0.1

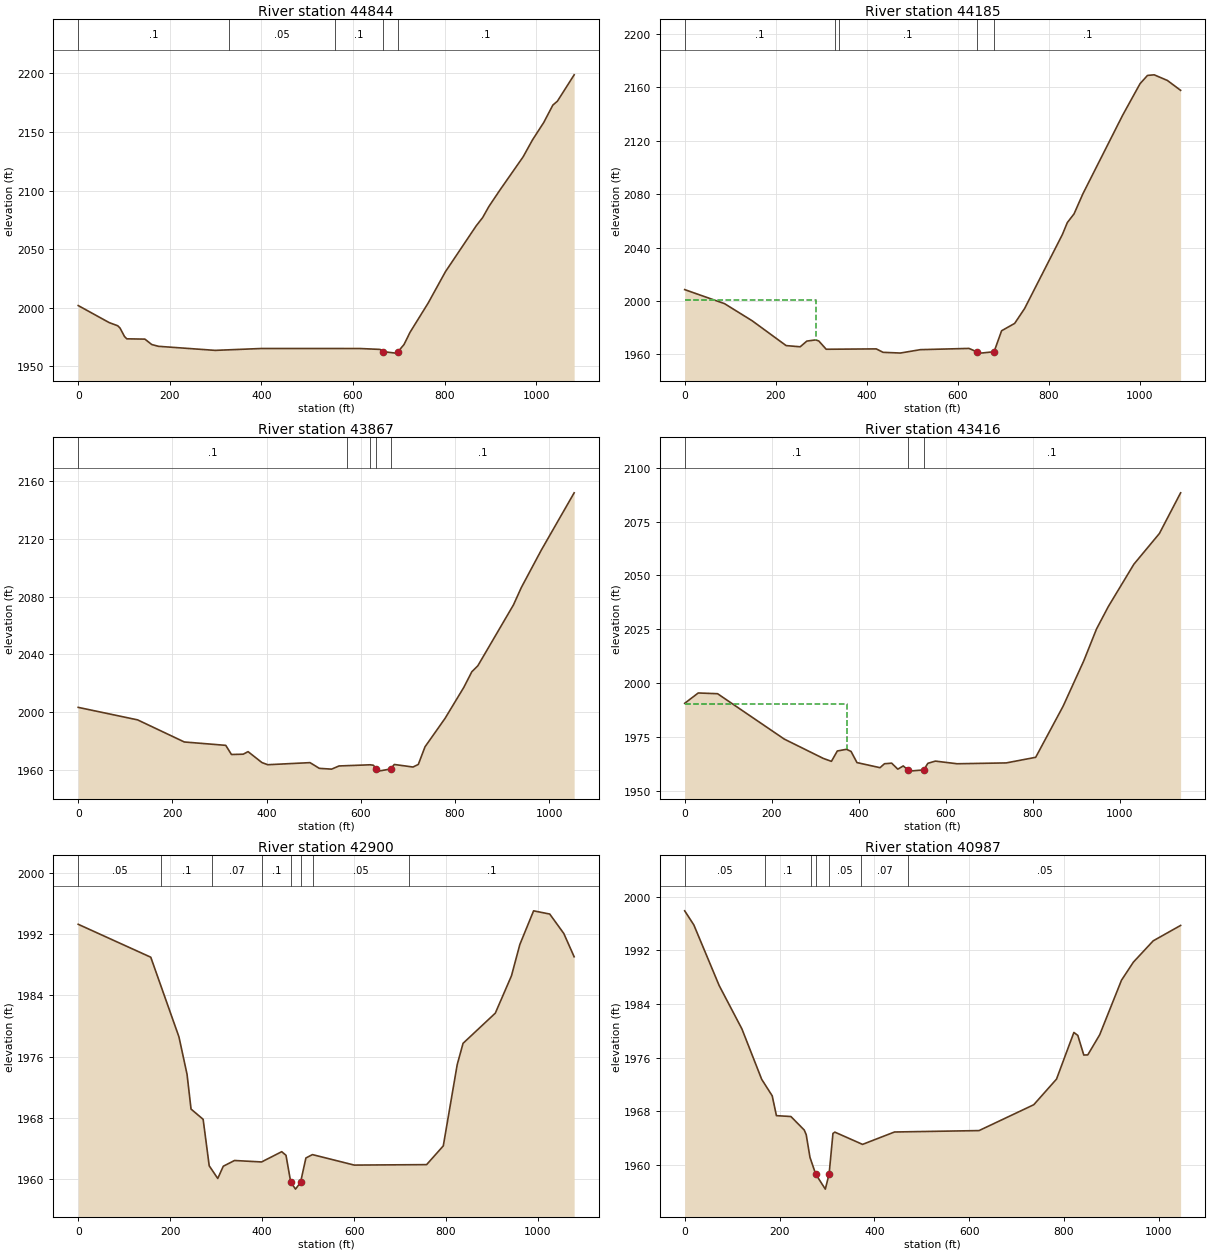
Type RM Length L Ch R = 1 ,44844   ,658.3,658.3,658.3
XS GIS Cut Line= 2
  2303657.883173 748273.511642512302782.57904454747635.507477943
#Sta/Elev= 30
       0 2001.91    67.3 1987.43    86.3 1984.66    91.2 1982.79   101.1  1975.5
   106.1 1973.52   145.7 1973.26   160.5 1968.66   175.4 1967.12   299.1 1963.66
   399.4 1965.25   615.9 1965.23   659.3 1964.48   665.91962.586   693.2 1961.31
   698.41962.564   711.5 1968.62   724.8 1979.16   764.4 2004.12   801.9 2030.73
   868.9 2069.77   883.3 2077.01     897 2086.51   920.5 2100.19   971.7 2128.84
     992 2143.19  1016.8  2158.2  1036.6 2172.98  1046.5 2176.29  1083.1  2198.8
#Mann= 5 ,-1,0
       0      .1       0     330     .05       0     560      .1       0
   665.9    .045       0   698.4      .1       0
Bank Sta=665.9,698.4
XS Rating Curve= 0 ,0
Exp/Cntr(USF)=0,0
Exp/Cntr=0.3,0.1

Type RM Length L Ch R = 1 ,44185   ,318.2,318.2,318.2
XS GIS Cut Line= 2
 2303951.6696109747940.4425524022303060.70120461 747312.41930931
#Sta/Elev= 30
       0 2008.57    87.5 1998.07   148.4 1985.21     223 1966.63   253.9 1965.73
   268.5 1969.99   288.1 1970.89   294.8 1970.08   311.1 1963.88   421.1 1964.15
   436.1 1961.58   474.1 1961.05   518.1 1963.58   624.9 1964.51   642.1 1961.97
   650.7 1960.98   680.11962.033   696.6 1977.74   725.3 1983.24   747.2 1994.41
   830.1 2049.76   841.1  2058.8   855.8 2065.27   875.4 2080.42   962.7 2139.23
  1000.9 2162.84  1017.3 2169.03    1032 2169.49    1061 2165.28  1090.1 2157.87
#Mann= 5 ,-1,0
       0      .1       0     330     .05       0     340      .1       0
   642.1    .045       0   680.1      .1       0
#XS Ineff= 2 , 0
          289.39 2000.86
Permanent Ineff=
       F       F
Bank Sta=642.1,680.1
XS Rating Curve= 0 ,0
Exp/Cntr(USF)=0,0
Exp/Cntr=0.3,0.1

Type RM Length L Ch R = 1 ,43867   ,451,451,451
XS GIS Cut Line= 2
2304124.60597224747750.1740892372303317.47573056747073.733920814
#Sta/Elev= 30
       0 2003.43   126.1 1994.79   225.3 1979.51   313.3 1977.18   325.4 1970.86
   350.3 1971.06   360.7 1972.82     390 1965.31   402.4 1963.79   492.2 1965.23
     512 1961.28   538.1 1960.73   553.8 1962.93     620 1963.74   626.8 1963.44
   632.91960.886   637.3 1959.36   663.4 1960.84   671.1 1963.96   710.9  1962.2
   722.2 1963.99   736.4 1976.16     779 1995.84   818.8 2017.26   835.8 2028.04
   848.5 2032.14   924.3 2074.31   940.8 2086.19   983.4 2112.16  1053.1 2151.73
#Mann= 5 ,-1,0
       0      .1       0     570     .08       0     620      .1       0
   632.9    .045       0   663.4      .1       0
Bank Sta=632.9,663.4
XS Rating Curve= 0 ,0
Exp/Cntr(USF)=0,0
Exp/Cntr=0.3,0.1

Type RM Length L Ch R = 1 ,43416   ,515.9,515.9,515.9
XS GIS Cut Line= 2
2304467.13021889747360.3104697132303456.90240876746831.802680328
#Sta/Elev= 30
       0 1990.63    31.2 1995.43    75.6 1995.09   229.1 1974.01   318.7 1965.06
   337.4  1963.7   350.9 1968.51     372 1969.29   382.5  1968.3   396.1 1963.12
   449.1 1960.76   459.3 1962.59   475.8 1962.86     490 1960.07   502.4 1961.57
   513.5  1959.7   515.9 1959.16   549.6 1959.72     559 1962.78   576.3 1963.81
   626.3 1962.58   739.2 1962.97   806.9 1965.57   870.1 1989.34   917.4 2010.32
   946.8 2025.15   973.9 2035.53  1032.6 2055.17  1091.3 2069.44  1140.1 2088.32
#Mann= 3 ,-1,0
       0      .1       0   513.5    .045       0   549.6      .1       0
#XS Ineff= 2 , 0
          372.56 1990.21
Permanent Ineff=
       F       F
Bank Sta=513.5,549.6
XS Rating Curve= 0 ,0
Exp/Cntr(USF)=0,0
Exp/Cntr=0.3,0.1

Type RM Length L Ch R = 1 ,42900   ,1913.5,1913.5,1913.5
XS GIS Cut Line= 3
2304637.91434656746955.0613615652304502.87644006746888.776860515
2303655.65921943746509.639142816
#Sta/Elev= 30
       0  1993.3   157.8    1989   219.1 1978.59   236.7  1973.7   245.4 1969.16
   271.7 1967.82   284.9 1961.75   303.5 1960.09   315.5 1961.69   339.9 1962.44
   398.8 1962.25   442.6 1963.59   451.9 1963.12   462.21959.621   472.6  1958.7
   483.51959.574   495.2 1962.77   509.4 1963.21   600.4 1961.84   757.7  1961.9
     794 1964.35   824.3 1974.98     837 1977.75   907.1 1981.69   942.2 1986.56
   960.5 1990.66   990.4 1995.06  1025.5 1994.64  1056.1  1992.1  1078.6 1989.06
#Mann= 8 ,-1,0
       0     .05       0  180.43      .1       0  290.43     .07       0
  400.43      .1       0   462.2    .045       0   483.5      .1       0
  510.43     .05       0  720.43      .1       0
Bank Sta=462.2,483.5
XS Rating Curve= 0 ,0
Exp/Cntr(USF)=0,0
Exp/Cntr=0.3,0.1

Type RM Length L Ch R = 1 ,40987   ,512.1,512.1,512.1
BEGIN DESCRIPTION:
Structure
END DESCRIPTION:
XS GIS Cut Line= 6
2304917.19255861746342.0822374462304723.41881439746244.975790497
2304617.35904408746232.0641662852304544.50059317746205.318658989
2304411.69531556746178.5731516932303924.89066621 746029.58611512
#Sta/Elev= 30
       0  1997.9    19.3  1995.8    72.7 1986.75   120.7 1980.27   162.4 1972.75
   184.6 1970.28   193.5 1967.32     224 1967.19   252.2 1965.17   256.3 1964.48
   264.3 1961.08   276.4 1958.58   296.6 1956.35   304.6 1958.61   312.7 1964.66
   316.7 1964.86   375.1 1963.03   442.5 1964.88   620.8 1965.09   736.2 1968.95
   784.2 1972.78   820.8 1979.74   829.1  1979.3   841.7 1976.37   850.1 1976.39
   875.2 1979.39   921.2 1987.54   946.3 1990.24   988.1 1993.42  1045.9 1995.72
#Mann= 7 ,-1,0
       0     .05       0     170      .1       0  266.74     .05       0
   276.4    .045       0   304.6     .05       0  372.06     .07       0
  471.35     .05       0
Bank Sta=276.4,304.6
XS Rating Curve= 0 ,0
Exp/Cntr(USF)=0,0
Exp/Cntr=0.3,0.1

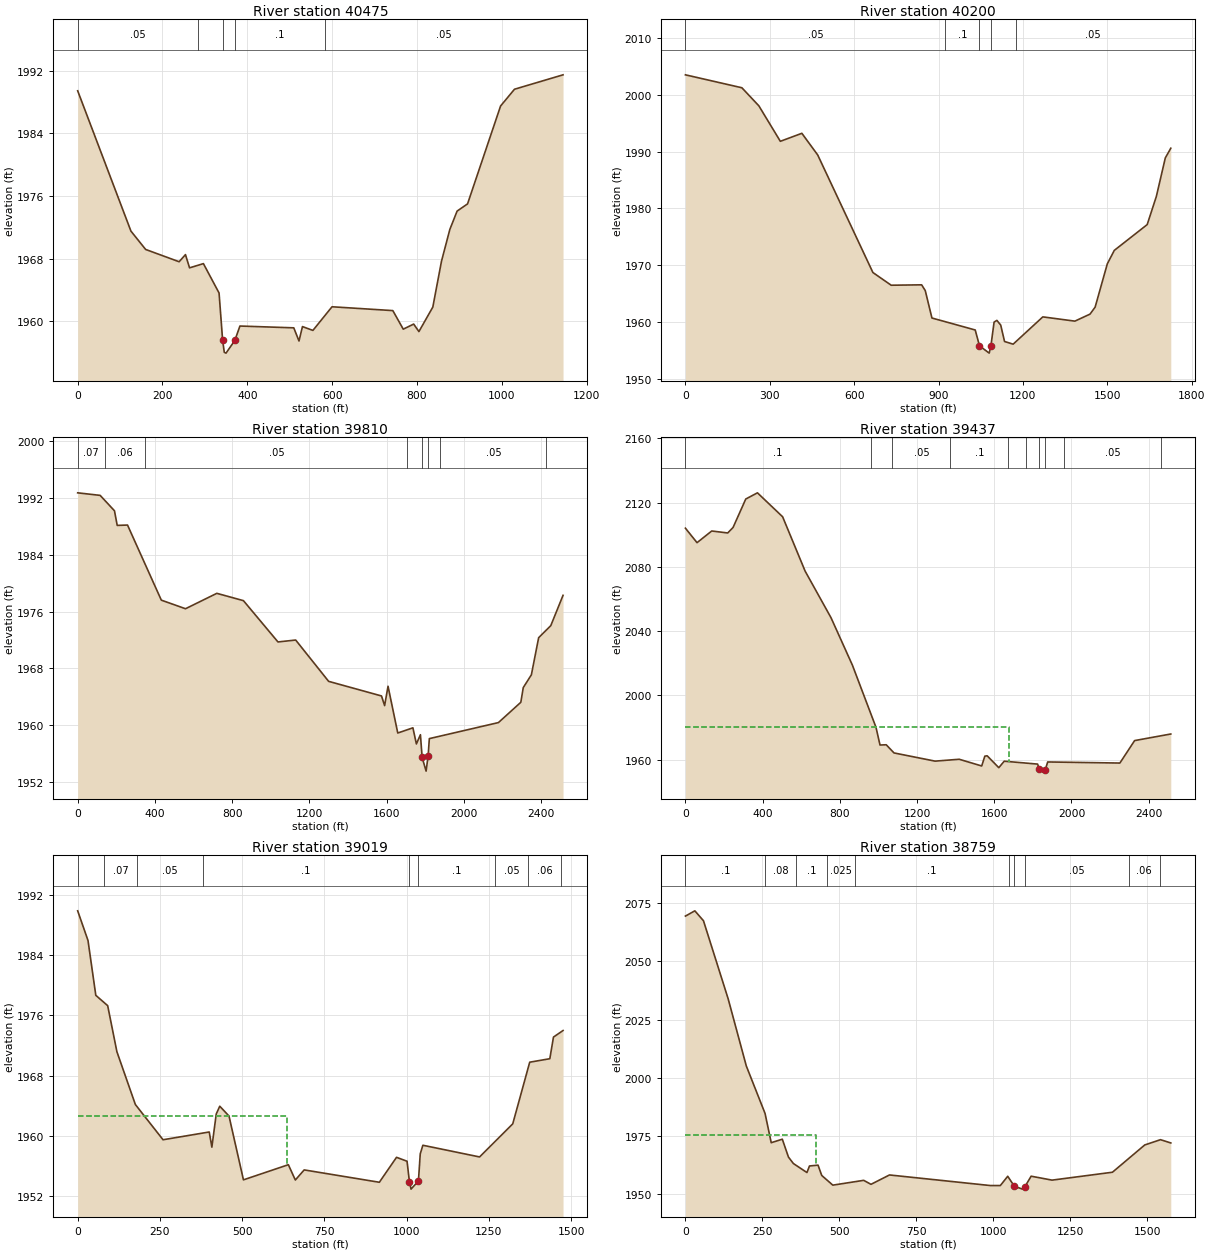
Type RM Length L Ch R = 1 ,40475   ,274.8,274.8,274.8
XS GIS Cut Line= 3
 2305096.4870997746131.4212957162305001.75860438746023.899724813
2304024.37854742745806.415108513
#Sta/Elev= 30
       0 1989.44   125.6 1971.52   160.3 1969.18   239.2 1967.61   254.2 1968.52
   263.8 1966.83   296.5 1967.37   333.4 1963.62   341.81957.592   345.7 1956.04
   349.8 1955.94   370.61957.559   382.6  1959.4   509.6 1959.17   521.9 1957.49
   530.1 1959.33   554.7 1958.84   599.8 1961.86   743.2 1961.37   767.8    1959
   792.4 1959.65   804.7 1958.69   837.5 1961.82   857.9 1967.67   877.6 1971.73
   894.8 1974.08   919.4    1975   997.3  1987.5  1030.1 1989.64  1144.6 1991.48
#Mann= 5 ,-1,0
       0     .05       0   283.3      .1       0   341.8    .045       0
   370.6      .1       0   583.3     .05       0
Bank Sta=341.8,370.6
XS Rating Curve= 0 ,0
Exp/Cntr(USF)=0,0
Exp/Cntr=0.3,0.1

Type RM Length L Ch R = 1 ,40200   ,389.8,389.8,389.8
XS GIS Cut Line= 3
2305201.25801875746556.554538529 2305127.4430517745906.005584014
2304182.94193918745400.804491626
#Sta/Elev= 30
       0 2003.56   200.7 2001.28     261  1998.1   337.5 1991.84     414 1993.25
   470.4 1989.43   666.6 1968.71   731.6 1966.47   839.9 1966.54   852.8 1965.52
   876.5 1960.69  1030.4 1958.581045.6081955.786  1080.1  1954.5  1086.3 1955.82
  1097.5 1959.97  1107.5 1960.27  1121.1 1959.44  1134.7 1956.55  1165.3 1956.08
  1270.8 1960.89  1384.8 1960.14  1438.7 1961.38  1456.8 1962.61    1500 1970.23
  1524.9 1972.61  1641.9 1977.16  1674.6 1982.15  1706.3 1988.91  1725.8 1990.62
#Mann= 5 ,-1,0
       0     .05       0  924.72      .1       01045.608    .045       0
  1086.3      .1       0 1174.72     .05       0
Bank Sta=1045.608,1086.3
XS Rating Curve= 0 ,0
Exp/Cntr(USF)=0,0
Exp/Cntr=0.3,0.1

Type RM Length L Ch R = 1 ,39810   ,373.4,373.4,373.4
XS GIS Cut Line= 3
2305621.79795008746996.9460126192305174.85705753745472.783370398
2304291.70575351745193.645755048
#Sta/Elev= 30
       0 1992.75   116.5 1992.39   190.6 1990.22   204.8 1988.16   258.2 1988.21
   433.3 1977.63   558.7 1976.42   720.9 1978.59   858.7 1977.56  1037.7 1971.74
  1129.4 1972.01  1300.1 1966.19  1574.1 1964.13  1590.2 1962.77  1607.9  1965.5
  1658.3 1958.91  1736.8 1959.64  1754.8 1957.37  1775.7 1958.67  1784.6 1955.47
  1805.1 1953.54 1815.651955.726  1821.9 1958.12  2179.9 1960.38  2295.9 1963.24
  2308.5 1965.31  2350.5 1967.11  2388.2 1972.34  2451.1 1974.04  2514.6 1978.31
#Mann= 8 ,-1,0
       0     .07       0     140     .06       0     350     .05       0
 1708.34      .1       0  1784.6    .045       0 1815.65      .1       0
 1878.34     .05       0 2428.34     .06       0
Bank Sta=1784.6,1815.65
XS Rating Curve= 0 ,0
Exp/Cntr(USF)=0,0
Exp/Cntr=0.3,0.1

Type RM Length L Ch R = 1 ,39437   ,417.7,417.7,417.7
XS GIS Cut Line= 3
2306609.73205534745872.6083395032305921.73177243 745143.23625697
2304417.78774266744986.769983755
#Sta/Elev= 30
       0 2104.12    60.1  2095.1   136.3 2102.37   219.2 2101.14   246.9 2104.58
   312.6 2122.28   373.1 2126.14   503.6 2111.22   620.2 2077.37   754.3 2048.36
     865 2018.86   987.4 1980.07  1008.2 1969.07  1040.4 1969.23  1080.6 1964.16
  1293.8 1959.04  1418.4 1960.21  1535.1 1956.03  1551.2 1962.13  1563.2 1962.38
  1623.6 1954.97  1651.7    1959  1824.6  1957.2  1834.3 1953.97  1856.8 1952.82
  1864.8 1953.81  1876.9 1958.53  2250.9 1957.85  2327.3 1971.84  2514.7 1975.94
#Mann= 10 ,-1,0
       0      .1       0     960     .06       0 1072.66     .05       0
 1372.66      .1       0 1672.66     .05       0 1762.66      .1       0
  1834.3    .045       0  1864.8      .1       0 1962.66     .05       0
 2462.66     .06       0
#XS Ineff= 2 , 0
         1675.77    1980
Permanent Ineff=
       F       F
Bank Sta=1834.3,1864.8
XS Rating Curve= 0 ,0
Exp/Cntr(USF)=0,0
Exp/Cntr=0.3,0.1

Type RM Length L Ch R = 1 ,39019   ,260.5,260.5,260.5
XS GIS Cut Line= 2
2305935.13340681744818.9129073052304463.07964597744719.408222095
#Sta/Elev= 30
       0 1989.85    31.4 1985.91    55.1 1978.64    91.2 1977.27   119.2 1971.16
   175.4 1964.15   259.5 1959.48   399.9 1960.51   407.9  1958.5   421.2  1962.9
   431.9 1963.93     460 1962.62   503.9 1954.16   640.4 1956.17   661.6 1954.14
   688.5 1955.48     917 1953.84   969.2 1957.15  1001.2 1956.63  1008.4 1953.91
  1013.3 1952.93  1035.81954.013  1041.3  1957.6  1049.3 1958.75  1221.7  1957.2
  1322.5 1961.59  1374.1 1969.77  1435.2 1970.23  1446.3  1973.1  1475.4 1973.97
#Mann= 9 ,-1,0
       0     .05       0      80     .07       0     180     .05       0
     380      .1       0  1008.4    .045       0  1035.8      .1       0
    1270     .05       0    1370     .06       0    1470     .05       0
#XS Ineff= 2 , 0
          637.69 1962.62
Permanent Ineff=
       F       F
Bank Sta=1008.4,1035.8
XS Rating Curve= 0 ,0
Exp/Cntr(USF)=0,0
Exp/Cntr=0.3,0.1

Type RM Length L Ch R = 1 ,38759   ,523.5,523.5,523.5
XS GIS Cut Line= 2
2306010.76534709744494.6428009642304434.66515733744489.815757827
#Sta/Elev= 30
       0 2069.43    30.6 2071.69    58.6 2067.43   138.6    2034   197.7 2005.11
   258.6 1984.73   278.6 1972.18   314.6 1973.69   334.6 1966.01   350.6 1963.24
   394.6 1959.38   402.8 1962.19   430.6 1962.56   442.6 1958.13   478.6 1953.97
   578.9 1956.03   602.6 1954.32   662.6 1958.34   990.6 1953.79  1022.6  1953.8
  1046.6 1957.78  1067.9 1953.53  1094.6 1952.26  1102.6 1953.35  1122.6 1957.81
  1190.6 1956.12  1386.6 1959.51  1491.5 1971.21  1542.6 1973.48  1576.1 1972.08
#Mann= 10 ,-1,0
       0      .1       0     260     .08       0     360      .1       0
     460    .025       0     550      .1       0    1050     .05       0
  1067.9    .045       0  1102.6     .05       0    1440     .06       0
    1540     .05       0
#XS Ineff= 2 , 0
          423.97 1975.48
Permanent Ineff=
       F       F
Bank Sta=1067.9,1102.6
XS Rating Curve= 0 ,0
Exp/Cntr(USF)=0,0
Exp/Cntr=0.3,0.1

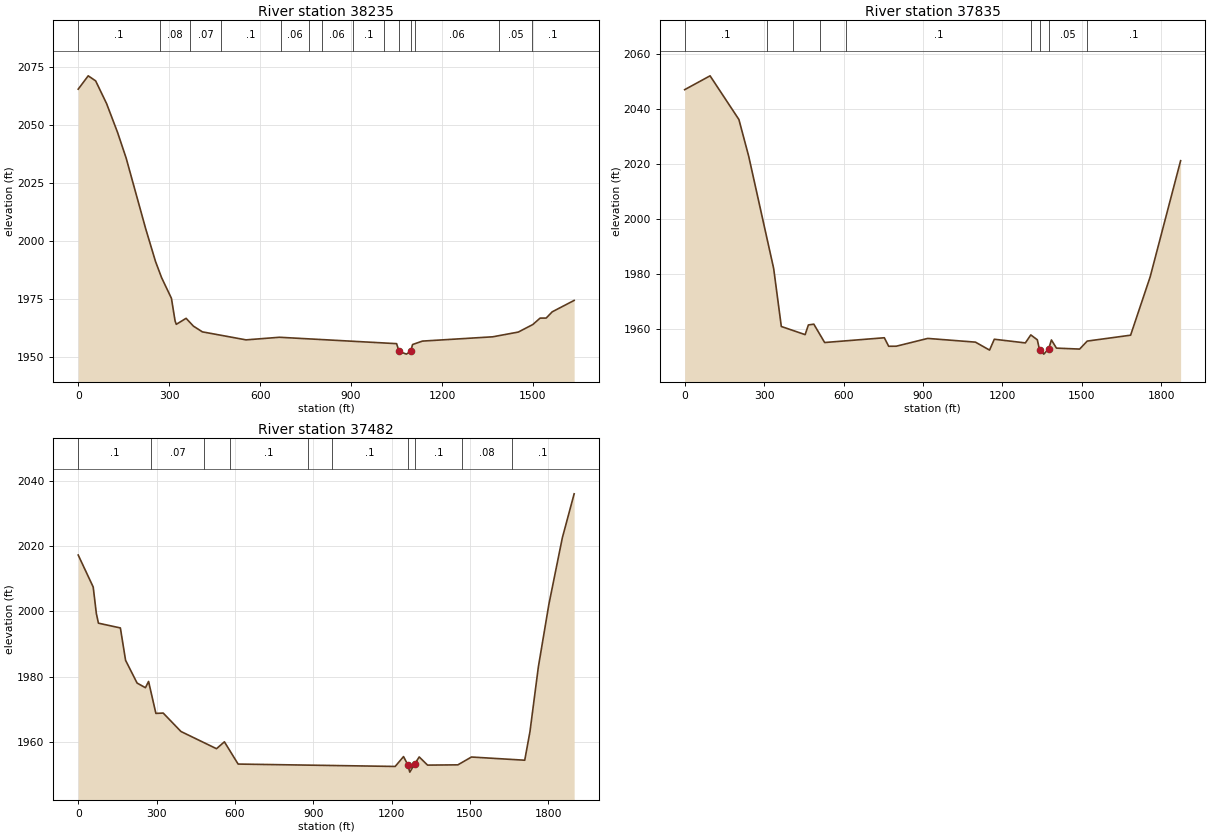
Type RM Length L Ch R = 1 ,38235   ,399.9,399.9,399.9
BEGIN DESCRIPTION:
Structure
END DESCRIPTION:
XS GIS Cut Line= 6
2306020.89138474744365.0750137492305387.19759614744279.662073162
2305258.77853071  744175.53850662305080.03307478744128.682901648
2304948.14322381744107.8581883352304435.80665293744106.628043541
#Sta/Elev= 30
       0 2065.36      33  2071.1    57.5 2068.93    93.6 2059.15   129.9  2046.7
   158.1  2035.7   222.7 2005.21     255 1991.17   275.2 1984.16   307.5 1975.31
   319.6 1965.54   323.6  1964.1   355.9 1966.69   380.1 1963.32   409.6 1960.86
   553.7 1957.41   663.9 1958.53  1050.3 1955.781058.3651952.489  1082.7 1951.27
1096.9651952.523  1102.9  1955.4  1135.5 1956.88  1367.6 1958.73  1451.7 1960.77
  1499.7 1964.02  1523.7 1966.78  1543.7  1966.8  1563.7 1969.49    1636  1974.4
#Mann= 14 ,-1,0
       0      .1       0     270     .08       0     370     .07       0
     470      .1       0  669.42     .06       0  762.66      .1       0
  802.66     .06       0   904.9      .1       0 1009.68     .08       0
1058.365    .045       01096.965     .08       0 1109.68     .06       0
 1387.45     .05       0 1497.89      .1       0
Bank Sta=1058.365,1096.965
XS Rating Curve= 0 ,0
Exp/Cntr(USF)=0,0
Exp/Cntr=0.3,0.1

Type RM Length L Ch R = 1 ,37835   ,353.5,353.5,353.5
XS GIS Cut Line= 4
2306079.41966775744297.5443122072305797.18607355744074.542265148
2304428.51003313743770.0614240242304317.37054944743762.332698458
#Sta/Elev= 30
       0 2046.93    95.9 2051.95   204.8 2036.11   241.8 2022.78   336.1 1982.08
     365 1961.02     455 1958.06   467.3 1961.58   487.8 1961.86   528.7  1955.2
   754.1 1956.93   770.5 1953.84   799.2 1953.86     918 1956.69  1098.3 1955.34
  1151.6 1952.45  1169.5 1956.39  1286.8 1955.06  1307.3 1957.96  1331.9  1956.2
1340.7241952.392  1356.5 1950.991375.1241952.969  1385.2 1956.13  1404.2 1953.17
  1491.7 1952.82  1520.4 1955.72  1684.3 1957.86  1758.1    1979  1873.2 2021.16
#Mann= 9 ,-1,0
       0      .1       0     310     .07       0   409.7      .1       0
   509.7    .025       0   609.7      .1       0  1309.7     .05       0
1340.724    .045       01375.124     .05       0  1519.7      .1       0
Bank Sta=1340.724,1375.124
XS Rating Curve= 0 ,0
Exp/Cntr(USF)=0,0
Exp/Cntr=0.3,0.1

Type RM Length L Ch R = 1 ,37482   ,458.7,458.7,458.7
XS GIS Cut Line= 2
2306233.59571586743543.5104054462304334.93582377743527.825920139
#Sta/Elev= 30
       0 2017.26    57.4 2007.46    69.4 1999.37    77.4 1996.38   161.4 1994.92
   181.4 1984.99   225.4 1978.03   257.4  1976.6   269.4 1978.52   297.4 1968.73
   325.4 1968.83   393.4 1963.18   529.4 1957.91   559.7 1960.02   612.2  1953.2
  1213.5 1952.47  1245.5  1955.51261.4611953.034  1269.5 1950.731287.6611953.139
  1305.5 1955.38  1337.5 1952.88  1453.5 1952.96  1505.5 1955.36  1709.5 1954.38
  1729.5 1963.12  1761.7 1982.99    1802 2002.18  1853.5 2022.55  1898.7 2036.02
#Mann= 10 ,-1,0
       0      .1       0     280     .07       0     480     .05       0
     580      .1       0     880     .05       0     970      .1       0
1261.461    .045       01287.661      .1       0    1470     .08       0
    1660      .1       0
Bank Sta=1261.461,1287.661
XS Rating Curve= 0 ,0
Exp/Cntr(USF)=0,0
Exp/Cntr=0.3,0.1