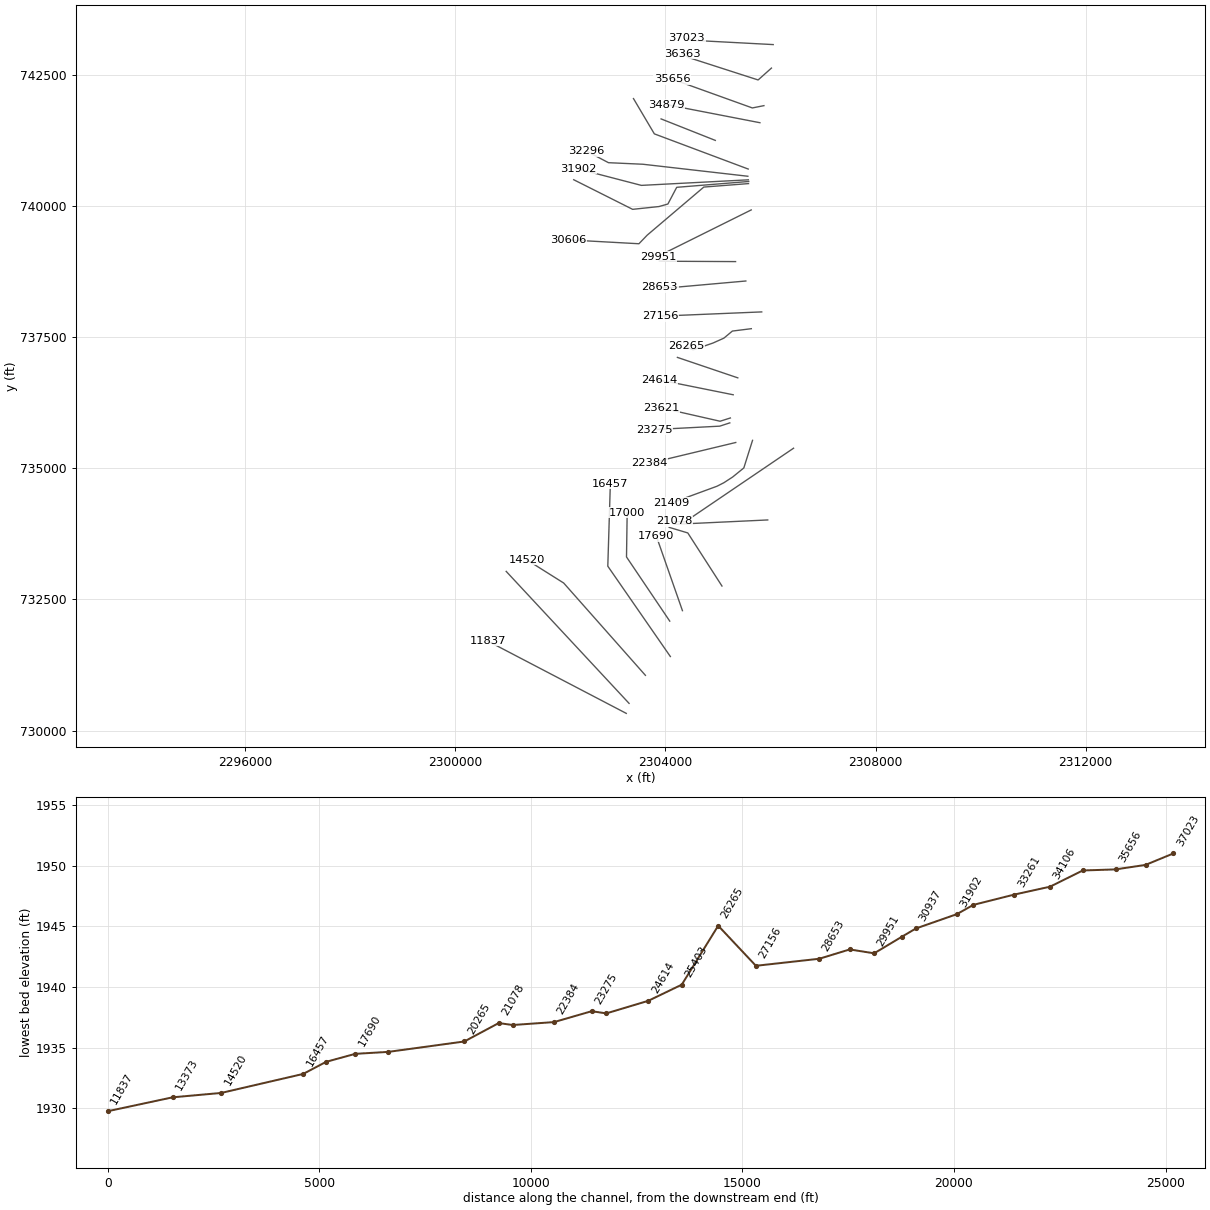
HEC-RAS study LEADNGCK.prj: LEADNGCK

--- LEADNGCK.g01 (geometry) --- (continued)

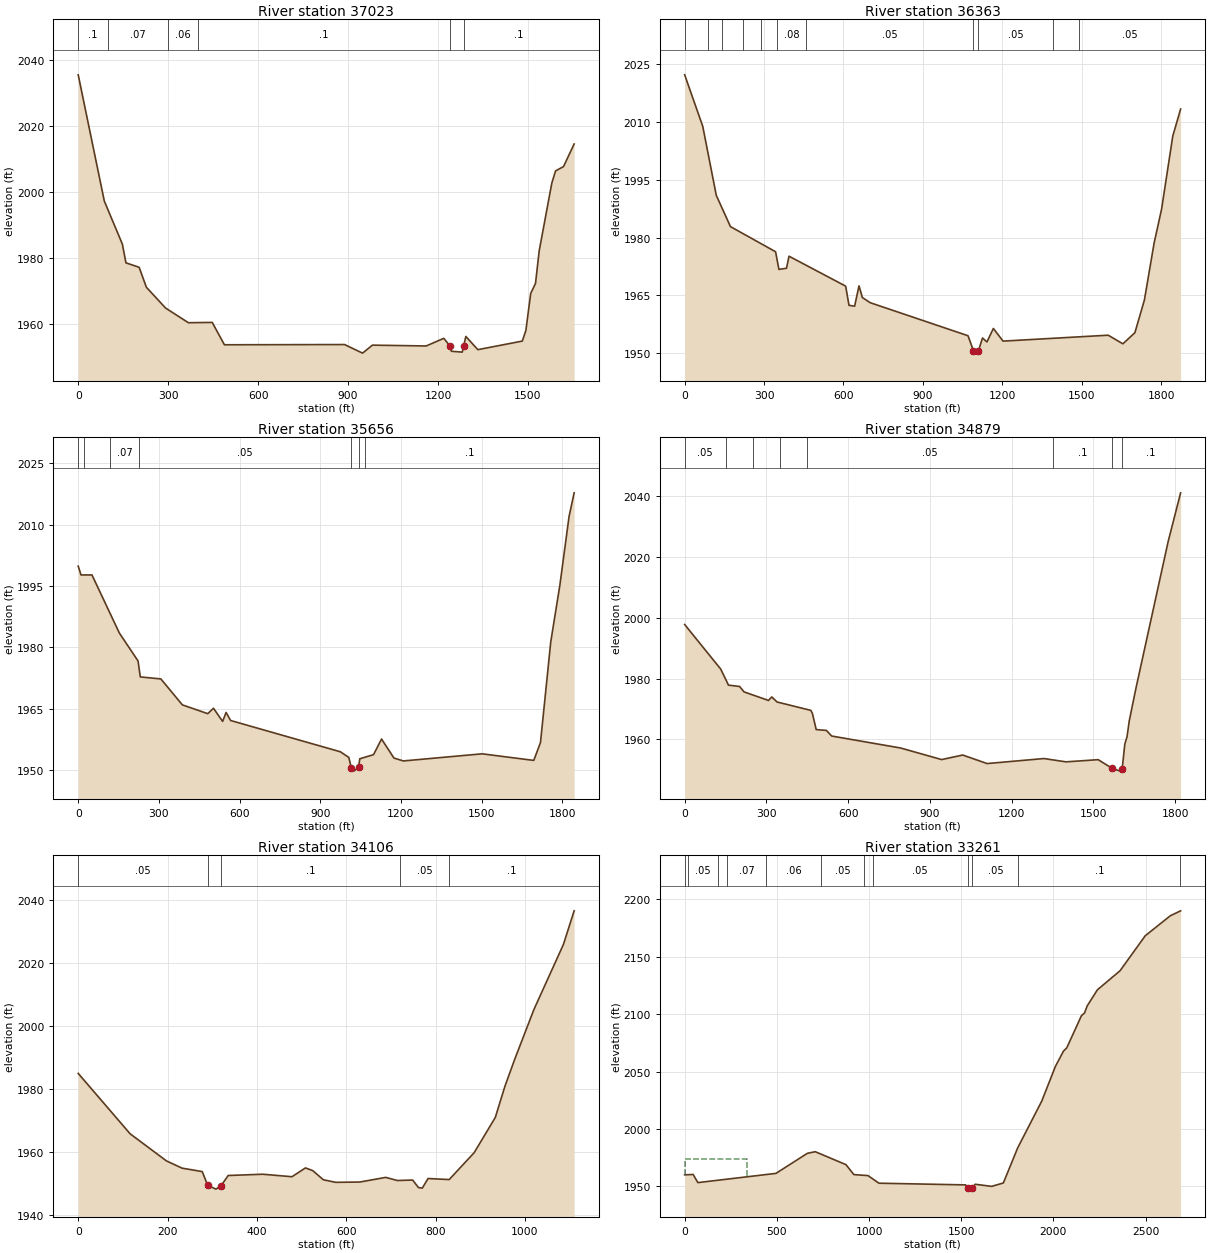
Type RM Length L Ch R = 1 ,37023   ,659.5,659.5,659.5
XS GIS Cut Line= 3
2306051.13590162743070.1810442062304521.92271717743151.133770401
2304405.40296974743189.347622096
#Sta/Elev= 30
       0 2035.39    87.1 1997.11   147.2 1984.09   159.2  1978.4   203.2 1977.05
   227.3 1971.01   291.4 1964.69   367.5 1960.25     447 1960.34   487.6 1953.56
   888.2 1953.63   948.3 1951.03   981.2 1953.45  1160.6  1953.2  1219.2 1955.52
  1239.2 1953.28  1244.7 1951.59  1280.8 1951.33  1285.7 1953.33  1292.8 1956.09
  1332.8 1952.08    1481 1954.68    1493 1957.88  1509.1 1969.13  1525.1 1972.16
  1537.5 1982.07  1579.5 2002.57  1592.1 2006.27  1618.6 2007.58    1654 2014.43
#Mann= 6 ,-1,0
       0      .1       0     100     .07       0     300     .06       0
     400      .1       0  1239.2    .045       0  1285.7      .1       0
Bank Sta=1239.2,1285.7
XS Rating Curve= 0 ,0
Exp/Cntr(USF)=0,0
Exp/Cntr=0.3,0.1

Type RM Length L Ch R = 1 ,36363   ,707.9,707.9,707.9
XS GIS Cut Line= 4
2306017.24319383742622.6230293882305763.57646218 742396.30233723
2304448.29227257742820.5139310642304319.03728234742900.308813184
#Sta/Elev= 30
       0 2022.12    68.3 2008.79   119.4 1990.93     173 1982.83   343.5 1976.32
   356.1 1971.76   384.7 1972.05   394.2 1975.17   608.3 1967.42   620.9 1962.46
   642.1 1962.23   658.7 1967.49   671.4 1964.47   700.8 1963.14  1070.6 1954.58
  1090.9 1950.76  1104.3 1950.08    11101950.688  1125.3    1954  1142.1 1952.97
  1166.4 1956.47  1202.9 1953.19  1600.2 1954.72  1655.8 1952.49  1701.1 1955.36
  1737.1 1963.83  1773.8 1978.59    1802 1987.36  1844.3 2006.27  1873.9 2013.26
#Mann= 11 ,-1,0
       0      .1       0      90     .08       0     140     .07       0
     220     .08       0     290     .05       0  349.95     .08       0
  459.95     .05       0  1090.9    .045       0    1110     .05       0
 1389.95      .1       0 1489.95     .05       0
Bank Sta=1090.9,1110
XS Rating Curve= 0 ,0
Exp/Cntr(USF)=0,0
Exp/Cntr=0.3,0.1

Type RM Length L Ch R = 1 ,35656   ,776.4,776.4,776.4
XS GIS Cut Line= 3
2305874.37614876741906.8965185852305653.78506503 741863.02983677
2304130.31789749742411.572559462
#Sta/Elev= 30
       0 1999.84    10.4 1997.68    51.2 1997.68     153 1983.48   222.5 1976.65
   230.9 1972.75   307.4 1972.25   387.3 1965.91   481.7 1963.76     503 1965.09
     537 1961.86   549.8 1964.06   566.7 1962.09   974.9 1954.44  1006.2 1953.06
  1015.6 1950.45  1024.9 1949.71  1042.31950.651  1047.1 1952.73  1098.2 1953.74
  1127.9 1957.56    1174 1952.91  1208.7  1952.2    1502 1953.94  1693.9 1952.33
  1718.9 1956.69  1757.1 1981.31  1791.1 1995.21  1825.1 2011.94  1844.1 2017.76
#Mann= 7 ,-1,0
       0     .06       0      20     .05       0     120     .07       0
  224.91     .05       0  1015.6    .045       0  1042.3     .05       0
 1064.91      .1       0
Bank Sta=1015.6,1042.3
XS Rating Curve= 0 ,0
Exp/Cntr(USF)=0,0
Exp/Cntr=0.3,0.1

Type RM Length L Ch R = 1 ,34879   ,773.5,773.5,773.5
XS GIS Cut Line= 2
2305798.05389923741581.6125898532304011.10459733741928.100942041
#Sta/Elev= 30
       0 1997.71   132.3  1983.1   160.8 1977.83   201.6 1977.39   217.9 1975.61
   307.5 1972.81   319.7 1973.95   339.1  1972.3   462.9 1969.56   468.8 1968.57
   482.7 1963.25     520 1962.98   539.7 1961.13   792.4 1957.21   943.1 1953.41
  1020.5  1954.9  1109.9  1952.1  1318.6 1953.75  1399.5 1952.66  1517.6 1953.38
  1569.41950.509  1598.4 1949.62  1604.31950.304  1607.3 1951.64  1615.4 1958.49
  1623.6 1960.93  1631.7 1966.12  1656.4 1976.87  1774.3 2024.88  1820.2 2040.92
#Mann= 8 ,-1,0
       0     .05       0     150     .07       0     250     .05       0
     350      .1       0     450     .05       0    1350      .1       0
  1569.4    .045       0  1604.3      .1       0
Bank Sta=1569.4,1604.3
XS Rating Curve= 0 ,0
Exp/Cntr(USF)=0,0
Exp/Cntr=0.3,0.1

Type RM Length L Ch R = 1 ,34106   ,844.6,844.6,844.6
XS GIS Cut Line= 2
2304948.32965615741244.7639246232303916.13329974741654.066114451
#Sta/Elev= 30
       0 1984.96   116.3 1965.81   197.6 1957.22   232.5 1954.93   277.7 1953.84
     2901949.455   308.6 1948.28   320.11949.393   335.8  1952.6   413.5    1953
   478.6 1952.21   508.8    1955   525.1 1954.15   548.9 1951.24   576.8 1950.43
   630.5 1950.53   688.6    1952   714.5 1951.01   748.9 1951.16   761.8 1948.77
   770.4 1948.61   783.3 1951.64   830.6 1951.31   886.6 1959.84   933.9 1971.01
   955.4 1980.87   976.9 1989.27  1020.3  2005.2  1086.3  2025.8  1110.4 2036.48
#Mann= 5 ,-1,0
       0     .05       0     290    .045       0   320.1      .1       0
     720     .05       0     830      .1       0
Bank Sta=290,320.1
XS Rating Curve= 0 ,0
Exp/Cntr(USF)=0,0
Exp/Cntr=0.3,0.1

Type RM Length L Ch R = 1 ,33261   ,965.3,965.3,965.3
XS GIS Cut Line= 3
2305575.23611986740698.7999440172303787.85888372741369.119887956
2303390.49123254742041.372122542
#Sta/Elev= 30
       0 1960.07      46 1960.38    71.6 1953.31   495.1 1961.34   665.4 1978.81
   708.2 1980.23   874.8 1968.96   917.5  1960.3   994.4  1959.4  1053.8 1952.79
  1524.1 1951.31 1534.791948.836  1545.2 1947.631559.8991948.872  1575.4 1951.88
  1665.1 1950.03  1728.5    1953  1806.2 1983.56  1936.9 2024.35  2011.2 2054.66
  2054.8 2067.87  2072.3 2070.62    2152 2098.69  2168.7 2101.06  2183.4 2107.25
  2238.7 2121.24  2361.4 2137.82  2497.9 2168.27  2633.9  2185.7  2689.9 2190.01
#Mann= 12 ,-1,0
       0     .07       0      20     .05       0     180     .06       0
     230     .07       0     440     .06       0     740     .05       0
     970     .06       0    1020     .05       0 1534.79    .045       0
1559.899     .05       0    1810      .1       0 2688.94     .06       0
#XS Ineff= 2 , 0
          336.46 1973.79
Permanent Ineff=
       F       F
Bank Sta=1534.79,1559.899
XS Rating Curve= 0 ,0
Exp/Cntr(USF)=0,0
Exp/Cntr=0.3,0.1

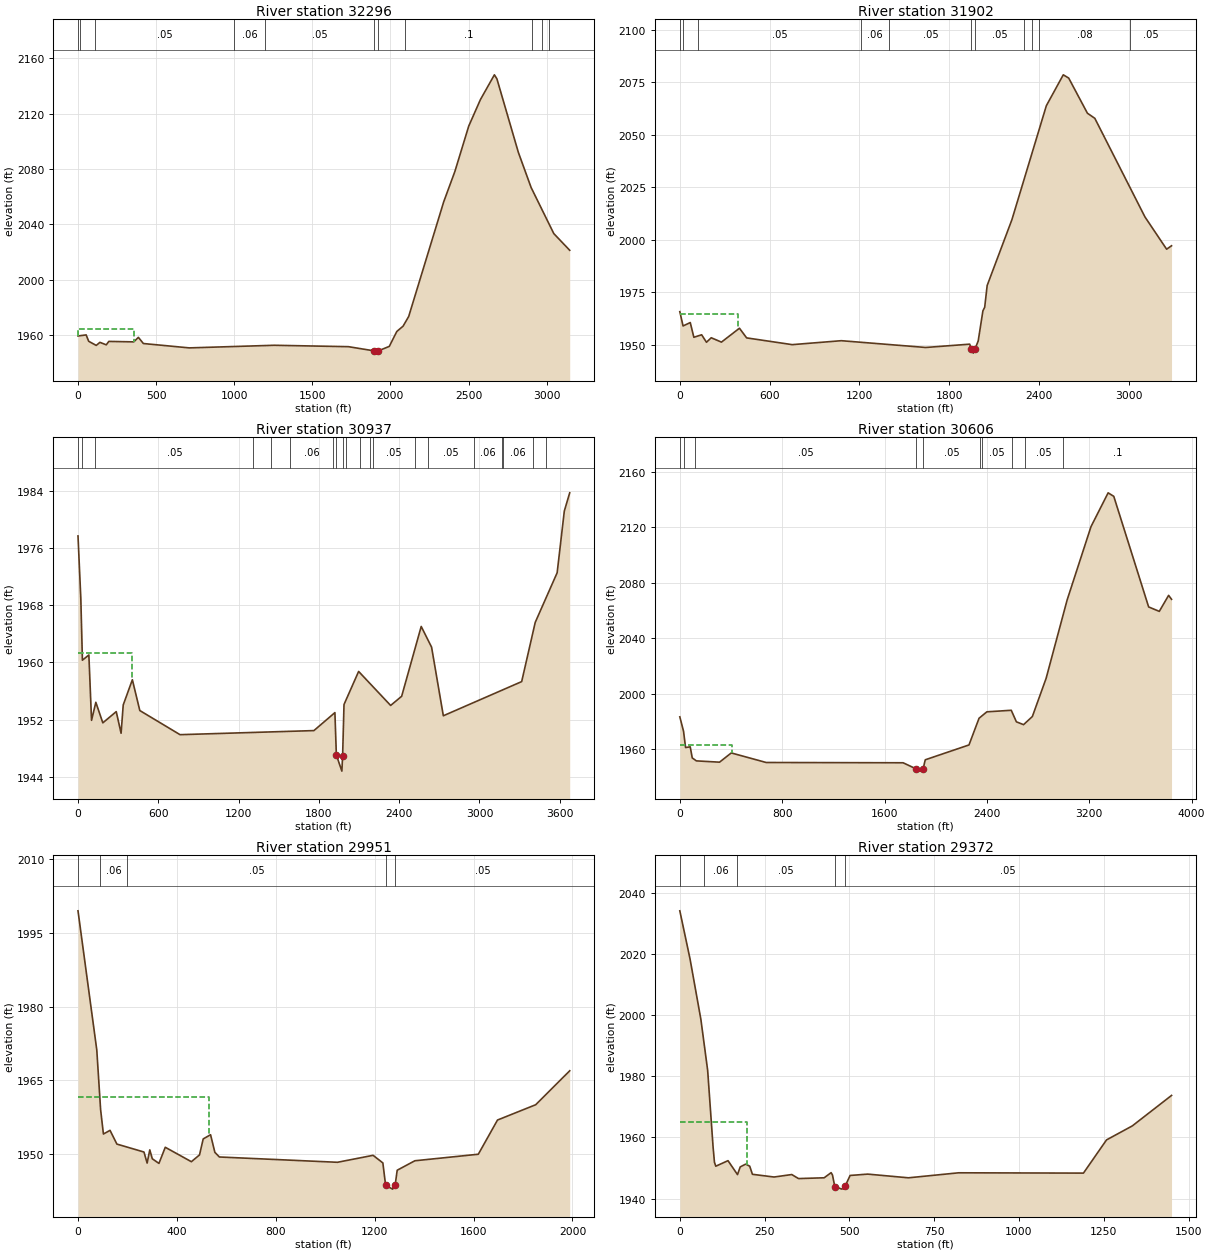
Type RM Length L Ch R = 1 ,32296   ,394.2,394.2,394.2
XS GIS Cut Line= 4
2305568.13498835740561.6492687912303569.42948552    740790.42382
2302914.32895123740820.0587337112302489.30479396741043.854157407
#Sta/Elev= 30
       0 1959.19    52.3 1959.97    68.4 1955.35   116.7 1952.37   140.4 1954.58
   181.1 1952.78   197.2 1955.26   357.2 1954.92   386.5 1958.19   418.6 1953.72
   712.6 1950.57  1256.7 1952.46  1731.2 1951.45 1895.221948.425    1907 1946.78
1922.5991948.413  1992.9 1951.66    2041 1962.46  2081.1 1966.29  2117.1 1973.31
  2341.2 2056.27  2412.8 2078.25  2501.5 2111.09  2576.3 2130.25  2665.7 2148.17
  2681.8 2145.28  2819.1 2092.05  2900.9 2066.61    3046 2033.29  3147.9  2021.2
#Mann= 11 ,-1,0
       0      .1       0      10     .07       0     110     .05       0
    1000     .06       0    1200     .05       0 1895.22    .045       0
1922.599     .05       0 2091.76      .1       0 2907.53     .05       0
 2967.53      .1       0 3017.53     .05       0
#XS Ineff= 2 , 0
           355.6  1963.9
Permanent Ineff=
       F       F
Bank Sta=1895.22,1922.599
XS Rating Curve= 0 ,0
Exp/Cntr(USF)=0,0
Exp/Cntr=0.3,0.1

Type RM Length L Ch R = 1 ,31902   ,965.1,965.1,965.1
XS GIS Cut Line= 3
2305577.80696046740493.6130289752303541.06203121740387.605968776
2302336.41337969740701.253675269
#Sta/Elev= 30
       0 1965.76    21.7 1958.95    69.7 1960.57    93.8 1953.56   145.8 1954.75
   177.9 1951.19   209.9 1953.33     278 1951.25   398.4 1957.87   446.2 1953.27
   750.6 1950.05  1078.7 1951.93  1642.9  1948.7  1936.1 1950.281948.1991947.789
  1960.3 1946.011971.499  1947.9  1993.2 1951.87  2024.4 1966.15  2036.4 1967.86
  2052.8  1978.2  2218.2 2009.58  2448.2 2063.87  2561.2 2078.57  2597.4 2077.03
  2722.4 2060.29    2772 2057.85  3106.8 2010.88  3251.5 1995.51  3284.3 1997.14
#Mann= 11 ,-1,0
       0      .1       0      20     .07       0     120     .05       0
    1210     .06       0    1400     .05       01948.199    .045       0
1971.499     .05       0  2299.5     .08       0  2349.5      .1       0
  2399.5     .08       0  3009.5     .05       0
#XS Ineff= 2 , 0
          388.09 1964.86
Permanent Ineff=
       F       F
Bank Sta=1948.199,1971.499
XS Rating Curve= 0 ,0
Exp/Cntr(USF)=0,0
Exp/Cntr=0.3,0.1

Type RM Length L Ch R = 1 ,30937   ,330.9,330.9,330.9
XS GIS Cut Line= 6
2305585.07576999740461.9130250432304213.56708786740350.821730054
2304045.81245285740032.6663877832303876.12960364739984.461032893
2303374.51209895739931.2118319492302252.42168396740495.408978812
#Sta/Elev= 30
       0 1977.67      21 1968.97      33 1960.32    81.2 1961.05   101.2 1951.92
   133.3 1954.44   185.5 1951.57   285.8 1953.14     322 1950.12     338 1954.07
   406.3 1957.59   461.9 1953.29   762.6 1949.92  1763.1 1950.49    1920    1953
  1930.81947.083    1972 1944.83  1977.51946.873    1988 1954.13  2097.3 1958.75
  2336.4    1954  2418.8 1955.28    2565 1965.03  2642.5 1962.14  2730.3 1952.56
  3315.8 1957.33  3417.1  1965.6  3580.9 1972.53  3634.5 1981.15  3674.8 1983.69
#Mann= 20 ,-1,0
       0      .1       0      30     .06       0     130     .05       0
    1310     .06       0    1446     .05       0    1586     .06       0
 1905.67     .05       0  1930.8    .045       0  1977.5     .05       0
 2002.07     .08       0 2105.29     .07       0 2185.29     .06       0
 2205.29     .05       0 2518.81     .06       0 2618.81     .05       0
 2958.81     .06       0 3168.81     .05       0 3178.81     .06       0
 3398.81     .07       0 3498.81     .06       0
#XS Ineff= 2 , 0
          406.14 1961.31
Permanent Ineff=
       F       F
Bank Sta=1930.8,1977.5
XS Rating Curve= 0 ,0
Exp/Cntr(USF)=0,0
Exp/Cntr=0.3,0.1

Type RM Length L Ch R = 1 ,30606   ,654.7,654.7,654.7
XS GIS Cut Line= 5
2305581.09052556740421.7426520712304729.48243494740355.579566076
2303651.88276333739439.5092905482303494.28579493739275.608443415
2302149.50091458739349.483640942
#Sta/Elev= 30
       0 1983.33      29 1972.98    45.1 1961.17    81.2  1961.7    97.2 1953.68
   129.3 1951.55   310.4 1950.61   402.1 1957.28   674.9 1950.38    1745 1950.18
  1848.1 1945.73  1869.1 1944.15  1901.1  1945.7  1918.1 1952.33  2259.8 1963.04
  2338.4  1982.3  2399.4 1986.95  2590.2 1988.07  2630.2 1979.75  2686.3 1977.68
  2755.1 1983.57  2862.6 2011.12  3026.8 2067.67  3213.3 2120.61  3347.3 2145.02
  3391.4 2142.48  3663.8 2062.66    3747 2059.46    3820 2071.01  3842.7 2068.18
#Mann= 10 ,-1,0
       0      .1       0      30     .06       0     120     .05       0
  1848.1    .045       0  1901.1     .05       0 2348.53     .06       0
 2358.53     .05       0 2595.91     .06       0 2695.91     .05       0
 2995.91      .1       0
#XS Ineff= 2 , 0
          406.14 1963.19
Permanent Ineff=
       F       F
Bank Sta=1848.1,1901.1
XS Rating Curve= 0 ,0
Exp/Cntr(USF)=0,0
Exp/Cntr=0.3,0.1

Type RM Length L Ch R = 1 ,29951   ,578.8,578.8,578.8
XS GIS Cut Line= 3
2305632.19613721 739920.06520627 2304034.9442243739125.582982545
2303854.28815478739028.672109049
#Sta/Elev= 30
       0  1999.5      76 1971.14    91.4 1959.01   102.8 1954.01   129.6 1954.76
   157.3 1951.96   266.9 1950.34   279.6 1948.09   290.4 1950.78   300.5 1948.97
   327.4 1948.02     353 1951.31   458.6 1948.37   491.5 1949.75   506.4 1953.01
   536.2 1953.87   553.6 1950.28   571.9 1949.33  1049.4 1948.25  1193.6 1949.67
  1233.1 1948.12  1244.3 1943.54  1272.9 1942.78  1282.71943.567  1291.1 1946.63
  1362.5 1948.56  1619.2 1949.89  1696.8 1956.86  1851.3 1959.98  1988.9  1966.9
#Mann= 5 ,-1,0
       0      .1       0      90     .06       0     200     .05       0
  1244.3    .045       0  1282.7     .05       0
#XS Ineff= 2 , 0
          528.52 1961.62
Permanent Ineff=
       F       F
Bank Sta=1244.3,1282.7
XS Rating Curve= 0 ,0
Exp/Cntr(USF)=0,0
Exp/Cntr=0.3,0.1

Type RM Length L Ch R = 1 ,29372   ,719.3,719.3,719.3
XS GIS Cut Line= 3
2305334.27017707738935.5322204252304057.89063845 738941.76637832
2303884.53680501 738945.99246507
#Sta/Elev= 30
       0 2034.14    30.1 2018.42    62.1 1998.63    82.1 1981.94    98.1 1956.86
   102.1 1951.89   106.1  1950.6   142.1 1952.41   170.1 1947.85   178.1 1950.36
   194.1 1951.28   206.1 1950.61   214.1 1947.95   277.8 1947.06   330.1 1947.87
     350 1946.55   425.7 1946.81   446.1 1948.49   450.1 1947.72     457 1943.92
   478.1  1943.1   487.21944.023   502.1 1947.57   554.1 1948.01   674.1  1946.8
   822.1 1948.44  1190.1 1948.34  1258.1  1959.2  1334.1 1963.78  1449.8 1973.75
#Mann= 5 ,-1,0
       0      .1       0      70     .06       0     170     .05       0
     457    .045       0   487.2     .05       0
#XS Ineff= 2 , 0
          198.12    1965
Permanent Ineff=
       F       F
Bank Sta=457,487.2
XS Rating Curve= 0 ,0
Exp/Cntr(USF)=0,0
Exp/Cntr=0.3,0.1

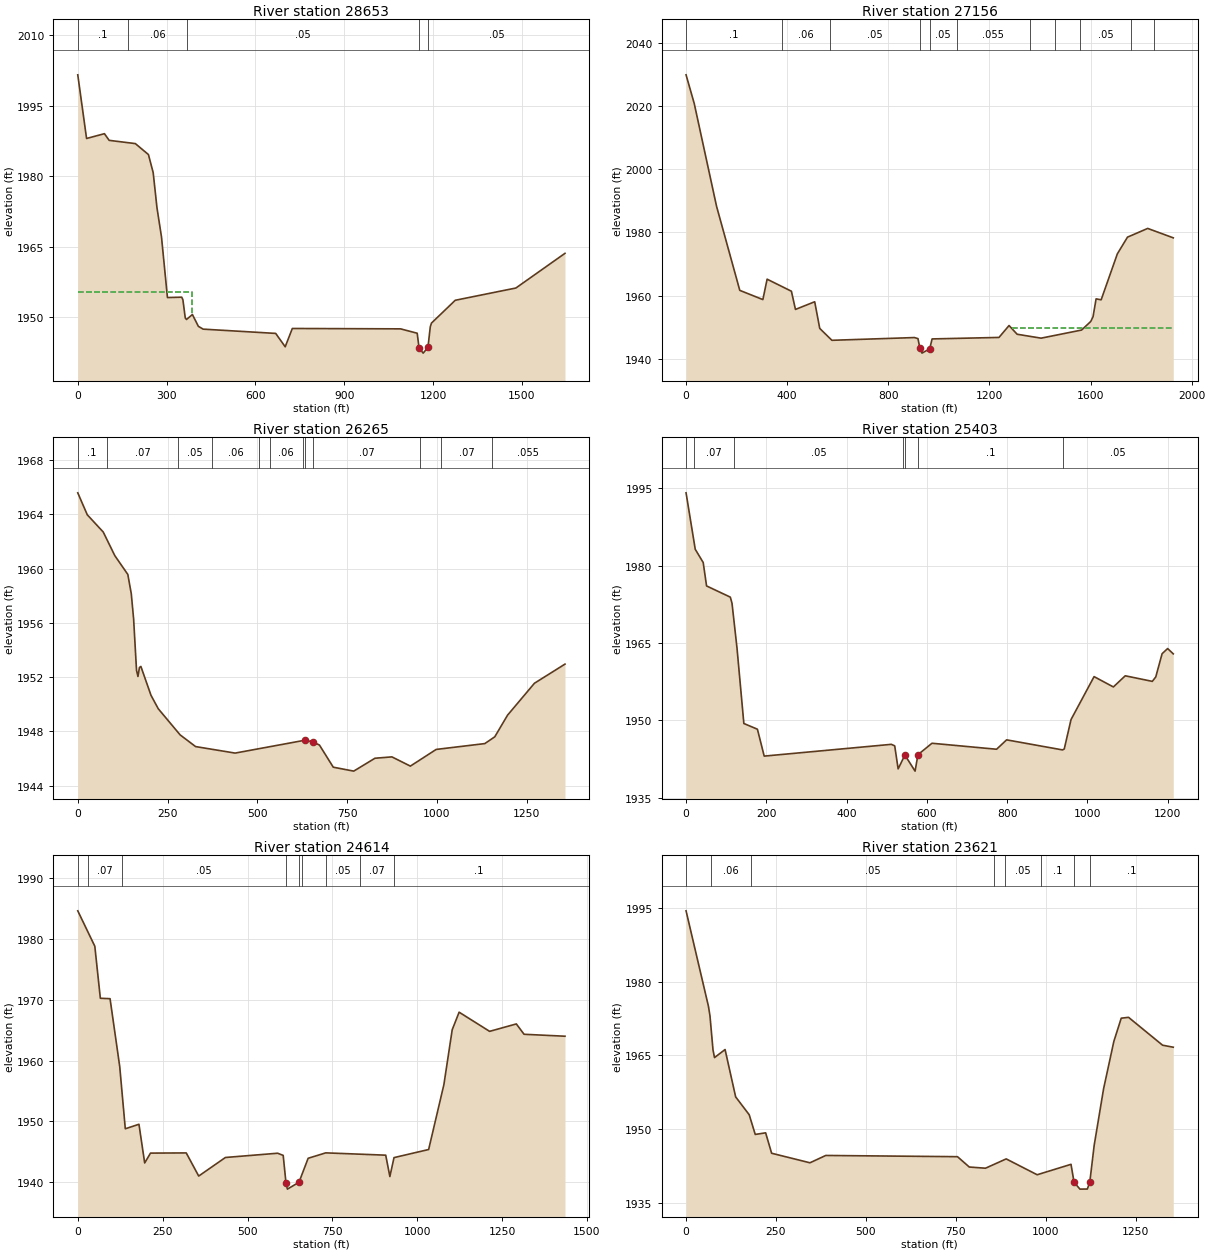
Type RM Length L Ch R = 1 ,28653   ,1497,1497,1497
XS GIS Cut Line= 3
2305529.79307885738565.7866554832304100.53863922738438.502473273
2303890.58653506738447.898024515
#Sta/Elev= 30
       0 2001.62    29.7 1988.06      90 1989.08     106 1987.66   194.4 1986.97
   238.6 1984.63   254.6 1980.79   267.5 1973.27   282.7 1967.08   302.8 1954.17
     351 1954.25     355 1953.69     363 1949.81   367.1  1949.5   387.1 1950.55
   407.2 1948.04   423.3 1947.44   668.3 1946.53   700.4 1943.68   724.5 1947.58
  1089.9  1947.5  1146.1 1946.57  1152.41943.447  1166.2 1942.33  1182.41943.543
  1190.3 1947.94  1194.3 1948.73  1274.6 1953.59  1479.3  1956.2  1645.1 1963.59
#Mann= 5 ,-1,0
       0      .1       0     170     .06       0     370     .05       0
  1152.4    .045       0  1182.4     .05       0
#XS Ineff= 2 , 0
          387.29 1955.33
Permanent Ineff=
       F       F
Bank Sta=1152.4,1182.4
XS Rating Curve= 0 ,0
Exp/Cntr(USF)=0,0
Exp/Cntr=0.3,0.1

Type RM Length L Ch R = 1 ,27156   ,890.6,890.6,890.6
XS GIS Cut Line= 2
2305832.53328288737976.992791382 2303907.2419647737896.772319791
#Sta/Elev= 30
       0  2029.9    32.4  2020.8   120.5  1988.3   212.5 1961.63   303.8 1958.71
   320.6 1965.17   416.7 1961.36   432.7 1955.59   508.8 1958.02   528.8 1949.57
   576.9 1945.81   903.3 1946.68   917.2 1946.35   925.2 1943.22   933.2 1941.75
   963.61943.116   973.2 1946.25  1237.7 1946.72  1277.5 1950.49  1309.5 1947.73
  1404.2 1946.49  1564.4 1949.06  1600.6 1951.77  1609.8 1953.31  1621.8 1958.94
  1641.8 1958.64  1705.8 1973.18  1745.9 1978.48  1825.9 1981.25    1927 1978.27
#Mann= 11 ,-1,0
       0      .1       0     380     .06       0     570     .05       0
   925.2    .045       0   963.6     .05       0    1070    .055       0
    1360     .05       0    1460    .055       0    1560     .05       0
    1760     .06       0    1850     .05       0
#XS Ineff= 2 , 0
                         1288.09         1949.83
Permanent Ineff=
       F       T
Bank Sta=925.2,963.6
XS Rating Curve= 0 ,0
Exp/Cntr(USF)=0,0
Exp/Cntr=0.3,0.1

Type RM Length L Ch R = 1 ,26265   ,861.7,861.7,861.7
BEGIN DESCRIPTION:
Structure
END DESCRIPTION:
XS GIS Cut Line= 6
2305634.49264664737657.2415163762305273.40451087  737611.8890087
2305111.75267378737476.9448664362304905.11945594737384.170768629
2304525.58905583737253.4436308112304387.26849808737318.272440152
#Sta/Elev= 30
       0 1965.58    26.5 1963.96    70.9 1962.69   103.1 1960.95   139.4 1959.56
     149 1958.14   155.5 1956.28   163.6 1952.49   167.6 1952.04   171.7  1952.7
   175.7 1952.78   203.9 1950.65   224.1 1949.66   285.1 1947.73   328.1 1946.87
   438.1 1946.39   632.9 1947.34   655.1 1947.21     673 1946.98   711.4 1945.35
   768.4 1945.06   827.5 1946.01   874.7 1946.11   926.1 1945.43     998 1946.66
  1133.4 1947.09  1161.1 1947.59  1196.8 1949.19  1271.6 1951.54  1356.6 1952.95
#Mann= 12 ,-1,0
       0      .1       0      80     .07       0     280     .05       0
  373.93     .06       0  504.69     .08       0  534.69     .06       0
  625.89     .07       0   632.9    .045       0   655.1     .07       0
  952.39     .08       0 1012.39     .07       0 1152.39    .055       0
Bank Sta=632.9,655.1
XS Rating Curve= 0 ,0
Exp/Cntr(USF)=0,0
Exp/Cntr=0.3,0.1

Type RM Length L Ch R = 1 ,25403   ,789.9,789.9,789.9
XS GIS Cut Line= 2
  2305376.599631736720.5511621142304226.90574904737110.109498686
#Sta/Elev= 30
       0 1994.11    22.9 1983.17    42.7 1980.61    51.1 1976.07   110.3  1973.9
   114.5  1972.7     127 1963.99     144 1949.42   177.8 1948.31   194.7  1943.1
   511.5 1945.38   519.9 1945.09   528.4 1940.63   545.3  1943.3   570.6 1940.19
   577.81943.374   612.7 1945.59   773.7 1944.43   798.7 1946.25     938  1944.3
   942.3 1944.48   959.2 1950.18  1016.6  1958.5  1064.7  1956.5  1094.3 1958.66
  1161.7 1957.58  1170.3 1958.44  1186.1 1962.94  1199.9 1963.94  1213.9 1962.91
#Mann= 7 ,-1,0
       0      .1       0      20     .07       0     120     .05       0
     540      .1       0   545.3    .045       0   577.8      .1       0
     940     .05       0
Bank Sta=545.3,577.8
XS Rating Curve= 0 ,0
Exp/Cntr(USF)=0,0
Exp/Cntr=0.3,0.1

Type RM Length L Ch R = 1 ,24614   ,992.2,992.2,992.2
XS GIS Cut Line= 3
2305289.37085998736398.1165490242304042.78689945 736649.20567539
2303880.61495036736670.209962255
#Sta/Elev= 30
       0  1984.6    50.2 1978.78    66.5 1970.23    95.1 1970.16   123.6 1958.99
     140 1948.78   180.2 1949.52   197.1 1943.16   214.2 1944.78   319.5 1944.81
   356.2 1941.01   434.9 1944.06   588.8 1944.76   605.1  1944.4   613.21939.931
   617.4 1938.86   651.6 1939.99   678.6 1943.93   730.4 1944.82   907.1 1944.44
   919.3 1940.93   931.5 1944.04  1033.5 1945.37  1078.4 1956.03  1102.9 1965.05
  1123.3 1967.94  1213.1 1964.79  1291.8 1966.01  1314.6 1964.31  1435.1 1963.99
#Mann= 9 ,-1,0
       0      .1       0      30     .07       0     130     .05       0
   613.2    .045       0   651.6     .05       0     660     .07       0
     730     .05       0     830     .07       0     930      .1       0
Bank Sta=613.2,651.6
XS Rating Curve= 0 ,0
Exp/Cntr(USF)=0,0
Exp/Cntr=0.3,0.1

Type RM Length L Ch R = 1 ,23621   ,346.3,346.3,346.3
XS GIS Cut Line= 3
2305235.56781842735956.2271736152305039.31706047735893.882571189
2303919.16266659736148.484268823
#Sta/Elev= 30
       0 1994.36    62.3 1974.95    66.5 1973.01    74.9 1966.13    79.1 1964.54
   108.5 1966.18   137.9 1956.56   175.6 1952.93   192.4 1948.93   221.3 1949.26
   237.9 1945.11   344.5 1943.17   388.4 1944.66   754.7 1944.41   787.5 1942.31
   832.6 1942.07   890.1 1943.96   976.2 1940.74  1070.3 1942.86  1078.8 1939.21
  1095.2 1937.82  1115.7 1937.84 1122.481939.205  1134.7 1946.71  1160.8 1958.18
  1189.5 1967.86    1210 1972.55  1230.3 1972.72  1324.9 1967.06  1354.6 1966.65
#Mann= 8 ,-1,0
       0      .1       0      70     .06       0     180     .05       0
  855.92      .1       0  885.92     .05       0  985.92      .1       0
  1078.8    .045       0 1122.48      .1       0
Bank Sta=1078.8,1122.48
XS Rating Curve= 0 ,0
Exp/Cntr(USF)=0,0
Exp/Cntr=0.3,0.1

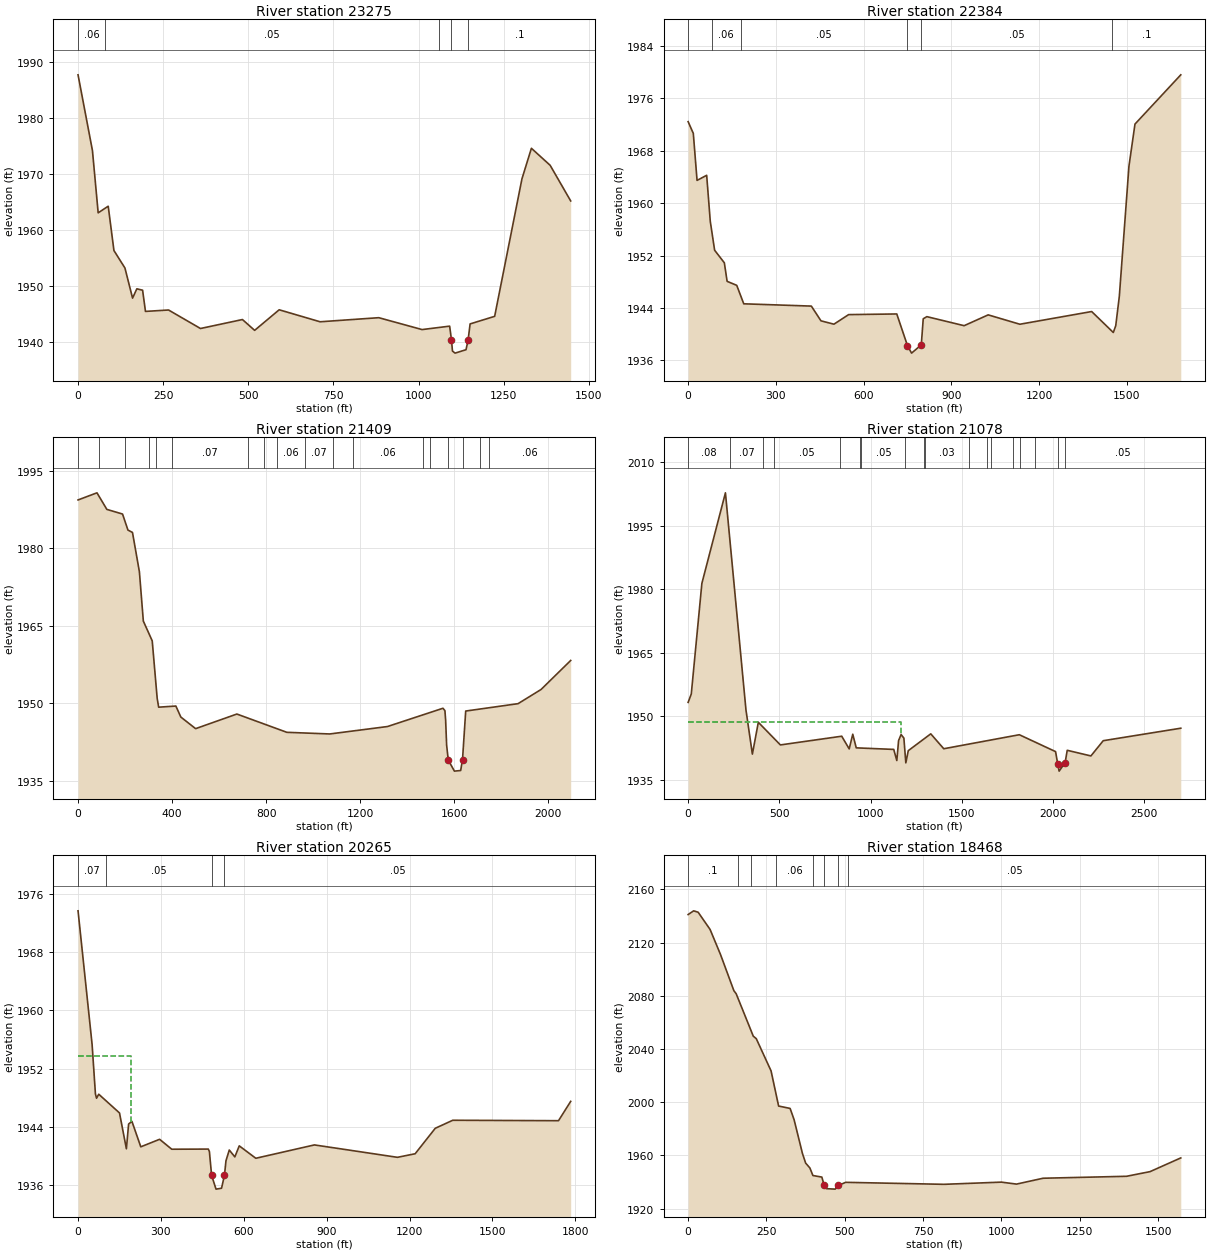
Type RM Length L Ch R = 1 ,23275   ,890.8,890.8,890.8
XS GIS Cut Line= 3
2305224.35182347735862.6363396942305033.30786926735800.154870723
2303789.17604702735735.409747016
#Sta/Elev= 30
       0 1987.63    42.3 1974.12    59.1 1963.02    88.6  1964.2   105.4  1956.3
   137.7 1953.18   160.1 1947.81   172.7 1949.47   189.6 1949.22     198 1945.44
   265.8 1945.69   359.6 1942.39   482.8 1943.99   518.6 1942.06   590.7 1945.73
   710.8 1943.59   883.1 1944.32  1010.3  1942.2  1091.3 1942.81  1096.6  1940.4
  1099.6 1938.37  1107.2    1938  1139.4 1938.61  1145.5 1940.33  1151.4 1943.21
  1223.5 1944.56  1303.6 1969.07  1331.4 1974.53  1386.4  1971.5  1446.8 1965.14
#Mann= 5 ,-1,0
       0     .06       0      80     .05       0    1061      .1       0
  1096.6    .045       0  1145.5      .1       0
Bank Sta=1096.6,1145.5
XS Rating Curve= 0 ,0
Exp/Cntr(USF)=0,0
Exp/Cntr=0.3,0.1

Type RM Length L Ch R = 1 ,22384   ,975.5,975.5,975.5
XS GIS Cut Line= 2
2305337.80197148735488.8632558712303699.93886316735095.403880776
#Sta/Elev= 30
       0 1972.44    17.7 1970.65    30.5 1963.47    63.4 1964.25    75.7 1957.23
    90.6 1952.81   123.8 1950.89   133.3 1948.06   166.2 1947.45   190.2 1944.63
   421.3 1944.28   454.2 1942.03   498.6 1941.52   548.8 1942.98   713.4 1943.08
   749.91938.252     764  1937.1   797.2 1938.36   803.9 1942.34   816.2 1942.67
   943.7 1941.29    1026 1942.94  1134.3 1941.51  1379.8 1943.45  1453.8 1940.25
  1462.1 1941.28  1474.4 1945.78  1507.3 1965.65  1527.9 1972.07  1684.5 1979.59
#Mann= 6 ,-1,0
       0     .07       0      80     .06       0     180     .05       0
   749.9    .045       0   797.2     .05       0    1450      .1       0
Bank Sta=749.9,797.2
XS Rating Curve= 0 ,0
Exp/Cntr(USF)=0,0
Exp/Cntr=0.3,0.1

Type RM Length L Ch R = 1 ,21409   ,330.4,330.4,330.4
XS GIS Cut Line= 6
2305657.41300851735529.9581623052305491.56709652735004.177597556
2305278.27710814734830.7671852452305112.72063731734722.999293854
2304981.52494344734655.8395934212304114.69625182734337.221479743
#Sta/Elev= 30
       0  1989.4    80.5 1990.78   122.5 1987.57   189.2 1986.67   212.1 1983.57
   231.5  1983.1   260.9 1975.47   277.6 1965.93   315.4  1962.1   336.5 1950.96
   342.8 1949.25     416 1949.47     437 1947.34   499.9 1945.09   675.3 1947.92
   887.8 1944.38  1070.1 1944.06  1315.7  1945.5  1551.6 1949.04  1559.9 1948.58
  1562.9 1946.78  1567.2  1941.91574.1411939.007  1600.3 1936.86  1626.9 1936.98
1634.7411939.101  1648.3  1948.5  1870.9 1949.93  1968.8 1952.68  2094.7  1958.3
#Mann= 18 ,-1,0
       0     .05       0      90     .06       0     200     .08       0
     300     .07       0     330     .06       0     400     .07       0
  721.32     .06       0  791.32     .08       0  846.21     .06       0
  966.21     .07       0 1083.75     .05       0 1171.13     .06       0
 1467.12     .05       0 1497.12     .07       01574.141    .045       0
1634.741     .07       0 1707.12     .05       0 1747.12     .06       0
Bank Sta=1574.141,1634.741
XS Rating Curve= 0 ,0
Exp/Cntr(USF)=0,0
Exp/Cntr=0.3,0.1

Type RM Length L Ch R = 1 ,21078   ,813,813,813
XS GIS Cut Line= 3
2306438.49733649735379.9647612752304371.05504556733976.691189765
2304170.03316474733985.332773933
#Sta/Elev= 30
       0 1953.26    17.3 1955.26    75.3 1981.38   204.4 2002.78     317 1951.46
   352.1 1941.04   384.7 1948.56   505.6 1943.21   841.7 1945.27   882.7 1942.27
   902.2 1945.74   921.3 1942.52  1126.8 1942.15  1143.7 1939.52  1153.4 1944.25
  1167.1 1945.67  1182.4 1944.82    1193 1938.97  1206.6 1941.86  1329.7 1945.83
    1401 1942.31    1815 1945.62  2013.7 1941.632025.4021938.743  2033.2 1937.02
2066.1021939.022  2077.6 1941.94  2207.3 1940.61    2275 1944.21  2699.9 1947.16
#Mann= 18 ,-1,0
       0     .08       0     230     .07       0     410     .06       0
     470     .05       0     830     .07       0     940     .06       0
     950     .05       0    1190     .03       0    1290     .05       0
    1300     .03       0    1540      .1       0    1640     .05       0
    1660     .03       0    1780     .05       0    1820     .07       0
    1900     .05       02025.402    .045       02066.102     .05       0
#XS Ineff= 2 , 0
         1166.03 1948.52
Permanent Ineff=
       F       F
Bank Sta=2025.402,2066.102
XS Rating Curve= 0 ,0
Exp/Cntr(USF)=0,0
Exp/Cntr=0.3,0.1

Type RM Length L Ch R = 1 ,20265   ,1797.7,1797.7,1797.7
XS GIS Cut Line= 2
2305947.00975297734013.1339424422304165.82050652733929.410873516
#Sta/Elev= 30
       0 1973.65    50.9 1955.32    62.9 1948.56    66.9 1947.96    74.9 1948.51
   150.1 1945.94     175 1941.03     183 1944.42     195 1944.79   227.1  1941.3
   295.2 1942.33   339.2 1940.97   471.4 1940.99   475.4 1940.67   483.4 1937.39
   499.4  1935.5   519.4 1935.62   529.91937.379   535.4 1939.38   547.4 1940.86
   567.5 1939.92   583.5 1941.43   643.5 1939.73   855.6 1941.56  1156.1 1939.86
  1220.2 1940.35    1293 1943.84  1356.3 1944.94  1739.1 1944.88  1783.2 1947.53
#Mann= 4 ,-1,0
       0     .07       0     100     .05       0   483.4    .045       0
   529.9     .05       0
#XS Ineff= 2 , 0
          192.92 1953.79
Permanent Ineff=
       F       F
Bank Sta=483.4,529.9
XS Rating Curve= 0 ,0
Exp/Cntr(USF)=0,0
Exp/Cntr=0.3,0.1

Type RM Length L Ch R = 1 ,18468   ,777.9,777.9,777.9
XS GIS Cut Line= 3
2305075.10580149732754.2826489842304424.66349991733765.610550868
2304070.27838327733871.893535798
#Sta/Elev= 30
       0 2141.11    17.7  2143.9      32 2142.83      70 2129.93   103.3 2111.08
     146 2083.86   153.3 2081.57   207.9 2049.67   217.5 2047.77   264.7 2023.55
   288.8 1997.11   325.5 1995.32   338.2 1986.86   364.9 1961.41   375.1  1954.2
   388.7 1950.53   398.2 1944.87   426.7  1943.7   434.3 1937.57   441.7 1934.98
   469.5 1934.64     479 1937.37   502.8 1939.75   816.7 1938.25   999.9  1939.9
  1048.1 1938.42    1133 1942.83  1399.2 1944.29  1474.4  1947.8  1572.4 1958.11
#Mann= 8 ,-1,0
       0      .1       0     160     .06       0     200      .1       0
     280     .06       0     400      .1       0   434.3    .045       0
     479      .1       0     510     .05       0
Bank Sta=434.3,479
XS Rating Curve= 0 ,0
Exp/Cntr(USF)=0,0
Exp/Cntr=0.3,0.1

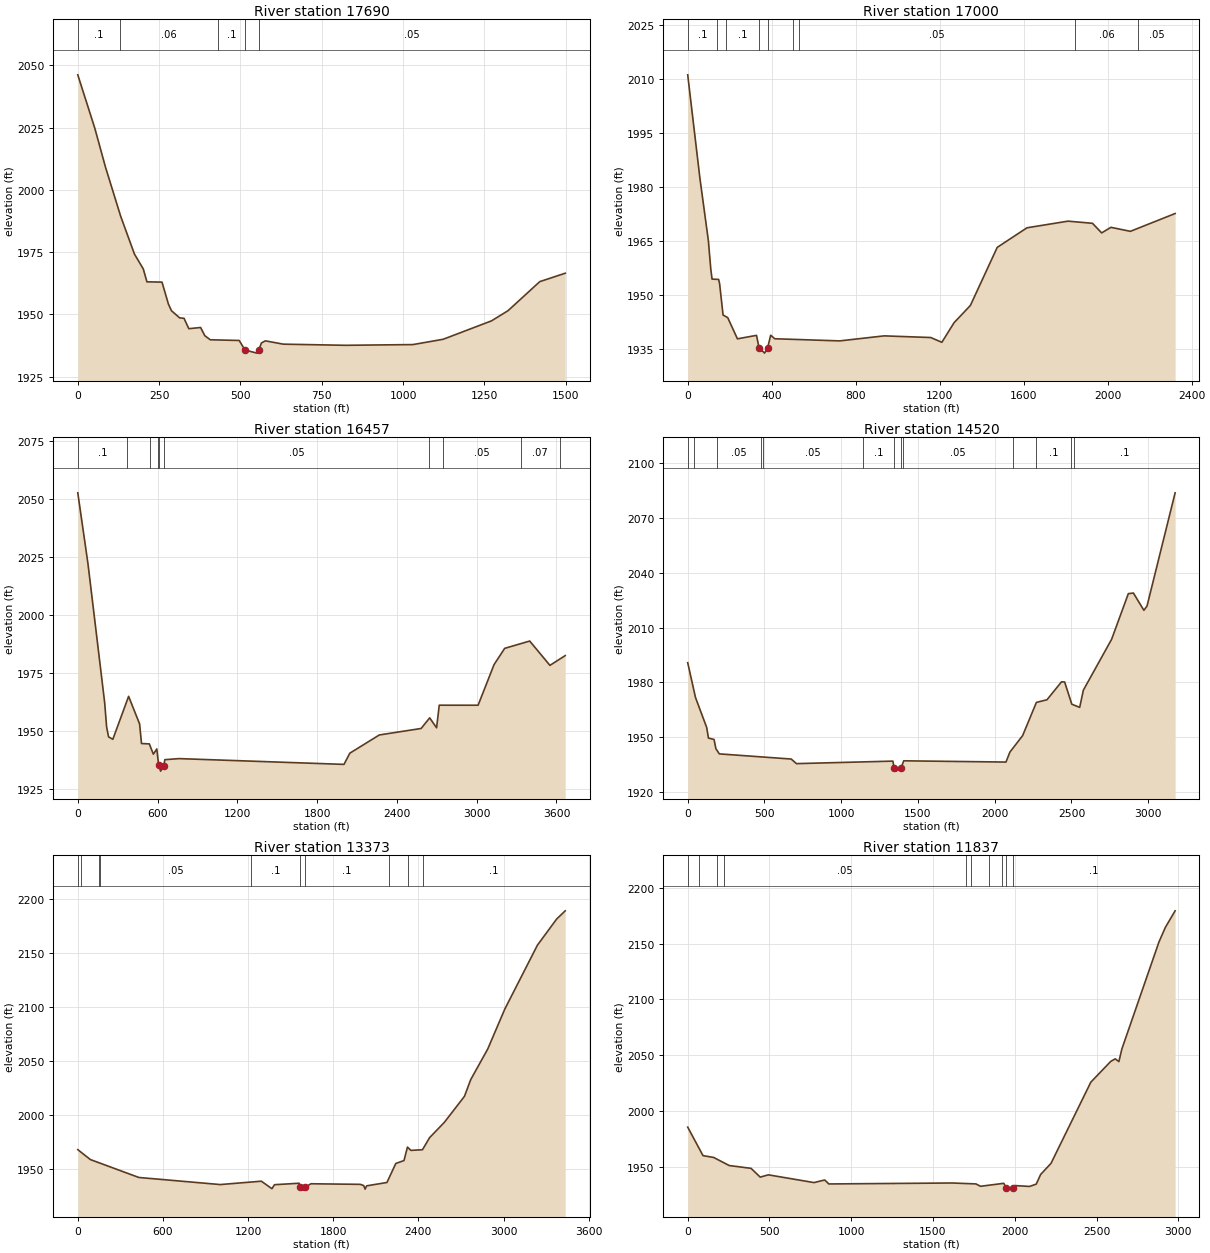
Type RM Length L Ch R = 1 ,17690   ,689.5,689.5,689.5
XS GIS Cut Line= 2
2304322.67744992732284.8114470392303827.75481629733699.025356477
#Sta/Elev= 30
       0 2046.21    52.5 2024.71    85.1 2009.17   131.8 1989.45   174.1 1974.28
   201.3 1968.29   212.6  1963.1   258.9 1962.99   278.5 1954.21   287.9 1951.52
     313 1948.65   326.7 1948.44   341.3 1944.29   377.6 1944.77   390.3 1941.51
   407.2 1939.84   496.2 1939.56     514 1935.73   550.7 1934.48   556.61935.834
   564.6 1938.56   576.7 1939.41   631.8 1938.08   822.5 1937.62  1030.2 1937.91
  1123.4 1940.05  1271.8 1947.44  1322.6 1951.52  1420.1 1963.18  1498.3 1966.56
#Mann= 5 ,-1,0
       0      .1       0     130     .06       0     430      .1       0
     514    .045       0   556.6     .05       0
Bank Sta=514,556.6
XS Rating Curve= 0 ,0
Exp/Cntr(USF)=0,0
Exp/Cntr=0.3,0.1

Type RM Length L Ch R = 1 ,17000   ,543.4,543.4,543.4
XS GIS Cut Line= 3
2304081.00147294 732085.483851572303257.64826625733307.834803526
2303270.45477604734154.921312727
#Sta/Elev= 30
       0 2011.23      58 1982.51    98.4  1965.1   109.9 1957.19     116 1954.41
   147.3 1954.32   151.8 1953.17   168.4 1944.42   190.6 1943.69   236.7  1937.8
   327.6 1938.76   339.71935.325   366.2 1933.82   380.61935.302   395.1 1938.81
   414.4 1937.82   723.7 1937.22   935.3 1938.62  1157.1 1938.16  1210.2 1936.83
  1268.3 1942.28  1346.1 1947.08  1473.8 1963.23  1615.5 1968.68  1811.2 1970.53
  1927.5 1969.93  1971.2 1967.26  2015.2 1968.81  2108.1  1967.7    2321 1972.65
#Mann= 9 ,-1,0
       0      .1       0     140     .06       0     180      .1       0
   339.7    .045       0   380.6     .05       0     500      .1       0
     530     .05       0 1843.79     .06       0 2143.79     .05       0
Bank Sta=339.7,380.6
XS Rating Curve= 0 ,0
Exp/Cntr(USF)=0,0
Exp/Cntr=0.3,0.1

Type RM Length L Ch R = 1 ,16457   ,1937.4,1937.4,1937.4
XS GIS Cut Line= 3
2304092.58160156731410.7965988462302901.56795639  733131.9926752
2302950.18282375734703.939066187
#Sta/Elev= 30
       0 2052.65    76.8 2022.04   202.3 1962.26   216.9 1951.81   231.5 1947.58
   263.6 1946.53   382.3 1965.02   464.9 1953.15   479.2 1944.71     538 1944.54
   568.4 1940.13   594.2 1942.37   608.6 1935.29     623 1932.82  647.021935.062
   654.7 1937.75     761 1938.21  2002.1 1935.72  2045.9 1940.54  2267.6 1948.39
  2582.5 1951.19  2646.5 1955.76  2698.5 1951.48  2718.6 1961.21  3010.7 1961.19
  3130.8 1978.69  3210.8 1985.69  3398.9 1988.83    3551 1978.36  3665.8 1982.56
#Mann= 10 ,-1,0
       0      .1       0     370     .07       0     540      .1       0
     600     .05       0   608.6    .045       0  647.02     .05       0
 2643.09     .06       0 2743.09     .05       0 3333.09     .07       0
 3623.09     .06       0
Bank Sta=608.6,647.02
XS Rating Curve= 0 ,0
Exp/Cntr(USF)=0,0
Exp/Cntr=0.3,0.1

Type RM Length L Ch R = 1 ,14520   ,1146.2,1146.2,1146.2
XS GIS Cut Line= 3
2303617.78334338731052.3678003322302061.92179363732811.080791006
 2301362.1629017733251.696737741
#Sta/Elev= 30
       0  1990.7    50.7 1971.63   123.6 1955.21   135.2 1949.35   171.5 1948.64
   183.5 1943.58   205.7 1940.71     674 1937.88   708.7 1935.36  1336.4 1936.74
  1344.91933.151  1354.7 1931.25  1389.41932.916  1407.2 1936.91  2073.2 1936.22
  2098.7 1941.67  2181.7 1950.73  2271.5 1968.94  2340.3 1970.39  2435.3 1980.24
  2455.4 1980.13  2502.2 1967.93  2553.5 1966.22  2577.3 1975.64  2761.4 2003.54
  2870.3 2028.57  2903.3 2028.91  2971.6 2019.44    2992 2021.77  3175.1 2083.86
#Mann= 13 ,-1,0
       0      .1       0      40     .07       0     190     .05       0
     480     .07       0     490     .05       0    1140      .1       0
  1344.9    .045       0  1389.4      .1       0    1400     .05       0
    2120     .06       0    2270      .1       0 2498.14     .06       0
 2518.14      .1       0
Bank Sta=1344.9,1389.4
XS Rating Curve= 0 ,0
Exp/Cntr(USF)=0,0
Exp/Cntr=0.3,0.1

Type RM Length L Ch R = 1 ,13373   ,1536.8,1536.8,1536.8
XS GIS Cut Line= 2
2303306.58469787730518.1574925152300967.04747094733032.818976471
#Sta/Elev= 30
       0 1967.48    88.8 1958.28   430.3 1941.69  1003.9 1935.12  1293.5 1938.24
    1368  1931.3  1386.4    1935  1559.7 1936.33 1568.311932.763  1604.61932.718
  1642.6 1935.86  1990.7 1935.32  2014.7 1934.19  2024.7 1930.89  2035.4 1933.93
  2178.6 1937.05  2240.9 1954.66  2298.8 1957.37  2323.1 1969.84  2347.3 1966.79
  2428.8 1967.37  2479.1 1978.58  2582.9 1992.74  2724.9  2016.9  2769.4  2032.5
  2888.8 2060.71    3009 2097.69  3238.8 2156.92  3374.3 2181.13  3434.7 2188.78
#Mann= 10 ,-1,0
       0      .1       0      20     .07       0     150     .06       0
     160     .05       0    1220      .1       0 1568.31    .045       0
  1604.6      .1       0    2190     .06       0    2330     .05       0
    2430      .1       0
Bank Sta=1568.31,1604.6
XS Rating Curve= 0 ,0
Exp/Cntr(USF)=0,0
Exp/Cntr=0.3,0.1

Type RM Length L Ch R = 1 ,11837   ,744.8,744.8,744.8
XS GIS Cut Line= 2
2303253.14805109730327.7055832852300611.38497937731708.245778893
#Sta/Elev= 30
       0 1985.33    93.7 1959.77   158.6 1958.17   253.8  1950.9   387.2 1948.39
   443.5  1940.5     493 1942.56   772.5 1935.61   837.7 1937.94   863.1 1934.38
  1617.3 1935.24  1762.6 1934.41  1790.9 1932.29  1932.8 1934.95  1949.3  1930.8
  1977.9 1929.74  1987.8 1930.51  1999.7 1932.94  2090.7 1932.15  2131.4 1934.24
  2158.4 1942.91  2221.6 1952.83  2465.3  2025.7  2587.2 2044.34  2614.3  2046.6
  2636.8 2044.12  2654.9 2055.39  2882.1 2151.54  2921.6 2164.68  2980.7 2179.37
#Mann= 10 ,-1,0
       0      .1       0      70     .07       0     180     .06       0
     220     .05       0    1700      .1       0    1730     .05       0
    1840     .08       0    1920      .1       0  1949.3    .045       0
  1987.8      .1       0
Bank Sta=1949.3,1987.8
XS Rating Curve= 0 ,0
Exp/Cntr(USF)=0,0
Exp/Cntr=0.3,0.1