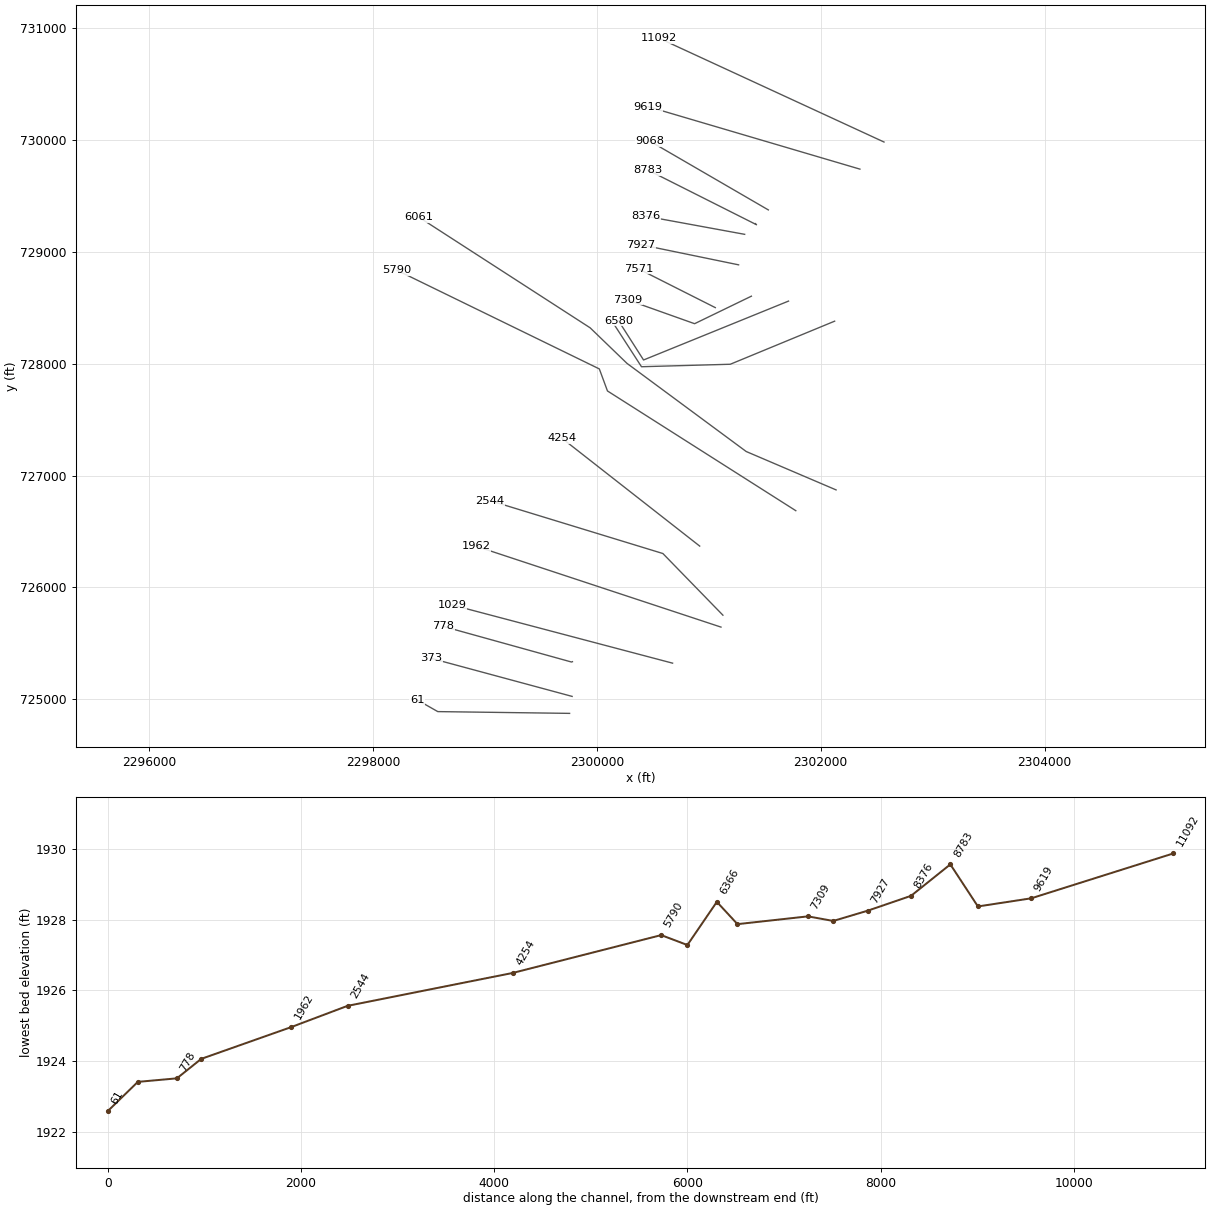
HEC-RAS study LEADNGCK.prj: LEADNGCK

--- LEADNGCK.g01 (geometry) --- (continued)

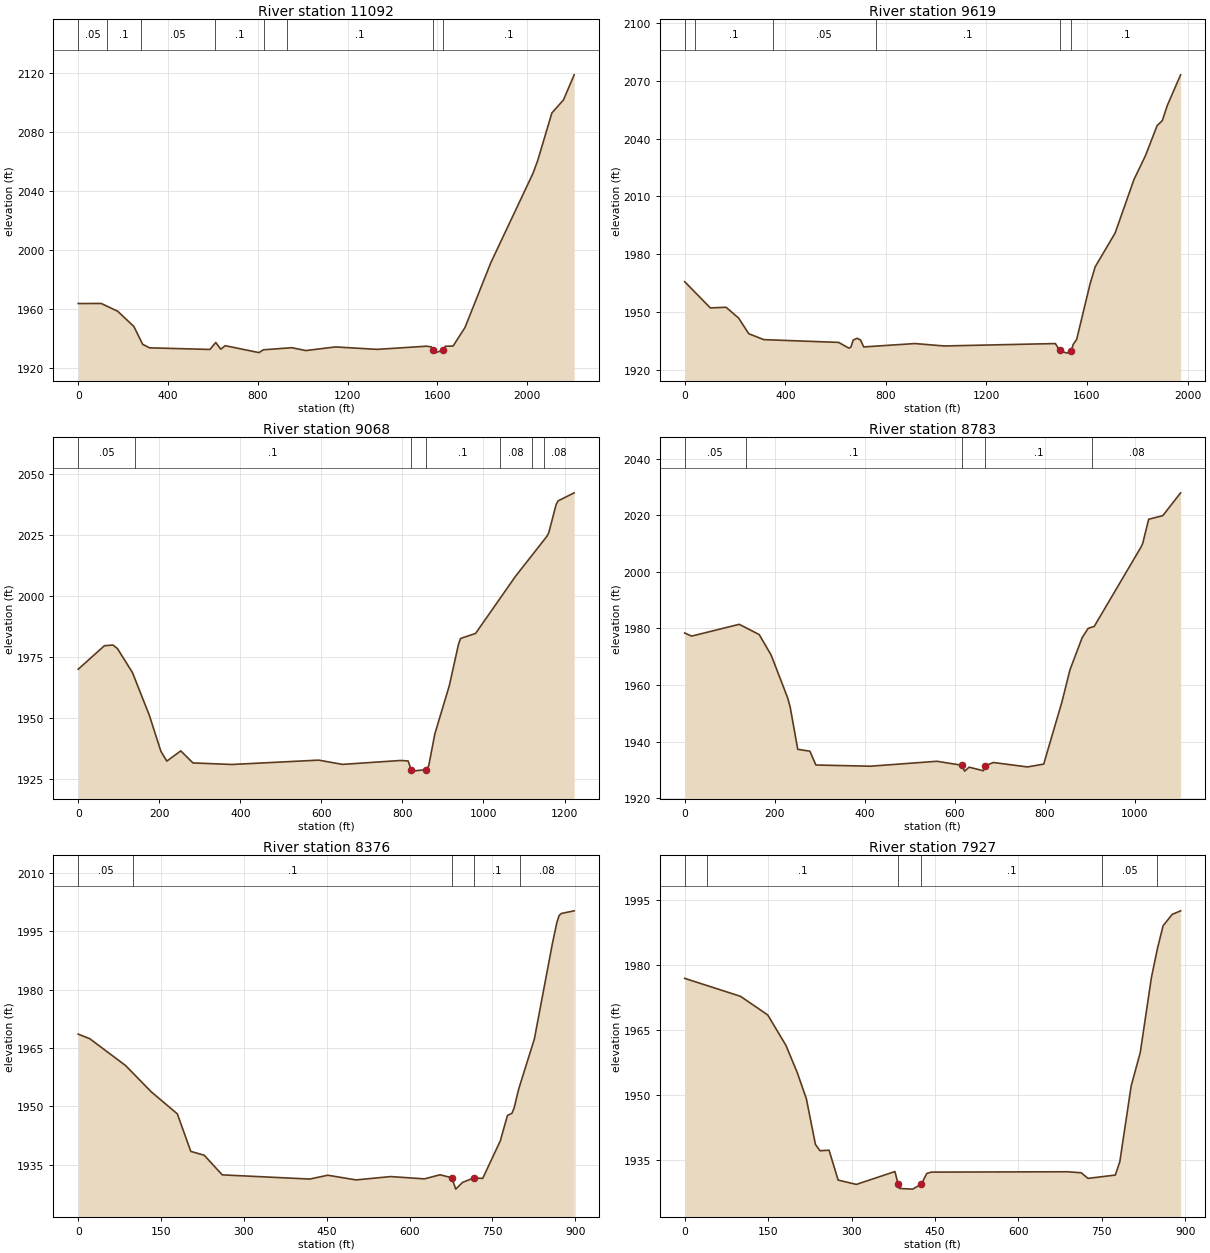
Type RM Length L Ch R = 1 ,11092   ,1472.5,1472.5,1472.5
XS GIS Cut Line= 2
2302565.03513696729980.805200307 2300558.6178085730907.391204665
#Sta/Elev= 30
       0 1963.55   102.3 1963.59   175.7 1958.34   248.1 1947.94   287.3 1935.83
   318.2 1933.46   586.9 1932.37   612.8  1937.1   635.4 1932.55     655 1934.92
   805.7 1930.22   824.9 1932.13   952.6 1933.55  1014.3 1931.61  1146.3 1934.08
  1331.5 1932.42  1553.2 1934.58  1573.9 1934.09  1579.3 1931.95  1586.3 1929.87
  1627.31931.973  1635.6 1934.52  1670.5 1934.68  1723.7 1947.31  1838.2 1991.09
  2026.4 2051.86  2047.5 2060.56  2110.7 2092.91  2162.3 2101.74    2210  2118.8
#Mann= 8 ,-1,0
       0     .05       0     130      .1       0     280     .05       0
     610      .1       0     830     .05       0     930      .1       0
  1579.3    .045       0  1627.3      .1       0
Bank Sta=1579.3,1627.3
XS Rating Curve= 0 ,0
Exp/Cntr(USF)=0,0
Exp/Cntr=0.3,0.1

Type RM Length L Ch R = 1 ,9619    ,551.2,551.2,551.2
XS GIS Cut Line= 2
2302350.14526584 729738.533566472300458.26139644730296.847468024
#Sta/Elev= 30
       0 1965.71   102.1 1952.08   164.7 1952.42   214.8 1946.76   254.9 1938.67
   314.8 1935.61   612.3 1934.17   652.7 1931.19     661 1931.72   670.3 1935.39
     686 1936.31   699.3 1935.44   712.2 1931.82   915.4 1933.57  1032.2 1932.32
  1474.3 1933.57  1491.31930.003  1519.6  1928.6  1537.91929.905  1545.2 1933.09
  1559.1 1935.75  1611.9 1964.32  1632.7  1973.4    1712 1990.95    1787 2018.75
  1832.9  2031.2  1878.8 2046.69  1899.7 2049.36  1919.7 2057.26  1972.5 2073.11
#Mann= 6 ,-1,0
       0     .05       0      40      .1       0     350     .05       0
     760      .1       0  1491.3    .045       0  1537.9      .1       0
Bank Sta=1491.3,1537.9
XS Rating Curve= 0 ,0
Exp/Cntr(USF)=0,0
Exp/Cntr=0.3,0.1

Type RM Length L Ch R = 1 ,9068    ,285.4,285.4,285.4
XS GIS Cut Line= 2
2301532.03791025729374.0608170372300473.80394316 729988.76819383
#Sta/Elev= 30
       0 1970.07    64.6 1979.69    85.8 1979.97      97  1978.5   133.9 1968.69
   175.6 1951.19   204.1 1936.46   218.7 1932.47   253.1 1936.66   283.1 1931.73
   379.2 1931.09   593.3 1932.87   652.1 1931.13   795.5 1932.73     814 1932.53
   821.7 1928.97   823.2 1928.37   858.3 1928.97   864.9 1930.53     880 1943.59
   915.8 1963.38   938.5 1980.35   943.5 1982.66   980.5 1984.72    1079 2008.09
  1156.3 2024.42    1161 2025.85  1179.4 2037.53  1184.1 2038.96  1223.8 2042.27
#Mann= 7 ,-1,0
       0     .05       0     140      .1       0   821.7    .045       0
   858.3      .1       0    1040     .08       0    1120      .1       0
    1150     .08       0
Bank Sta=821.7,858.3
XS Rating Curve= 0 ,0
Exp/Cntr(USF)=0,0
Exp/Cntr=0.3,0.1

Type RM Length L Ch R = 1 ,8783    ,407.1,407.1,407.1
XS GIS Cut Line= 3
2301414.78022035729251.6243231372301426.64374814729241.707802134
  2300456.824757729730.152099205
#Sta/Elev= 30
       0 1978.37    15.5 1977.28   121.2 1981.44   165.5 1977.82   192.1 1970.55
   228.7 1955.45   234.3 1952.19   251.1 1937.27     278 1936.61   291.4 1931.72
   412.3  1931.3   560.1 1933.04   615.6 1931.63   621.6 1929.56   631.8 1930.96
   663.2 1929.69   667.6 1931.44   685.5 1932.61   761.3 1931.04   797.3 1932.05
   837.8 1954.05   855.7 1965.41   882.6  1976.7     896 1980.01   909.5 1980.71
  1012.5 2008.51    1017 2009.97  1030.4 2018.57  1061.8 2019.85  1101.3 2027.91
#Mann= 5 ,-1,0
       0     .05       0  135.46      .1       0   615.6    .045       0
   667.6      .1       0  905.46     .08       0
Bank Sta=615.6,667.6
XS Rating Curve= 0 ,0
Exp/Cntr(USF)=0,0
Exp/Cntr=0.3,0.1

Type RM Length L Ch R = 1 ,8376    ,448.5,448.5,448.5
XS GIS Cut Line= 2
2301320.68289356729155.9082927142300437.28533522729318.001880031
#Sta/Elev= 30
       0 1968.56    20.9 1967.38    85.9 1960.46   132.1 1953.73   179.5 1948.04
   203.9 1938.38   228.2 1937.39   260.8 1932.34   419.4 1931.26   451.9 1932.25
   503.2 1931.04   565.8  1931.9   626.9 1931.31   655.3 1932.36  676.451931.606
   683.7 1928.67   695.9 1930.39   716.3 1931.56   732.5 1931.43   764.4  1941.1
   777.3 1947.63   785.4 1948.18   789.5  1949.6   797.6 1954.39   826.1 1967.33
   858.6 1991.78   866.7 1997.21   870.8 1999.05   874.9  1999.6   898.1 2000.28
#Mann= 5 ,-1,0
       0     .05       0     100      .1       0  676.45    .045       0
   716.3      .1       0     800     .08       0
Bank Sta=676.45,716.3
XS Rating Curve= 0 ,0
Exp/Cntr(USF)=0,0
Exp/Cntr=0.3,0.1

Type RM Length L Ch R = 1 ,7927    ,356.1,356.1,356.1
XS GIS Cut Line= 2
2301266.38875173728883.3112469482300393.17590576729063.312639826
#Sta/Elev= 30
       0 1976.95   100.3  1972.8   149.3  1968.5     182 1961.48   202.4 1955.18
   218.7 1949.17   235.1 1938.57   243.2 1937.12   259.6 1937.24   275.9 1930.34
   308.6 1929.34     378 1932.31   383.61929.509   386.2 1928.41   409.8 1928.25
   425.3 1929.37   435.2 1931.86   443.3 1932.18   688.4 1932.26   712.9 1932.03
   725.1 1930.73   774.2  1931.5   782.3 1934.58   802.7 1952.09   819.1 1959.84
     839 1977.07     850 1983.89   860.1 1989.09   876.3 1991.72   891.6 1992.55
#Mann= 6 ,-1,0
       0     .05       0      40      .1       0   383.6    .045       0
   425.3      .1       0     750     .05       0     850     .08       0
Bank Sta=383.6,425.3
XS Rating Curve= 0 ,0
Exp/Cntr(USF)=0,0
Exp/Cntr=0.3,0.1

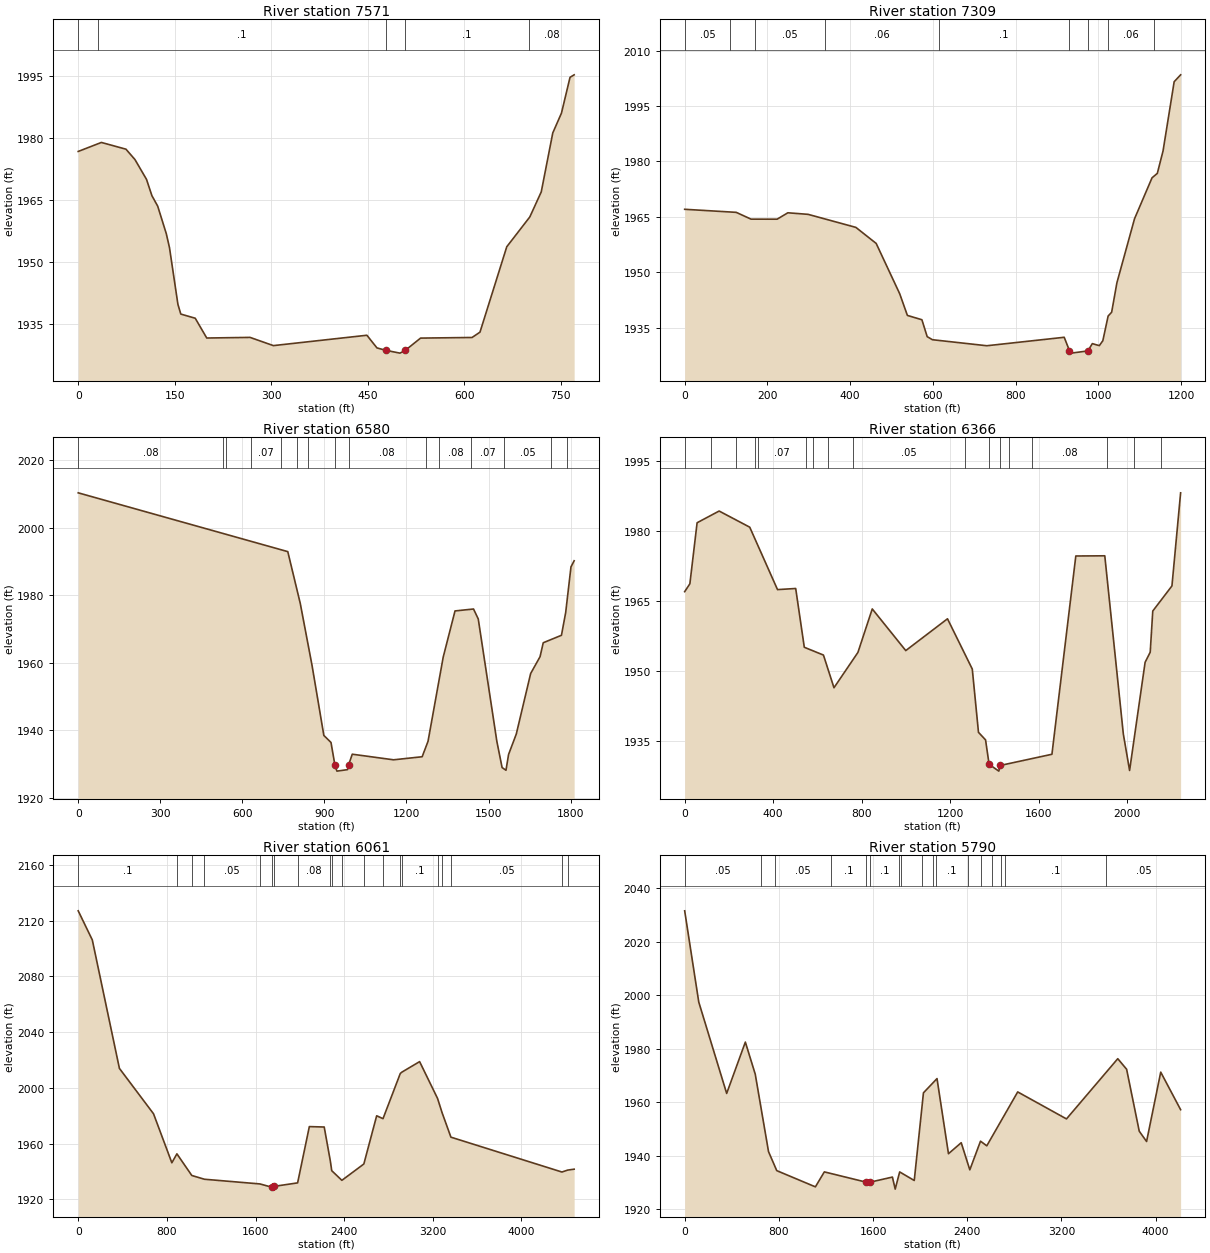
Type RM Length L Ch R = 1 ,7571    ,261.9,261.9,261.9
XS GIS Cut Line= 2
2301058.42036953728500.9330539042300370.61000163728848.245512837
#Sta/Elev= 30
       0 1976.81      36 1978.99    74.2 1977.36    88.2 1974.84   106.1 1970.05
   114.5  1966.1   123.5 1963.56   136.9 1956.86   141.8 1953.52   154.9 1939.78
   159.4 1937.42   181.8 1936.41   199.7 1931.62     267 1931.77   303.2 1929.78
   448.5 1932.29   464.1 1929.23   477.5 1928.65   499.9 1927.96     508 1928.61
   531.9  1931.6   611.9 1931.75   624.2 1933.04   665.8 1953.72   701.6 1960.94
   719.4 1967.02   737.3  1981.3   750.8  1986.1   764.1 1994.76   770.5 1995.37
#Mann= 5 ,-1,0
       0     .05       0      30      .1       0   477.5    .045       0
     508      .1       0     700     .08       0
Bank Sta=477.5,508
XS Rating Curve= 0 ,0
Exp/Cntr(USF)=0,0
Exp/Cntr=0.3,0.1

Type RM Length L Ch R = 1 ,7309    ,729.5,729.5,729.5
XS GIS Cut Line= 3
2301380.55888178728603.2095857242300873.38959523728357.374490963
2300275.12572397 728570.40995391
#Sta/Elev= 30
       0 1967.04   124.6 1966.21   160.4 1964.37   223.4 1964.36   249.4 1966.09
   298.3 1965.67   413.8 1962.14   462.9 1957.79   519.8 1944.15   538.3  1938.3
   573.4 1937.13   586.1 1932.56   598.8 1931.72   730.4 1930.09   917.3 1932.38
   930.1 1928.76   934.3 1928.09   974.6 1928.69   985.3 1930.66  1002.2 1930.12
  1010.7 1931.45  1023.5 1938.13    1032 1939.16  1044.7 1947.14  1087.3 1964.47
  1129.6 1975.56  1142.4 1976.77  1156.2 1982.82  1183.1 2001.58  1198.7 2003.45
#Mann= 9 ,-1,0
       0     .05       0     110     .06       0     170     .05       0
     340     .06       0  613.61      .1       0   930.1    .045       0
   974.6      .1       0 1023.61     .06       0 1133.61     .05       0
Bank Sta=930.1,974.6
XS Rating Curve= 0 ,0
Exp/Cntr(USF)=0,0
Exp/Cntr=0.3,0.1

Type RM Length L Ch R = 1 ,6580    ,213.6,213.6,213.6
XS GIS Cut Line= 3
 2301712.2050108728559.3402460232300417.59299603 728033.02684493
2300194.14667345728383.217914191
#Sta/Elev= 30
       0 2010.27   766.1 1992.86   811.8  1977.5     855 1959.06   897.9 1938.44
   924.1 1936.35  938.16 1929.76   945.7 1927.87   984.5 1928.31   988.8  1929.8
  1001.8 1932.88  1152.8 1931.22  1257.3 1932.13  1278.8 1936.71  1334.3 1961.65
  1377.4  1975.3  1445.1 1975.87  1462.4 1972.91  1530.5 1936.61  1549.5 1928.93
  1563.7 1928.12  1573.2  1932.8  1601.4 1938.85  1653.9 1956.77  1688.3 1961.76
  1699.9 1965.88  1766.5 1968.09    1782 1974.86  1801.3 1988.35  1812.9 1990.15
#Mann= 15 ,-1,0
       0     .08       0     530     .07       0     540     .08       0
     630     .07       0     740     .08       0     800     .07       0
     840     .08       0  938.16    .045       0   988.8     .08       0
    1270     .07       0    1320     .08       0 1437.51     .07       0
 1557.51     .05       0 1727.51     .07       0 1787.51     .05       0
Bank Sta=938.16,988.8
XS Rating Curve= 0 ,0
Exp/Cntr(USF)=0,0
Exp/Cntr=0.3,0.1

Type RM Length L Ch R = 1 ,6366    ,304.8,304.8,304.8
XS GIS Cut Line= 4
2302124.13840687728379.8962794232301191.98682427727994.896777762
2300399.16722812727972.724331783 2300159.7047284728342.888274114
#Sta/Elev= 30
       0 1966.94    23.5 1968.63    56.2  1981.7   155.8 1984.21   294.2 1980.75
   419.8 1967.38     502 1967.62   540.9 1955.03   627.5 1953.36   675.1 1946.36
   783.3 1953.92   848.2 1963.24   999.7 1954.32  1188.4 1961.13  1300.5 1950.36
  1328.5 1936.81  1360.5 1935.19  1376.5 1929.96  1420.5  1928.51426.6991929.712
  1660.6 1932.11  1768.6 1974.58  1899.6 1974.62  1983.5 1936.44  2011.8 1928.64
  2081.9  1951.8    2105 1953.97  2116.6 1962.79  2203.3 1968.17  2242.5 1988.11
#Mann= 17 ,-1,0
       0     .05       0     120     .06       0     230     .08       0
     320     .05       0     330     .07       0     550     .05       0
     580     .07       0     650     .06       0     760     .05       0
 1268.53      .1       0  1376.5    .045       01426.699      .1       0
 1468.53     .07       0 1568.53     .08       0 1911.66     .07       0
 2031.66     .05       0 2151.66     .07       0
Bank Sta=1376.5,1426.699
XS Rating Curve= 0 ,0
Exp/Cntr(USF)=0,0
Exp/Cntr=0.3,0.1

Type RM Length L Ch R = 1 ,6061    ,271,271,271
XS GIS Cut Line= 5
2302137.14493037726871.9936343482301334.41894822 727215.08089917
2300269.63313993 728002.781842432299940.57066991 728320.49733072
2298411.62020397729308.961450957
#Sta/Elev= 30
       0  2127.1   127.2 2106.19   371.8 2013.98   679.7 1981.38     845 1946.19
   890.7 1952.62    1025 1937.08  1139.5 1934.37  1639.7 1931.01    17451928.707
  1761.4 1927.28  1770.71929.291    1980 1931.77  2085.8 1972.17    2220 1971.88
  2275.8 1947.24  2287.9 1940.52  2379.4 1933.59  2577.6 1945.32  2693.4 1979.94
  2750.6 1977.87  2906.6 2010.32  2921.8 2011.32  3080.9 2018.83  3242.9 1992.39
  3284.1 1982.08  3363.4 1964.59  4365.3 1939.56  4417.4 1940.95  4475.5  1941.6
#Mann= 20 ,-1,0
       0      .1       0   890.7     .07       0    1025     .06       0
  1139.5     .05       0  1639.7      .1       0    1745    .045       0
  1770.7      .1       0    1980     .08       0  2275.8     .07       0
  2287.9     .05       0  2379.4     .07       0  2577.6     .05       0
  2750.6     .08       0  2906.6     .07       0  2921.8      .1       0
  3242.9     .05       0  3284.1      .1       0  3363.4     .05       0
  4365.3     .07       0  4417.4     .06       0
Bank Sta=1745,1770.7
XS Rating Curve= 0 ,0
Exp/Cntr(USF)=0,0
Exp/Cntr=0.3,0.1

Type RM Length L Ch R = 1 ,5790    ,1536.7,1536.7,1536.7
XS GIS Cut Line= 4
2301777.14174112726686.448326949 2300095.2594699727756.322970156
2300022.67919476727953.1338173212298216.36634352728834.268936007
#Sta/Elev= 30
       0 2031.52   119.7 1997.43   356.7 1963.31   515.4 1982.49   599.6 1970.48
   712.3 1941.57   782.1 1934.47  1110.5 1928.41  1186.3    1934  1540.31930.179
  1573.1 1930.14  1764.7 1932.06  1788.4 1927.56  1826.3 1933.98  1950.2 1930.79
  2028.3 1963.53  2143.5 1968.85  2240.9 1940.79  2349.2  1944.9  2422.2 1934.76
    2513 1945.47  2566.4 1943.74    2829 1963.87  3243.3 1953.79    3679 1976.28
  3754.2 1972.34  3861.5  1949.2  3923.8 1945.35    4044 1971.26  4212.9 1957.24
#Mann= 17 ,-1,0
       0     .05       0     650     .07       0     770     .05       0
    1240      .1       0  1540.3    .045       0  1573.1      .1       0
    1820     .05       0    1840     .07       0 2013.33     .08       0
 2113.33     .07       0 2133.33      .1       0  2403.1     .05       0
  2513.1     .06       0  2613.1      .1       0  2683.1     .05       0
  2723.1      .1       0  3583.1     .05       0
Bank Sta=1540.3,1573.1
XS Rating Curve= 0 ,0
Exp/Cntr(USF)=0,0
Exp/Cntr=0.3,0.1

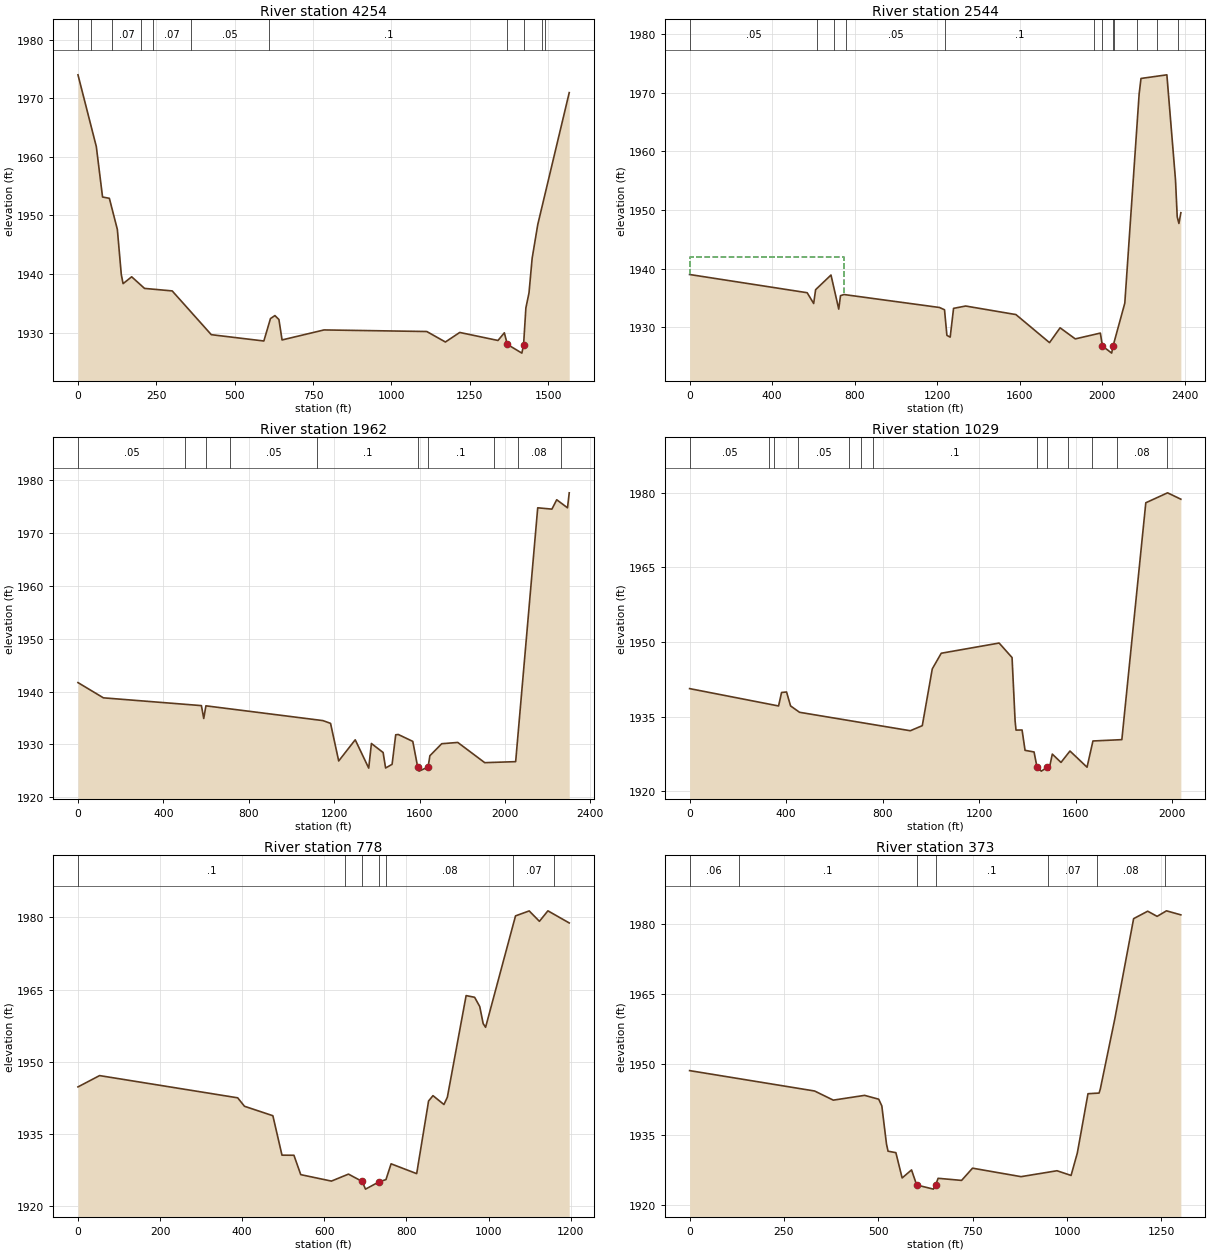
Type RM Length L Ch R = 1 ,4254    ,1709.3,1709.3,1709.3
XS GIS Cut Line= 2
2300919.01798535726369.9613656042299685.21346809727336.300132725
#Sta/Elev= 30
       0    1974    58.5 1961.75    78.4 1953.14   100.1 1952.92   125.6 1947.61
   138.2  1939.9   143.9 1938.35   171.3 1939.52   212.3 1937.54   300.6 1937.11
   425.3 1929.64     593 1928.56   614.1 1932.39   628.3  1932.9     641 1932.23
   651.1 1928.74     785 1930.45  1112.7 1930.18  1172.2 1928.39  1217.9 1930.02
  1339.9 1928.65  1360.2 1929.96  1369.71927.985  1416.1 1926.49  1421.5 1927.87
  1428.9  1934.2  1438.9 1936.78  1448.9 1942.68  1466.9 1948.46  1567.2 1970.96
#Mann= 11 ,-1,0
       0     .07       0      40      .1       0     110     .07       0
     200     .08       0     240     .07       0     360     .05       0
     610      .1       0  1369.7    .045       0  1421.5      .1       0
    1480     .06       0    1490     .07       0
Bank Sta=1369.7,1421.5
XS Rating Curve= 0 ,0
Exp/Cntr(USF)=0,0
Exp/Cntr=0.3,0.1

Type RM Length L Ch R = 1 ,2544    ,582.4,582.4,582.4
XS GIS Cut Line= 3
2301126.34273619725752.5025544512300590.21110061726303.515305929
2299047.34083732726775.767779368
#Sta/Elev= 30
       0 1938.98   570.2 1935.87   601.7 1934.03   611.1 1936.39   685.7 1938.89
   723.3 1933.07   731.8 1935.37   748.8 1935.56  1211.8 1933.35  1236.2 1932.96
  1247.8 1928.59  1263.7 1928.29  1280.1  1933.2  1338.7  1933.6  1582.5 1932.14
  1745.4 1927.35  1796.7 1929.88  1870.3 1927.99    1992 1928.98  2001.91926.786
  2046.8 1925.56  2054.21926.855  2110.5 1934.09    2180 1969.78    2189 1972.44
  2314.5 1973.06  2356.4 1955.09  2364.7 1948.82  2372.9 1947.69  2382.3 1949.52
#Mann= 12 ,-1,0
       0     .05       0     620     .08       0     700     .06       0
     760     .05       0  1238.8      .1       0  1958.8     .06       0
  2001.9    .045       0  2054.2     .06       0  2058.8     .08       0
  2168.8      .1       0  2268.8     .06       0  2368.8     .05       0
#XS Ineff= 2 , 0
          750.86 1941.98
Permanent Ineff=
       F       F
Bank Sta=2001.9,2054.2
XS Rating Curve= 0 ,0
Exp/Cntr(USF)=0,0
Exp/Cntr=0.3,0.1

Type RM Length L Ch R = 1 ,1962    ,932.5,932.5,932.5
XS GIS Cut Line= 2
2301109.13006187 725646.06072754 2298924.4586163726367.917889584
#Sta/Elev= 30
       0 1941.69     119 1938.81   578.1 1937.34     589 1934.91   599.2  1937.3
  1146.9 1934.51  1182.9 1933.99  1221.1 1926.88  1298.5 1930.88  1361.7 1925.53
  1374.3 1930.18  1429.1 1928.48  1440.8 1925.55  1471.2 1926.25  1488.1 1931.83
  1500.3 1931.88  1568.1 1930.58  1590.91925.766  1597.6 1924.96  1639.81925.735
  1648.2 1927.87  1703.6 1930.14  1778.8 1930.38  1905.1 1926.56  2049.9 1926.75
  2153.2 1974.72  2219.7 1974.47  2242.2 1976.24  2292.7 1974.72  2300.8 1977.55
#Mann= 10 ,-1,0
       0     .05       0     500     .07       0     600     .06       0
     710     .05       0    1120      .1       0  1590.9    .045       0
  1639.8      .1       0    1950     .06       0    2060     .08       0
    2260     .06       0
Bank Sta=1590.9,1639.8
XS Rating Curve= 0 ,0
Exp/Cntr(USF)=0,0
Exp/Cntr=0.3,0.1

Type RM Length L Ch R = 1 ,1029    ,251.8,251.8,251.8
XS GIS Cut Line= 2
2300676.85597491725323.7408204162298707.73947731725844.050361045
#Sta/Elev= 30
       0 1940.65   368.9 1937.16   381.3 1939.87     402 1939.97   418.6 1937.17
   455.8 1935.89     915 1932.18   964.7  1933.2  1006.1 1944.61  1043.3 1947.76
  1283.3 1949.81  1336.9 1946.89  1349.5 1934.18  1353.3 1932.31  1378.4 1932.33
  1390.8 1928.24  1428.1 1927.91  1440.5 1924.84    1458 1924.06  1481.9 1924.79
  1490.1 1924.36  1503.8 1927.48  1539.8 1925.81    1577  1928.1  1647.8 1924.85
  1672.2 1930.12  1792.1 1930.39  1891.4 1978.01  1981.6 1980.01  2036.7 1978.73
#Mann= 13 ,-1,0
       0     .05       0     330     .07       0     350     .06       0
     450     .05       0     660      .1       0     710     .05       0
     760      .1       0  1440.5    .045       0  1481.9      .1       0
    1570     .06       0    1670     .07       0    1770     .08       0
    1980     .07       0
Bank Sta=1440.5,1481.9
XS Rating Curve= 0 ,0
Exp/Cntr(USF)=0,0
Exp/Cntr=0.3,0.1

Type RM Length L Ch R = 1 ,778     ,404.3,404.3,404.3
XS GIS Cut Line= 3
2299782.65989527 725337.113744182299773.88335119  725334.0193288
2298630.15491257725651.717042447
#Sta/Elev= 30
       0 1944.76    52.6 1947.11   388.9 1942.49   405.5 1940.73   474.6 1938.77
   496.8 1930.57   525.9 1930.55   542.5 1926.52   617.2 1925.18   658.7 1926.63
   691.9 1925.11   700.2 1923.51   733.4 1925.03     750 1925.49   762.5 1928.77
   824.8 1926.73   853.8 1941.83   864.5 1942.94   891.2  1941.1   899.5 1942.61
   945.2 1963.74   965.9 1963.39   978.4 1961.46   986.7 1957.92   992.6 1957.15
  1065.5 1980.31  1098.8 1981.34  1123.7 1979.18  1144.4 1981.36  1196.3 1978.84
#Mann= 7 ,-1,0
       0      .1       0  649.31     .07       0   691.9    .045       0
   733.4     .07       0  749.31     .08       0 1059.31     .07       0
 1159.31     .05       0
Bank Sta=691.9,733.4
XS Rating Curve= 0 ,0
Exp/Cntr(USF)=0,0
Exp/Cntr=0.3,0.1

Type RM Length L Ch R = 1 ,373     ,312.4,312.4,312.4
XS GIS Cut Line= 2
 2299779.7143723725026.7233771412298523.46355344725366.063744802
#Sta/Elev= 30
       0 1948.69   331.1 1944.34   380.7 1942.39   463.6 1943.41   500.9 1942.59
   509.2 1941.16   521.6 1932.99   525.7  1931.5   546.4 1931.19     563 1925.79
   587.9 1927.51   601.51924.297   645.9 1923.41   651.41924.203   658.3 1925.72
   720.5 1925.27   749.5 1927.88   877.9 1926.07   973.2 1927.33  1010.5 1926.33
  1027.1 1931.12  1055.3 1943.76  1084.7  1943.9  1087.9 1944.75  1126.5 1959.78
  1176.2  1981.1  1213.5 1982.69  1238.4 1981.59  1263.2 1982.77  1301.3 1981.91
#Mann= 7 ,-1,0
       0     .06       0     130      .1       0   601.5    .045       0
   651.4      .1       0     950     .07       0    1080     .08       0
    1260     .07       0
Bank Sta=601.5,651.4
XS Rating Curve= 0 ,0
Exp/Cntr(USF)=0,0
Exp/Cntr=0.3,0.1

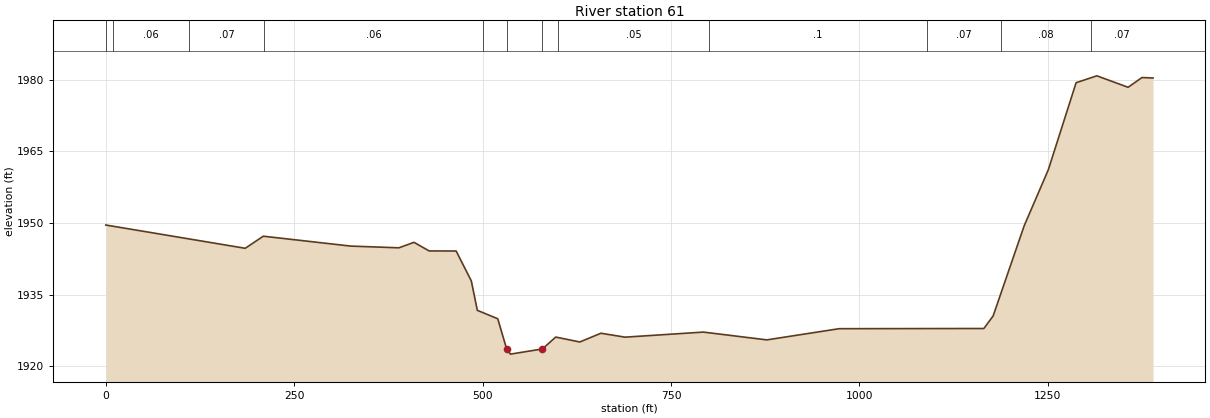
Type RM Length L Ch R = 1 ,61      ,,,
XS GIS Cut Line= 3
2299757.15251943724875.0607171412298579.87392373 724890.90092327
2298395.42375256724995.820143363
#Sta/Elev= 30
       0 1949.59     185 1944.72     209 1947.25     325 1945.18     389 1944.82
     409 1945.97     429 1944.17   464.9 1944.15     485 1937.91     493 1931.74
   520.1 1929.98   532.11923.563     537 1922.58   579.4 1923.66     597 1926.15
     629 1925.12     657 1926.95     689 1926.13     793 1927.19   877.1 1925.56
   973.1  1927.9  1165.1 1927.94  1177.4 1930.56  1218.5 1949.38  1250.7 1961.18
  1287.5 1979.36  1315.1  1980.8  1356.5  1978.4  1374.9 1980.44  1389.6 1980.35
#Mann= 12 ,-1,0
       0     .05       0      10     .06       0     110     .07       0
     210     .06       0     500      .1       0   532.1    .045       0
   579.4      .1       0     600     .05       0     800      .1       0
    1090     .07       0 1187.39     .08       0 1307.39     .07       0
Bank Sta=532.1,579.4
XS Rating Curve= 0 ,0
Exp/Cntr(USF)=0,0
Exp/Cntr=0.3,0.1
LCMann Table=0

Chan Stop Cuts=-1
Use User Specified Reach Order=0
Composite Channel Slope=5